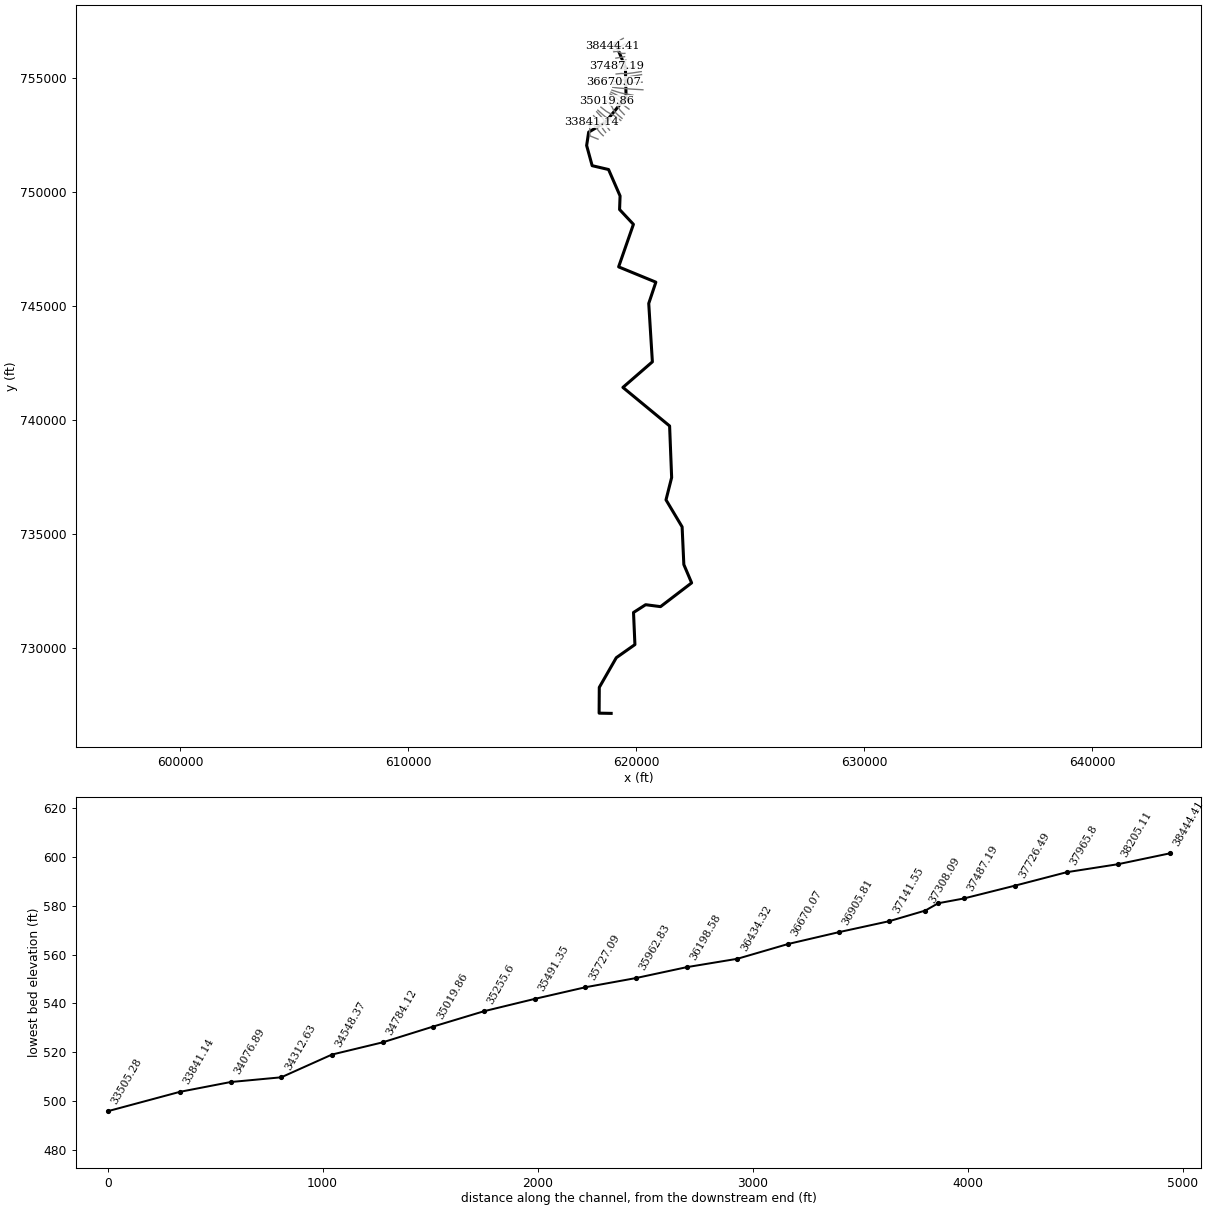
--- 3211_ras.prj (project) ---

Proj Title=3211
Current Plan=p01
Default Exp/Contr=0.3,0.1
English Units
Geom File=g01
Flow File=f01
Plan File=p01
Y Axis Title=Elevation
X Axis Title(PF)=Main Channel Distance
X Axis Title(XS)=Station
BEGIN DESCRIPTION:
RFD model 3211 exported to HEC-RAS
END DESCRIPTION:

--- 3211_ras.p01 (plan) ---

Plan Title=Plan 01
Program Version=4.10
Short Identifier=Plan 01
Geom File=g01
Flow File=f01
Subcritical Flow
Calc Critical at every XS
Secant Critical Depth

--- 3211_ras.f01 (steady flow) ---

Flow Title=Flow 01
Program Version=5.01
Number of Profiles= 6
Profile Names=10yr,25yr,50yr,100yr,100plus,500yr
River Rch & RM=3211,123,38444.41
 2510.92 4093.75 5607.95 6999.9910219.9912274.81
River Rch & RM=3211,123,38205.11
 2513.85 4099.02  5615.6 7010.0210234.6312291.79
River Rch & RM=3211,123, 37965.8
 2521.94 4113.55 5636.74 7037.7810275.1612338.92
River Rch & RM=3211,123,37726.49
 2523.69 4116.72 5641.36 7043.8610284.0412349.28
River Rch & RM=3211,123,37487.19
 2527.37 4123.35 5651.02 7056.57 10302.612370.93
River Rch & RM=3211,123,37368.36
 2528.32 4125.08 5653.54 7059.8910307.4312376.58
River Rch & RM=3211,123,37141.55
 4699.36 7651.4910478.2513062.3819071.0820897.82
River Rch & RM=3211,123,36905.81
 4859.84 7937.1210891.5513602.2719859.3121724.65
River Rch & RM=3211,123,36670.07
  4871.7 7958.6610923.0813643.8419920.0121789.48
River Rch & RM=3211,123,36434.32
 4875.82 7966.1610934.0613658.3319941.1621812.07
River Rch & RM=3211,123,36198.58
 4885.57 7983.8710960.0113692.5719991.1521865.51
River Rch & RM=3211,123,35962.83
 4886.93 7986.3610963.6513697.3919998.1821873.04
River Rch & RM=3211,123,35727.09
 4980.77 8156.2911212.0114024.5620475.8522380.74
River Rch & RM=3211,123,35491.35
 4992.33 8177.3211242.8314065.2520535.2622444.07
River Rch & RM=3211,123, 35255.6
 4993.83 8180.0411246.8214070.5120542.9522452.26
River Rch & RM=3211,123,35019.86
 4999.15 8189.7211260.98 14089.220570.2322481.29
River Rch & RM=3211,123,34784.12
 5015.43 8219.33 11304.414146.5320653.9422570.52
River Rch & RM=3211,123,34548.37
 5019.05 8225.9511314.1214159.39 20672.722590.58
River Rch & RM=3211,123,34312.63
 5027.89 8242.0211337.6514190.4520718.0522638.83
River Rch & RM=3211,123,34076.89
 5028.83 8243.7311340.1714193.7820722.9222644.03
River Rch & RM=3211,123,33841.14
 5041.74 8267.1911374.5314239.1420789.1522714.48
River Rch & RM=3211,123,33505.28
 5081.42 8338.7711478.9614376.5220989.7122926.06
River Rch & RM=3211,123,33097.37
 5085.65 8346.4511490.1814391.3121011.3222948.95
River Rch & RM=3211,123,32851.54
 5118.56 8405.6611576.4514504.6821176.83 23122.9
River Rch & RM=3211,123,32605.71
 5121.79 8411.5511585.0814516.0821193.4723140.56
River Rch & RM=3211,123,32359.89
 5145.73 8455.1111648.9414600.4421316.6423271.38
River Rch & RM=3211,123,32114.06
 5147.42 8458.2111653.5314606.5321325.5323280.93
River Rch & RM=3211,123,31868.23
 5154.78 8471.7111673.3914632.8521363.9623322.01
River Rch & RM=3211,123,31622.41
 5156.47 8474.8111677.9714638.9421372.8523331.55
River Rch & RM=3211,123,31376.58
 5175.08 8508.8711728.0614705.2721469.6923434.87
River Rch & RM=3211,123,31130.75
 5196.76 8548.58 11786.514782.7121582.7623555.54
River Rch & RM=3211,123,30884.93
 5200.78 8555.98 11797.414797.1921603.8923578.19
River Rch & RM=3211,123, 30639.1
 5208.66 8570.4811818.8114825.6321645.4223622.73
River Rch & RM=3211,123,30393.27
 5212.09 8576.8411828.2214838.1621663.7123642.43
River Rch & RM=3211,123,30147.45
 5255.52 8657.13   1194714996.2421894.5123890.71
River Rch & RM=3211,123,29901.62
  5272.4 8688.4311993.3915058.0621984.7823987.99
River Rch & RM=3211,123,29655.79
 5275.57 8694.3812002.2515069.93 22002.124006.85
River Rch & RM=3211,123,29409.97
 5278.87 8700.5612011.4715082.26 22020.124026.43
River Rch & RM=3211,123,29164.14
 5286.66 8715.2512033.4315111.7522063.1624073.53
River Rch & RM=3211,123,28918.31
 5289.31 8720.2312040.8815121.7522077.7524089.47
River Rch & RM=3211,123,28672.49
 5290.83 8723.1312045.23 15127.6 22086.324098.88
River Rch & RM=3211,123,28426.66
 5292.43 8726.1912049.8515133.8522095.4324109.02
River Rch & RM=3211,123,28180.83
 5582.82 9254.8612825.66 16159.8 23593.325687.59
River Rch & RM=3211,123,27935.01
 5584.52  9258.112830.55 16166.423602.9425698.18
River Rch & RM=3211,123,27689.18
 5587.23 9263.2912838.3616176.9623618.3625715.13
River Rch & RM=3211,123,27443.35
 5588.92 9266.5312843.2516183.56   2362825725.72
River Rch & RM=3211,123,27197.53
 5591.75 9271.9312851.3816194.5623644.0625743.36
River Rch & RM=3211,123,26891.65
 5594.88 9277.9412860.4616206.8423661.9925763.11
River Rch & RM=3211,123,26794.34
 5595.75 9279.6212863.0116210.3123667.0625768.75
River Rch & RM=3211,123,26525.69
 5736.04 9542.9613256.1916737.7824437.1626600.03
River Rch & RM=3211,123, 25958.1
 5740.77  9552.213270.2916757.0224465.2526631.37
River Rch & RM=3211,123,25728.05
 5741.72 9554.0513273.1216760.8724470.8826637.64
River Rch & RM=3211,123,25494.01
 5777.56 9621.2513373.4116895.3924667.2826848.95
River Rch & RM=3211,123,25183.49
 5812.95 9691.0113480.2917041.7524880.9527088.67
River Rch & RM=3211,123,25051.05
 5814.34 9693.7113484.3817047.3224889.0927097.66
River Rch & RM=3211,123,24488.39
    600810050.6114012.2717750.2825915.4128179.78
River Rch & RM=3211,123, 23859.5
 6013.8310061.89 14029.417773.5925949.4428217.22
River Rch & RM=3211,123,23613.59
 6018.16 10070.514042.6517791.8225976.0528247.16
River Rch & RM=3211,123,23367.69
 6023.7110081.5114059.5817815.0826010.0128285.25
River Rch & RM=3211,123,23121.78
 6034.4610102.4114091.4117858.4726073.3728355.26
River Rch & RM=3211,123,22875.88
 6036.7810106.9814098.4117868.0626087.3728370.88
River Rch & RM=3211,123,22629.98
 6041.7910116.7914113.4117888.5726117.3228404.15
River Rch & RM=3211,123,22384.07
 6087.91 10208.114253.7218081.2426398.6228719.13
River Rch & RM=3211,123,22138.17
 6090.3910213.1514261.5918092.1726414.5728737.38
River Rch & RM=3211,123,21892.26
 6095.9610224.5114279.3218116.8226450.5528778.59
River Rch & RM=3211,123,21646.36
 6104.0210240.9514304.95 18152.4 26502.5   28838
River Rch & RM=3211,123,21400.45
 6107.4410247.9614315.9218167.6826524.8128863.64
River Rch & RM=3211,123,21154.55
 6114.5310262.6714339.0418199.9926571.9928918.26
River Rch & RM=3211,123,20908.64
 6118.1310270.3414351.2718217.2426597.1728947.91
River Rch & RM=3211,123,20416.83
 6124.64 10284.414373.7818249.1226643.7129003.14
River Rch & RM=3211,123,20170.93
 6125.9510287.2714378.3918255.6826653.2929014.59
River Rch & RM=3211,123,19925.02
 6133.4310303.1714403.6918291.3426705.3529075.83
River Rch & RM=3211,123,19346.18
 6201.9210445.7114628.2518605.7127164.3429608.01
River Rch & RM=3211,123, 18695.5
 6211.6310467.6314664.0718657.2127239.5329699.45
River Rch & RM=3211,123,18203.69
 6218.1910482.3314688.0118691.5327289.6429760.13
River Rch & RM=3211,123,17957.78
 6220.09 10486.714695.2118701.9427304.8429778.79
River Rch & RM=3211,123,17711.88
 6224.0410495.5614709.6518722.6627335.0829815.43
River Rch & RM=3211,123,17465.97
 6232.2310513.8414739.3818765.27 27397.329890.66
River Rch & RM=3211,123,17220.07
 6235.2610520.8414750.9118781.9627421.6529920.59
River Rch & RM=3211,123,16974.16
 6239.3610530.2314766.3518804.2527454.2129960.49
River Rch & RM=3211,123,16728.26
 6239.9210531.4914768.4218807.2327458.5629965.81
River Rch & RM=3211,123,16482.35
 6240.56   1053314770.94 18810.927463.9229972.46
River Rch & RM=3211,123,16236.45
 6319.2910693.5915021.7619159.9127973.47 30554.5
River Rch & RM=3211,123,15990.54
 6320.8210697.2715027.9219168.9427986.6530570.99
River Rch & RM=3211,123,15744.64
 6323.7810704.3615039.7819186.2828011.9630602.64
River Rch & RM=3211,123,15498.73
 6325.1310707.59 15045.219194.2128023.5530617.14
River Rch & RM=3211,123,15252.83
  6325.510708.4815046.6819196.3828026.72 30621.1
River Rch & RM=3211,123,15006.92
 6336.6510735.2115091.4819261.9628122.4730740.96
River Rch & RM=3211,123,14761.02
 6337.3310736.9115094.3719266.2228128.6930748.86
River Rch & RM=3211,123,14515.11
 6338.3110739.3215098.4619272.2628137.5130760.04
River Rch & RM=3211,123,14269.21
 6342.0310748.5315114.0919295.34 28171.2 30802.8
River Rch & RM=3211,123, 14023.3
  6356.210782.02 15169.919376.7528290.0630950.61
River Rch & RM=3211,123, 13777.4
 6356.8910783.7215172.79   1938128296.2630958.49
River Rch & RM=3211,123,13531.49
 6357.57 10785.415175.6519385.2428302.4630966.37
River Rch & RM=3211,123,13285.59
 6372.5510822.2215237.9719477.1228436.5931136.14
River Rch & RM=3211,123,13039.68
  6374.310826.6415245.5319488.3328452.9631157.09
River Rch & RM=3211,123,12793.78
 6375.2910829.1315249.7819494.6428462.1731168.88
River Rch & RM=3211,123,12547.87
 6376.3910831.89 15254.519501.6528472.4131181.97
River Rch & RM=3211,123,12255.45
 6380.9610843.3815274.1319530.7428514.8931236.26
River Rch & RM=3211,123,12134.23
 6384.2710851.7615288.4819552.0628546.0131276.15
River Rch & RM=3211,123,12019.89
  6384.610852.5915289.8919554.1628549.0831280.07
River Rch & RM=3211,123, 11778.7
 6385.0810853.82   15292 19557.328553.6631285.95
River Rch & RM=3211,123,11537.52
 6417.8310935.2315430.4919762.2228852.8431666.73
River Rch & RM=3211,123,11296.33
 6418.2110936.1815432.1219764.6528856.3831671.29
River Rch & RM=3211,123,11055.14
 6419.0510938.3415435.8419770.1928864.4731681.69
River Rch & RM=3211,123,10813.96
 6419.5910939.6915438.1619773.6528869.5331688.19
River Rch & RM=3211,123,10572.77
 6427.0910958.8715471.1219822.7628941.2331780.48
River Rch & RM=3211,123,10331.58
 6428.3210961.9815476.4719830.7228952.8631795.42
River Rch & RM=3211,123, 10090.4
 6442.3910997.5215537.3219921.1929084.9431964.75
River Rch & RM=3211,123,9849.209
 6443.4611000.2215541.96 19928.129095.0331977.71
River Rch & RM=3211,123,9608.022
 6444.63 11003.215547.07 19935.729106.1331991.96
River Rch & RM=3211,123,9125.648
 6446.0711006.8615553.3419945.0429119.7532009.46
River Rch & RM=3211,123,8560.474
 6476.1411082.9215683.7620139.1729403.1932373.32
River Rch & RM=3211,123,  7970.8
 6491.4711121.5515749.9120237.5929546.8832557.54
River Rch & RM=3211,123,7678.527
 6493.4711126.5615758.4920250.3329565.4832581.34
River Rch & RM=3211,123, 7437.34
 6494.2811128.5915761.9620255.4829573.0132590.99
River Rch & RM=3211,123,7196.154
 6495.0911130.6215765.4320260.6529580.5432600.64
River Rch & RM=3211,123,6954.967
 6499.4111141.4615783.9520288.1829620.7432652.07
River Rch & RM=3211,123,5469.467
 6513.3811176.5815844.11 20377.729751.4432819.65
Boundary for River Rch & Prof#=3211,123,1
Up Type= 0
Dn Type= 2
Boundary for River Rch & Prof#=3211,123,2
Up Type= 0
Dn Type= 2
Boundary for River Rch & Prof#=3211,123,2
Up Type= 0
Dn Type= 2
Boundary for River Rch & Prof#=3211,123,2
Up Type= 0
Dn Type= 2
Boundary for River Rch & Prof#=3211,123,2
Up Type= 0
Dn Type= 2
Boundary for River Rch & Prof#=3211,123,2
Up Type= 0
Dn Type= 2

--- 3211_ras.g01 (geometry) ---

Geom Title=3211
Program Version=4.10

River Reach=3211,123
Reach XY= 30
619088.260991097756535.808573372619524.910369428755490.755995192
619553.303913592754188.469206231618646.033872395753079.295934442
617913.478108349752647.474947188617823.876537174752061.906450114
618066.002968819751176.081878125618785.077043444751007.559092289
619290.498704463749849.182488812619268.822328866749253.089808139
619875.955700576748603.158701222619226.716052474746737.959045104
620859.985427709746066.670687716 620547.76940179745132.972706732
620707.465655029742573.068066485619414.777610779741450.645644682
621462.729105562739760.142283004621552.395853966737498.427421893
621304.846501348736519.116925311622011.510565429735334.881596513
622087.086065083733681.586497669622428.599063964732877.858226591
621065.342788934731835.439640766620411.824873357731920.469239423
619880.283677606731579.322312322619941.456671953 730171.30238438
619124.924880741729596.155419831618378.956671864728294.132245501
618371.361185789727163.489884396 618899.52660358 727154.14482136

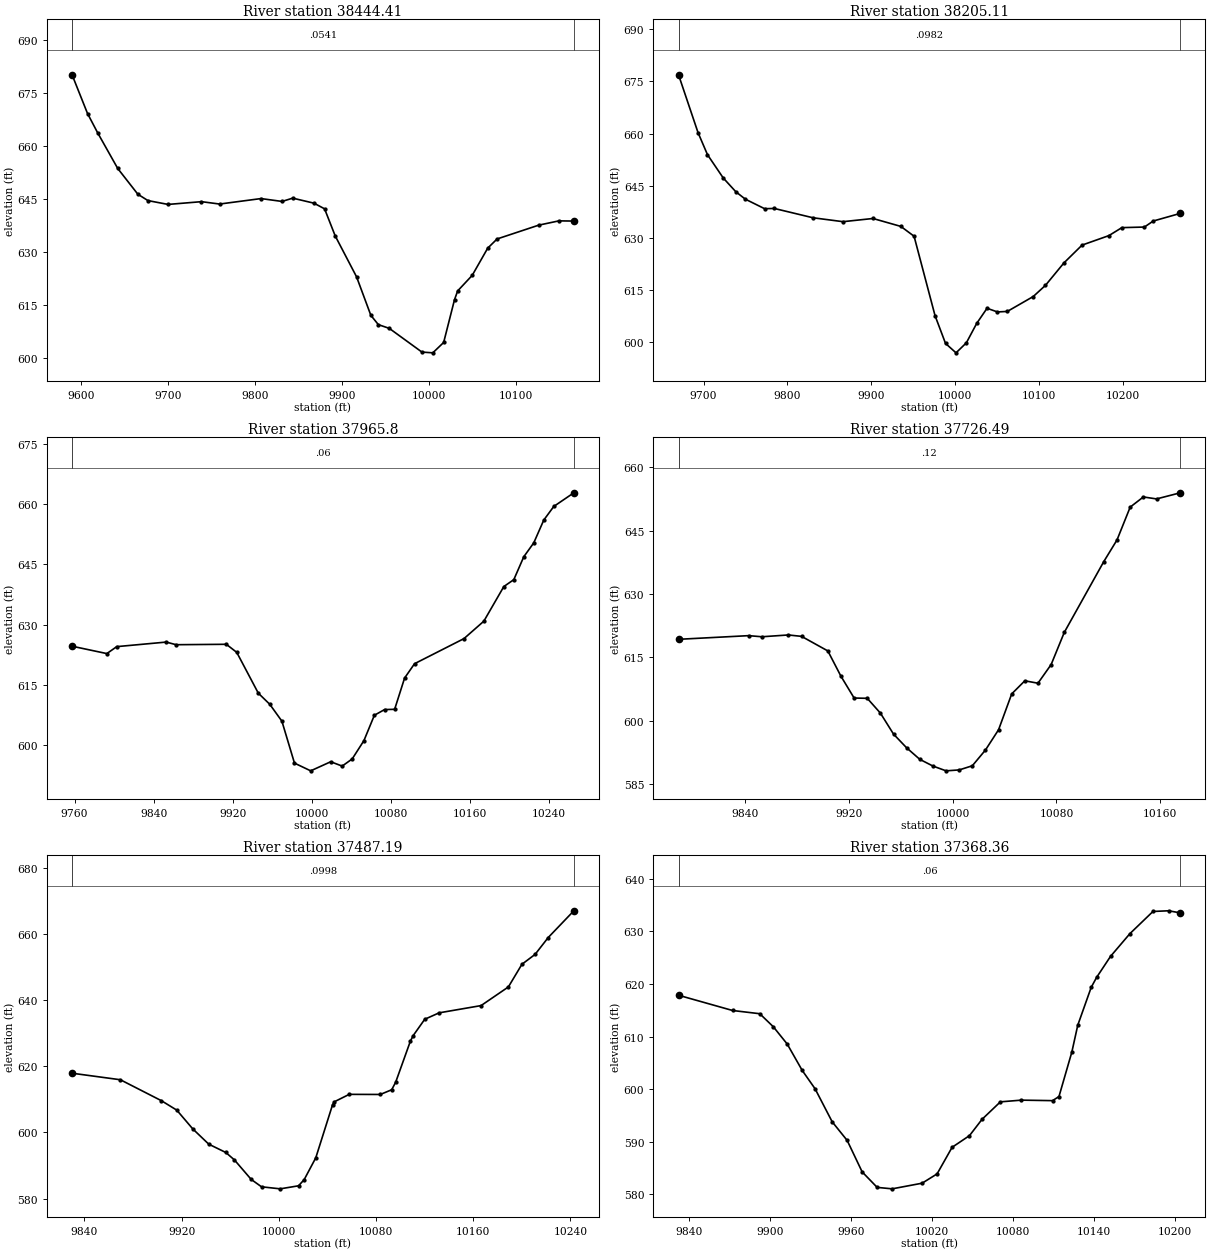
Type RM Length L Ch R = 1 ,38444.41,239.306600,239.306600,239.306600
XS GIS Cut Line= 6
619430.345367361756761.223601686619329.633776243756702.439085959
619239.162913409756644.217949166619159.029007768756587.928264588
619048.792532314756505.073180271618950.211834704756442.120247044
#Sta/Elev= 30
9590.005680.02629607.773669.07529619.352663.64829642.509653.53559665.667646.2479
9677.246644.45029700.404643.36559738.842644.14539759.694643.47419807.261645.0197
9831.511644.21079843.731645.14249868.172643.72099880.393642.12059892.614634.4634
9917.177622.88929933.607612.00289942.224609.37149954.747608.32729992.318601.6147
10004.85601.397510017.33 604.33310029.81616.430710033.44618.910810050.16623.3029
10067.98630.995410078.78633.600810126.69637.5081 10149.9638.716110167.06638.6616
#Mann= 3 , 0 , 0
9590.005  0.0541       09590.005  0.0541       010167.06  0.0541       0
#XS Ineff= 2 , 0
       0                               0
Bank Sta=9590.005,10167.06
Exp/Cntr=0.3,0.1

Type RM Length L Ch R = 1 ,38205.11,239.306500,239.306500,239.306500
XS GIS Cut Line= 6
619515.588781792756519.700594159619377.187222923756444.091147213
619297.817199206756392.641831974 619191.30860416756314.006308289
619155.213580451756293.323250732618994.286352371756233.147822632
#Sta/Elev= 30
9670.199676.92799693.432660.30669704.716653.9527 9723.51647.25379738.569643.2851
9749.853641.16679772.817638.42599784.346638.49649830.543635.81739866.295634.6945
9902.046635.61129935.263 633.334 9951.04630.50999976.036607.67919988.534 599.695
10001.06596.986310013.39599.868710025.71605.451310038.04609.798810050.37608.7482
10062.19608.887310093.15613.181310107.73616.400710129.69622.835910151.33627.9609
 10183.3630.686910198.78632.982510225.67633.150110236.19634.882510268.49637.0817
#Mann= 3 , 0 , 0
9670.199  0.0982       09670.199  0.0982       010268.49  0.0982       0
#XS Ineff= 2 , 0
       0                               0
Bank Sta=9670.199,10268.49
Exp/Cntr=0.3,0.1

Type RM Length L Ch R = 1 , 37965.8,239.306600,239.306600,239.306600
XS GIS Cut Line= 6
619500.060929925756101.758418981619415.332877657756097.719529948
619340.976516565756109.070223002619199.993984098756184.044538595
619111.147069217756185.923141573619015.153409761756170.072399162
#Sta/Elev= 30
9757.448624.65669792.649622.82749802.676624.55279852.724625.6843 9862.77625.0315
9913.592625.13419924.142623.13249945.966612.99389957.562610.2324 9969.84606.0441
9982.581595.6178    9999593.700610019.27595.959210030.87594.8813   10041596.6541
10052.89601.210710063.46607.508810073.77608.917410083.97 608.98510094.05616.7507
10104.13620.311610154.18626.547210174.28630.8783 10194.5639.477510204.61641.1927
10214.72646.884110224.84650.345510234.95655.995810245.08659.377410265.39662.7696
#Mann= 3 , 0 , 0
9757.448    0.06       09757.448    0.06       010265.39    0.06       0
#XS Ineff= 2 , 0
       0                               0
Bank Sta=9757.448,10265.39
Exp/Cntr=0.3,0.1

Type RM Length L Ch R = 1 ,37726.49,239.306600,239.306600,239.306600
XS GIS Cut Line= 6
619488.009637569755957.142910786  619395.2495132755938.932567282
619280.978772412 755921.30531373619278.998315957755921.026401142
619214.484360394755911.279176222619106.944974398755892.611533357
#Sta/Elev= 30
9788.847619.29669842.868620.16069853.059619.89769873.441620.3233 9883.63619.9912
9903.867 616.5489913.985610.56049924.103605.42369934.222 605.357 9944.34601.8658
9954.458596.90459964.576593.65559974.695590.94029984.813589.35569994.931588.2235
10005.04588.438210015.16 589.42310025.27593.136210035.38597.9332 10045.5606.3997
10055.61609.494810065.72608.925110075.87613.328910086.02620.943910116.47637.6778
10126.62642.773710136.77650.528510146.92652.925910157.07652.460610175.39653.9131
#Mann= 3 , 0 , 0
9788.847    0.12       09788.847    0.12       010175.39    0.12       0
#XS Ineff= 2 , 0
       0                               0
Bank Sta=9788.847,10175.39
Exp/Cntr=0.3,0.1

Type RM Length L Ch R = 1 ,37487.19,118.822900,118.822900,118.822900
XS GIS Cut Line= 6
 619455.48688823755796.385857865619362.966276735755728.136321962
 619311.92605105755672.106959373619252.216570765755620.815581217
619211.595006794755595.084043011619125.500664523755555.134166865
#Sta/Elev= 30
9829.894617.87399869.639615.89929903.388609.57179916.057606.71749929.217601.0459
9942.377596.43359956.398593.92469963.506591.6674 9977.29585.7857 9985.78583.5545
10001.16582.940510016.25583.861210020.89585.732310030.42592.314410044.19608.3038
10045.77609.260610057.96611.4878 10083.5611.451710092.88612.876810096.17615.1653
10108.24627.536310110.56629.236410120.07634.170810131.91636.114410166.42638.3037
10188.89643.937910200.04650.783510210.86653.771610221.68658.869910242.77666.9491
#Mann= 3 , 0 , 0
9829.894  0.0998       09829.894  0.0998       010242.77  0.0998       0
#XS Ineff= 2 , 0
       0                               0
Bank Sta=9829.894,10242.77
Exp/Cntr=0.3,0.1

Type RM Length L Ch R = 1 ,37368.36,60.269000,60.269000,60.269000
XS GIS Cut Line= 4
619475.009240299755784.751470342619464.946929723755706.936268046
619393.197034329 755559.06148383619300.447169662755468.936615333
#Sta/Elev= 30
9832.136617.85799872.219614.95469892.385614.34139902.469611.84779912.752608.5626
9923.867603.54279933.386600.05599946.097593.75599957.212590.21229968.327584.2182
9979.442581.27279990.557580.995110012.79582.0694 10023.9583.844210035.02588.9043
10047.92591.127110057.25594.237410070.83597.559510086.39597.885710109.49 597.789
10114.28598.565410123.84607.050210128.22612.150310138.19619.363610142.17621.2435
10152.54625.266410166.89629.5871   10184633.813510195.59633.943210204.29 633.542
#Mann= 3 , 0 , 0
9832.136    0.06       09832.136    0.06       010204.29    0.06       0
#XS Ineff= 2 , 0
       0                               0
Bank Sta=9832.136,10204.29
Exp/Cntr=0.3,0.1

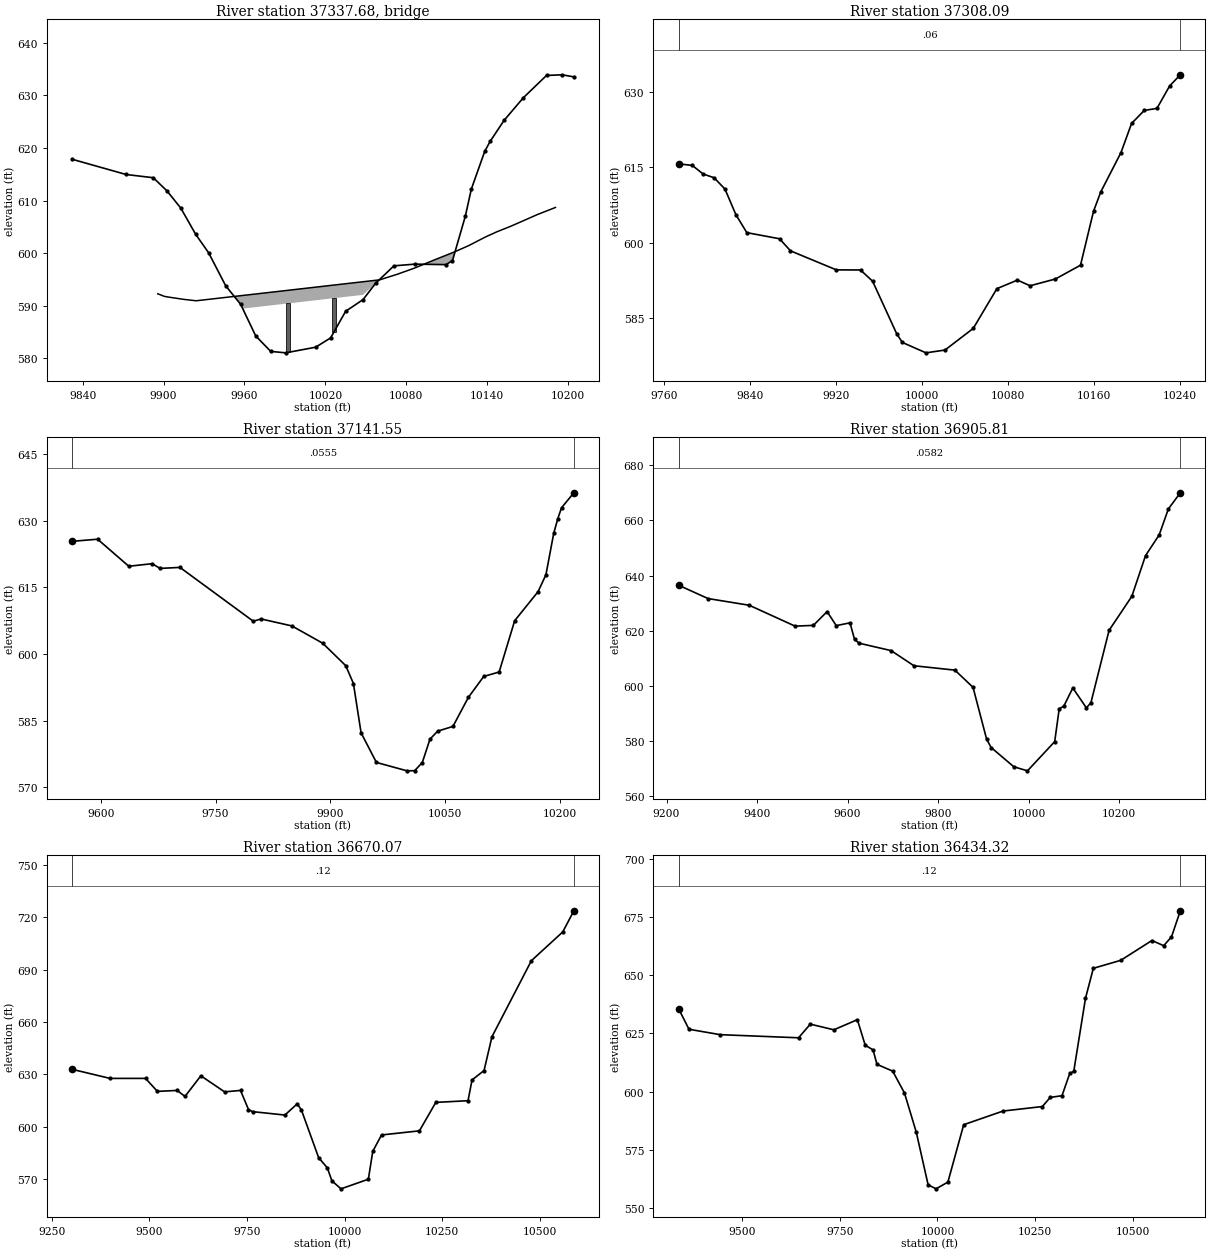
Type RM Length L Ch R = 3 ,37337.68,,,
BEGIN DESCRIPTION:
END DESCRIPTION:
Bridge Culvert--1,0,-1,-1, 0
Deck Dist Width WeirC Skew NumUp NumDn MinLoCord MaxHiCord MaxSubmerge Is_Ogee
16.134500,28.000000,2.6,0, 30, 30, , , 0.95, 0, 0,0,,
 9895.69 9900.71 9903.72 9914.90 9923.07 9924.16 9959.72 9959.7210058.7210058.72
10060.2810063.4210067.2910074.1310074.8410085.1510095.4610101.4210105.7710116.07
10126.3810136.6910140.2210143.9310146.8810157.0110167.1410177.2710187.4010190.63
  592.24  591.74  591.61  591.18  590.94  590.91  591.95  591.95  594.85  594.85
  594.90  595.15  595.47  596.02  596.10  597.04  598.12  598.75  599.19  600.25
  601.42  602.79  603.24  603.66  604.01  605.05  606.18  607.33  608.35  608.68
 -407.76 -408.26 -408.39 -408.82 -409.06 -409.09 -408.05  589.45  592.35 -405.15
 -405.10 -404.85 -404.53 -403.98 -403.90 -402.96 -401.88 -401.25 -400.81 -399.75
 -398.58 -397.21 -396.76 -396.34 -395.99 -394.95 -393.82 -392.67 -391.65 -391.32
 9895.69 9900.71 9903.72 9914.90 9923.07 9924.16 9957.93 9957.9310056.9310056.93
10060.2810063.4210067.2910074.1310074.8410085.1510095.4610101.4210105.7710116.07
10126.3810136.6910140.2210143.9310146.8810157.0110167.1410177.2710187.4010190.63
  592.24  591.74  591.61  591.18  590.94  590.91  591.90  591.90  594.80  594.80
  594.90  595.15  595.47  596.02  596.10  597.04  598.12  598.75  599.19  600.25
  601.42  602.79  603.24  603.66  604.01  605.05  606.18  607.33  608.35  608.68
 -407.76 -408.26 -408.39 -408.82 -409.06 -409.09 -408.10  589.40  592.30 -405.20
 -405.10 -404.85 -404.53 -403.98 -403.90 -402.96 -401.88 -401.25 -400.81 -399.75
 -398.58 -397.21 -396.76 -396.34 -395.99 -394.95 -393.82 -392.67 -391.65 -391.32
Pier Skew, UpSta & Num, DnSta & Num=  ,9992.22, 2 ,9990.43, 2 , 0 , 0 , 0 ,,
    3.00    3.00
 -407.10  592.90
    3.00    3.00
 -407.15  592.85
Pier Skew, UpSta & Num, DnSta & Num=  ,10026.22, 2 ,10024.43, 2 , 0 , 0 , 0 ,,
    3.00    3.00
 -406.10  593.90
    3.00    3.00
 -406.15  593.85
BR Coef=-1 , 0 , 0 ,, 0 ,,,0.8,0,1,0,
WSPro=,,,, 1 ,,,, 0 ,,,, 0 ,,,,-1 ,-1 ,-1 , 0 , 0 , 0 , 0 , 0
BC Design=,, 0 ,, 0 ,,,,,,

Type RM Length L Ch R = 1 ,37308.09,166.542300,166.542300,166.542300
XS GIS Cut Line= 4
619544.571813583 755807.56112124619522.696845502755684.186301246
619437.821969211755517.936543852619306.572160751755435.686663866
#Sta/Elev= 30
 9773.28615.68339786.037615.38229796.193613.65879806.349612.92019816.505610.6481
9826.661605.54379836.817601.96659867.285600.74549877.441 598.3369920.121 594.542
9942.577594.52119953.804592.2867 9976.26581.80089981.484580.073610003.48577.9965
10021.17578.552610047.46582.866810069.45 590.79210088.57592.503410100.37591.3715
10123.98592.728310147.27595.477310159.38606.2353 10166.1610.087710184.93617.9391
10194.78623.747610206.58626.339910218.39626.751610230.19631.225710240.13633.4517
#Mann= 3 , 0 , 0
 9773.28    0.06       0 9773.28    0.06       010240.13    0.06       0
#XS Ineff= 2 , 0
       0                               0
Bank Sta=9773.28,10240.13
Exp/Cntr=0.3,0.1

Type RM Length L Ch R = 1 ,37141.55,235.743600,235.743600,235.743600
XS GIS Cut Line= 6
619957.668282234755503.101802806 619712.66036424755456.092277735
619569.858329028755440.936898738619465.578045219755437.307610318
619398.229664475755429.258387938619309.344545096 755410.23686716
#Sta/Elev= 30
9562.273625.39389595.672625.8693 9636.48619.77289667.071620.35869677.268619.2874
9703.326619.51939799.261607.38949809.406   607.99849.752  606.339890.083 602.428
9920.181597.37239930.211593.35549940.241582.2384 9960.29575.567910000.31573.6752
10010.32  573.7110020.32575.552610030.33580.810310040.34582.613310060.36583.6835
 10080.5590.214910100.64 594.94710120.78595.940610141.12607.509110171.76614.0664
10181.98617.863910192.19627.206310197.45630.470310202.41632.967510218.51636.3329
#Mann= 3 , 0 , 0
9562.273  0.0555       09562.273  0.0555       010218.51  0.0555       0
#XS Ineff= 2 , 0
       0                               0
Bank Sta=9562.273,10218.51
Exp/Cntr=0.3,0.1

Type RM Length L Ch R = 1 ,36905.81,235.743500,235.743500,235.743500
XS GIS Cut Line= 6
620219.327906012755302.553253497619843.088238938755244.358567398
619618.308568593755216.535542108619540.133348656 755211.61263597
619337.465002005755220.690574455619118.888882029 755196.85066574
#Sta/Elev= 30
9226.587636.51439291.711631.66749382.825629.23239484.009621.66069524.462621.9223
9554.802 626.9379575.029621.83159605.369622.86039615.464616.83399625.555615.4602
9696.192612.77499746.598607.2845 9837.13605.69089877.209599.44919907.268580.6069
9917.279577.60219967.319570.62829997.441569.148110057.61579.745210067.62 591.701
10077.63592.570710097.63599.226510127.65591.992510137.66593.884410177.76620.1339
10228.07632.481810258.26 647.22910288.54654.797110308.76664.188610335.17670.0473
#Mann= 3 , 0 , 0
9226.587  0.0582       09226.587  0.0582       010335.17  0.0582       0
#XS Ineff= 2 , 0
       0                               0
Bank Sta=9226.587,10335.17
Exp/Cntr=0.3,0.1

Type RM Length L Ch R = 1 ,36670.07,235.743600,235.743600,235.743600
XS GIS Cut Line= 6
620231.396651773755170.299914507619725.956107899755086.921778773
619650.437719809755061.681206287619371.859348394 754924.72874617
 619218.60355396754886.559189225618996.590197044754862.612609283
#Sta/Elev= 30
9302.294632.81089399.561627.6054 9490.48627.60549520.786620.16459571.296620.6999
9591.517 617.272 9632.09629.0958 9692.95619.87719733.679620.70849754.091609.7532
9764.367608.56149847.232606.59939878.982613.03359889.652609.48349933.761582.1543
9955.975576.34589967.649568.89999990.998 564.30910061.04569.822710072.38 585.805
10094.82595.192310191.83597.549210233.76613.852910316.32 614.82310326.56626.7349
10357.28632.091810377.59651.500810478.56695.064110558.87711.554810587.31723.6732
#Mann= 3 , 0 , 0
9302.294    0.12       09302.294    0.12       010587.31    0.12       0
#XS Ineff= 2 , 0
       0                               0
Bank Sta=9302.294,10587.31
Exp/Cntr=0.3,0.1

Type RM Length L Ch R = 1 ,36434.32,235.743500,235.743500,235.743500
XS GIS Cut Line= 6
 620261.66742131754838.582731592 619807.84821364754808.365987073
619302.843554761754747.649055428619203.832661339754740.570556846
619071.753904934754737.741756818618982.396378015754740.782329301
#Sta/Elev= 30
9337.274635.69889363.979 626.805 9444.11624.48139644.503623.14719674.592629.0048
9734.784626.57579794.981630.92189815.073  619.979835.166617.93939845.212611.7343
9885.398608.81969915.543599.45189945.781582.59269976.077560.02079996.348 558.259
10026.71561.146510067.18585.812910167.91591.675210268.53 593.60810288.65597.5339
10318.77598.262810338.82607.922810348.85608.686510378.93640.103310398.98652.9952
   10469656.403910549.02664.932910579.04662.703810599.05666.479110621.67677.7036
#Mann= 3 , 0 , 0
9337.274    0.12       09337.274    0.12       010621.67    0.12       0
#XS Ineff= 2 , 0
       0                               0
Bank Sta=9337.274,10621.67
Exp/Cntr=0.3,0.1

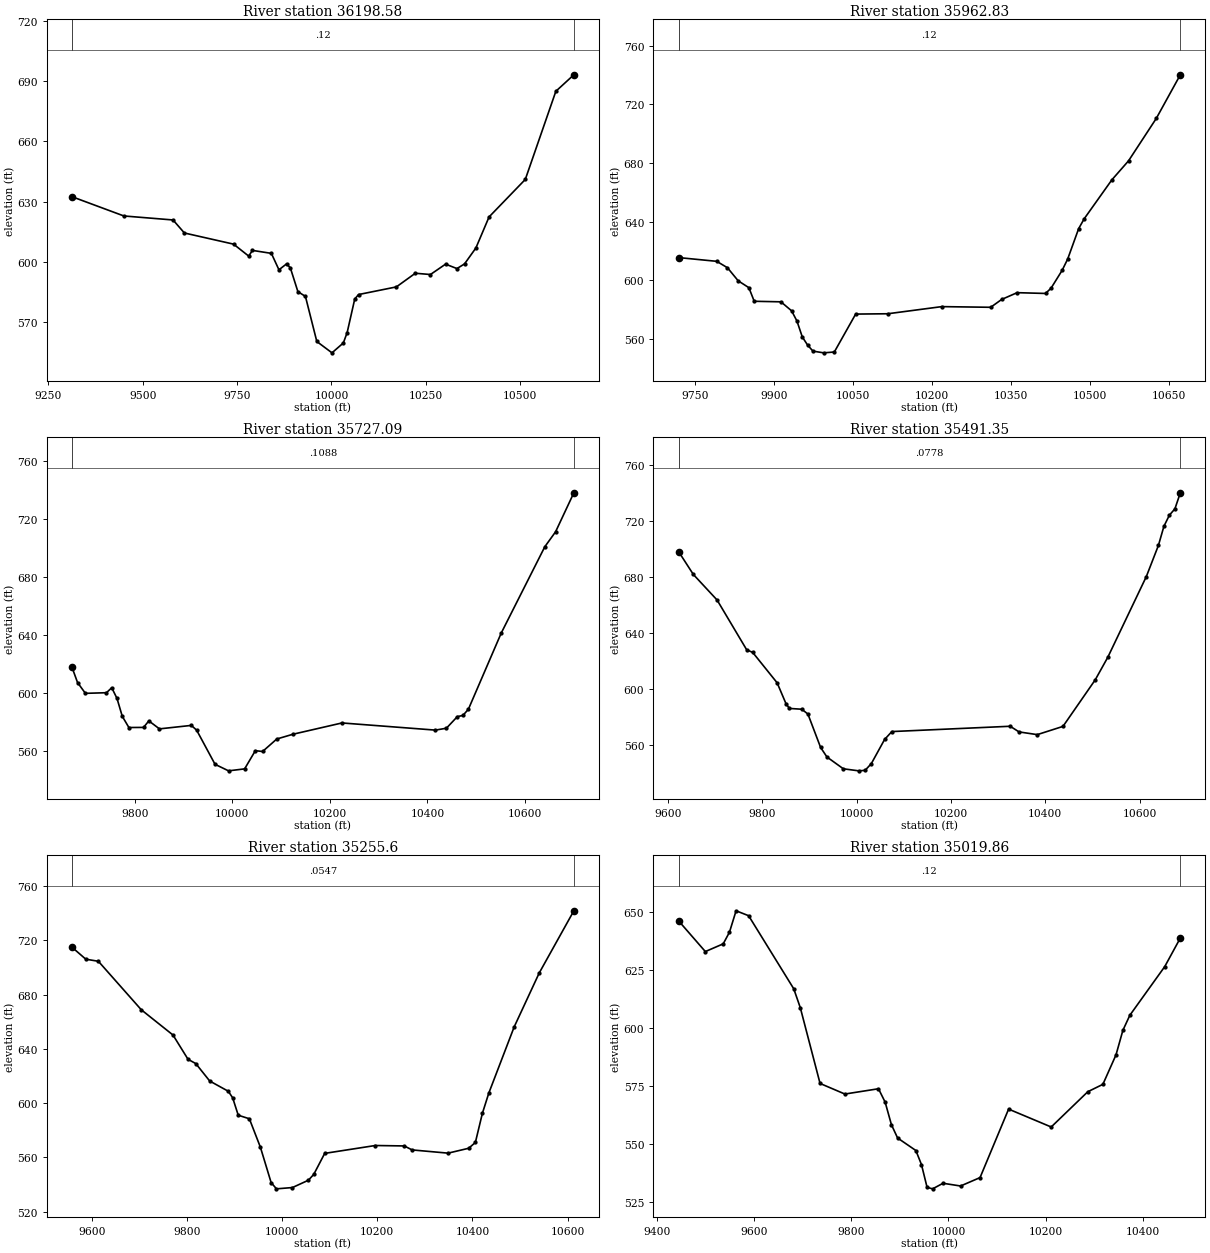
Type RM Length L Ch R = 1 ,36198.58,235.743600,235.743600,235.743600
XS GIS Cut Line= 6
 620292.07104831754505.409652324619766.844176187754536.692139196
619510.138861777754559.255333583619276.439326373754576.505012603
619076.309256607754598.900713387618967.866124209754616.064317482
#Sta/Elev= 30
9312.692632.44619449.969 622.8849580.213620.8954 9610.27614.41659740.514608.8777
9780.589602.93869790.607605.75899840.703604.29069860.762 596.1239880.822599.0383
9890.851597.15279910.911585.2852 9930.97 582.8679961.101560.465810001.28554.8264
10031.41559.745710041.46 564.89810061.54581.561510071.59583.8069 10171.9587.6138
10222.04594.399110262.15593.775110302.25598.934910332.34596.727510352.44599.0479
10382.58606.981510417.44622.410410513.45641.057910594.37684.883710642.09693.0891
#Mann= 3 , 0 , 0
9312.692    0.12       09312.692    0.12       010642.09    0.12       0
#XS Ineff= 2 , 0
       0                               0
Bank Sta=9312.692,10642.09
Exp/Cntr=0.3,0.1

Type RM Length L Ch R = 1 ,35962.83,235.743500,235.743500,235.743500
XS GIS Cut Line= 6
619856.352757659754267.533967562619738.207827232 754289.47440565
619441.203686115754340.490105992619311.982219532754370.748100403
619190.290279513754405.387788882618931.651032236754489.414598765
#Sta/Elev= 30
9719.374615.41959791.947612.85629812.289608.47089832.631599.55739852.932594.8595
9863.072585.57829913.773585.20229934.053  579.069944.193572.08419954.333561.2413
9964.473555.64569974.613551.54049994.893550.369410015.16550.941610055.69 576.834
10116.69577.057310219.17581.927510312.07581.472110332.87 586.82410362.21591.4527
10416.19590.916910426.68594.541810447.66606.668410458.15614.352910479.13635.2443
10489.62 641.93310542.11668.491110573.73681.453210626.42710.4195 10672.1740.2369
#Mann= 3 , 0 , 0
9719.374    0.12       09719.374    0.12       0 10672.1    0.12       0
#XS Ineff= 2 , 0
       0                               0
Bank Sta=9719.374,10672.1
Exp/Cntr=0.3,0.1

Type RM Length L Ch R = 1 ,35727.09,235.743600,235.743600,235.743600
XS GIS Cut Line= 6
619820.315121467753960.767326481619531.770348458754083.021474788
619430.034677713754129.287687122619348.352958396754168.615554954
619042.129189153754327.691560776618891.052430431754401.014417417
#Sta/Elev= 30
9671.406617.74689682.624607.38959698.742599.94819741.934600.38039752.732603.8182
 9763.53596.44349774.341584.14299787.885576.42559817.907576.49049828.798580.9809
9850.581575.4893 9915.93577.87659926.821574.60059964.551551.09179992.237546.5971
 10025.2547.950810047.17560.482910062.01559.9125 10091.1568.507410124.34571.7938
 10224.8579.565310416.37 574.63410438.91575.939910461.38583.942610472.71584.7229
10483.98588.999510551.41641.514210640.71 700.886 10662.8711.185910700.23738.0191
#Mann= 3 , 0 , 0
9671.406  0.1088       09671.406  0.1088       010700.23  0.1088       0
#XS Ineff= 2 , 0
       0                               0
Bank Sta=9671.406,10700.23
Exp/Cntr=0.3,0.1

Type RM Length L Ch R = 1 ,35491.35,235.743500,235.743500,235.743500
XS GIS Cut Line= 6
619681.882797147753657.125656319619547.833704717753755.268982716
619464.508397576753825.151121273619120.179435678754139.508787829
 618985.33807542754240.338161876 618855.12996394754322.796143604
#Sta/Elev= 30
9622.602698.16179653.961681.82089704.293663.60719767.187628.05199779.766626.2704
9831.633  604.57 9850.61589.55239857.735586.30639883.838585.74459896.889582.3107
 9923.79558.51469937.251551.68849971.999543.289210004.56541.8294 10018.1542.1762
 10031.3546.954510059.46564.186510074.84569.818610325.76573.604110344.53569.5695
10383.16 567.63810437.63573.508410506.01606.684510532.69622.788810614.38680.3201
10639.95 702.47510651.67716.160510663.31724.104710674.94728.564710686.43740.0234
#Mann= 3 , 0 , 0
9622.602  0.0778       09622.602  0.0778       010686.43  0.0778       0
#XS Ineff= 2 , 0
       0                               0
Bank Sta=9622.602,10686.43
Exp/Cntr=0.3,0.1

Type RM Length L Ch R = 1 , 35255.6,235.743600,235.743600,235.743600
XS GIS Cut Line= 6
619476.482084491753416.121294194619278.247232954753623.533521166
 619138.91333448753868.660870395619054.738672219753987.153819083
618940.955048619 754108.47096248618807.119501329754218.257233081
#Sta/Elev= 30
9558.313714.86269587.236706.08149613.598704.56679703.799668.81579770.529650.1715
9802.104632.29459818.468629.11899847.672616.28249886.773608.72329895.942603.8925
9907.645591.06459931.051588.44399954.276 567.4369976.743541.45919987.976536.7881
10021.54537.737310055.06543.119710066.41547.431210089.43562.933310195.83568.7351
10256.71568.413710273.17 565.48210348.85563.101510392.11566.701310406.18570.9974
10420.88592.418110434.33607.302210487.77 656.19410540.43695.951610613.22741.7891
#Mann= 3 , 0 , 0
9558.313  0.0547       09558.313  0.0547       010613.22  0.0547       0
#XS Ineff= 2 , 0
       0                               0
Bank Sta=9558.313,10613.22
Exp/Cntr=0.3,0.1

Type RM Length L Ch R = 1 ,35019.86,235.743500,235.743500,235.743500
XS GIS Cut Line= 6
619377.231794193753251.133798636619215.815843601753383.948551445
 619059.51055734753536.577837408619006.075627168753613.175765941
618923.258010143753775.604632332618700.529765565754016.821559845
#Sta/Elev= 30
 9444.24646.05789499.435632.78619536.265636.11789549.114641.13219562.747650.3663
 9588.55648.24069681.493616.74729695.023608.57739735.683575.94369786.799571.3832
9855.979573.66129869.734567.87529882.626558.17429895.352552.43399932.969547.0427
9944.525540.9663 9956.08531.15429967.482530.52559988.906532.9263   10025531.7493
10065.15535.373910123.95 564.88710211.68557.180410287.03572.380910318.12575.5713
10345.14588.281410359.25598.820110373.62605.337610445.47626.307710477.57638.6288
#Mann= 3 , 0 , 0
 9444.24    0.12       0 9444.24    0.12       010477.57    0.12       0
#XS Ineff= 2 , 0
       0                               0
Bank Sta=9444.24,10477.57
Exp/Cntr=0.3,0.1

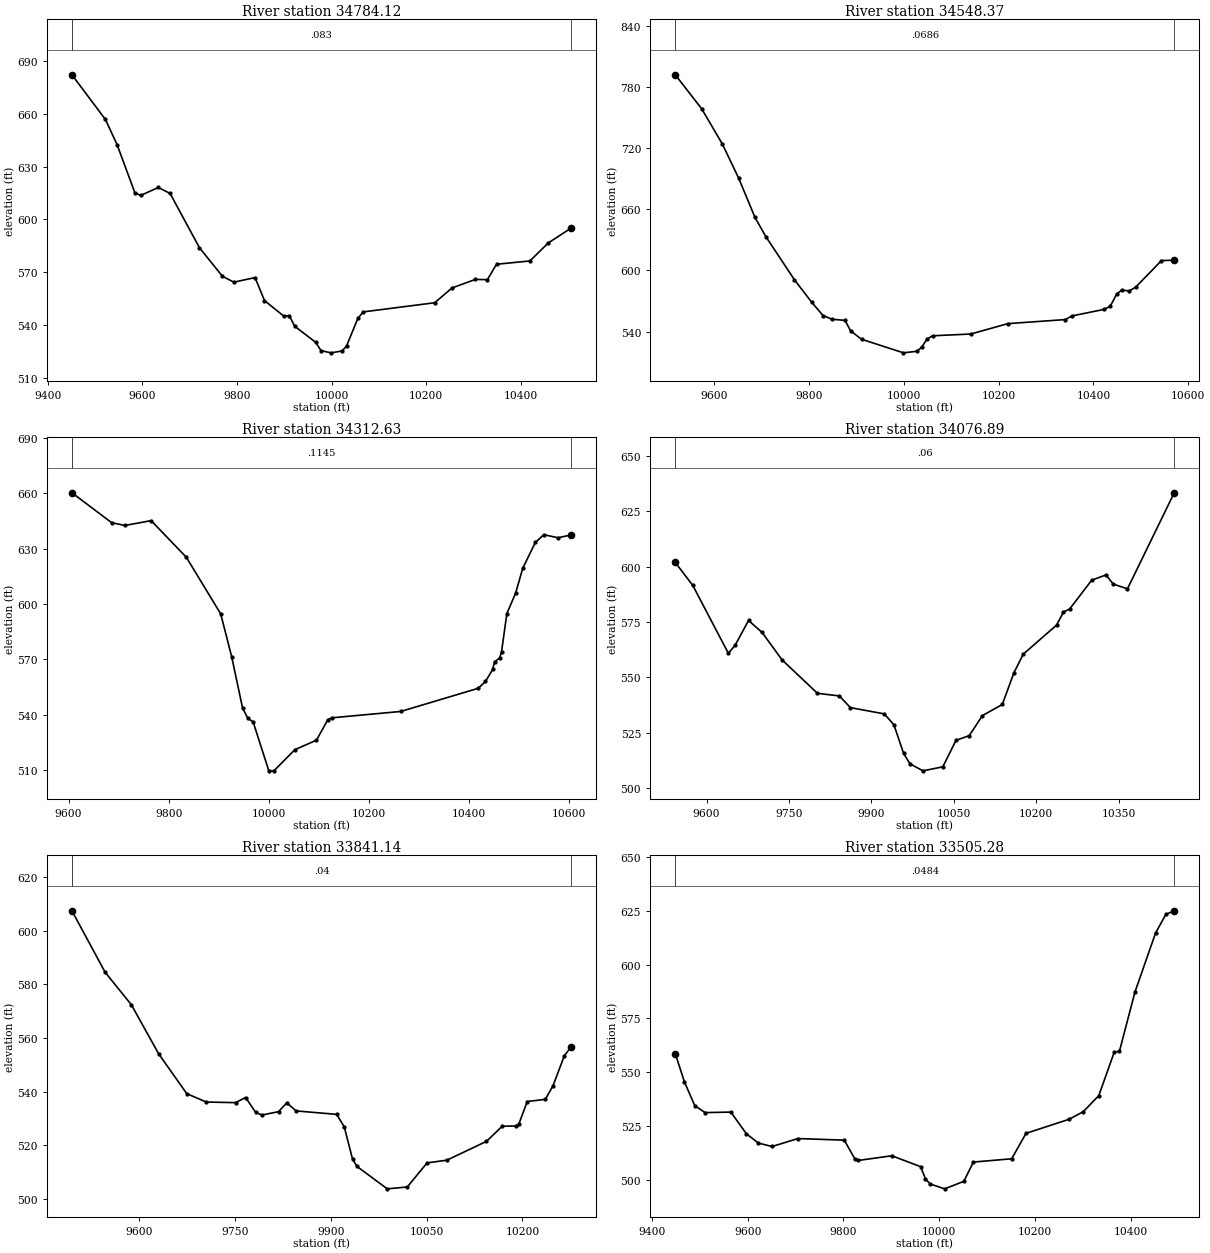
Type RM Length L Ch R = 1 ,34784.12,235.743600,235.743600,235.743600
XS GIS Cut Line= 6
619321.980166896753159.286937674619015.009648702753380.718131733
618936.841557462753425.907660435618770.385393335753508.890926805
618669.603809757753571.044761796618448.090991383 753744.59524932
#Sta/Elev= 30
 9451.18682.20049522.001656.77259546.859642.30179584.147615.15659596.576613.5707
9633.863618.11249658.722614.68449720.867583.78549769.351 567.6019793.511 564.241
9838.296566.84859858.277553.79599899.057544.88989910.608545.23319922.084539.1737
9966.674529.99999977.822525.2762    9999524.041710022.32525.110210031.68527.8863
10055.72543.7029   10067547.326710218.04552.528410254.78560.9653 10304.2565.8057
10329.48565.665110348.76 574.42410419.38576.309310458.21586.565310505.99594.9053
#Mann= 3 , 0 , 0
 9451.18   0.083       0 9451.18   0.083       010505.99   0.083       0
#XS Ineff= 2 , 0
       0                               0
Bank Sta=9451.18,10505.99
Exp/Cntr=0.3,0.1

Type RM Length L Ch R = 1 ,34548.37,235.743500,235.743500,235.743500
XS GIS Cut Line= 6
619160.589299598752987.210447588 618930.46673018753148.890588308
618704.978494538753281.914970753618637.777419394753326.323991387
618535.326150965753409.466194736618315.093271655753609.670691365
#Sta/Elev= 30
9517.228 792.289 9573.27758.65849616.593724.27939650.982690.77339685.371652.2164
9708.449633.22539768.852590.78039804.925568.94359829.009555.72299847.955552.0634
9875.567 550.9329887.341540.64149910.516532.3638    9999 519.03910026.57520.5607
 10037.2524.360610048.75532.609310060.31535.788310140.88 537.53810219.64 547.758
10340.87551.730710354.39555.297910421.96561.690610435.47564.766410448.99576.8465
10459.48580.589110476.02579.918310489.53583.780710543.59609.704510570.49610.0558
#Mann= 3 , 0 , 0
9517.228  0.0686       09517.228  0.0686       010570.49  0.0686       0
#XS Ineff= 2 , 0
       0                               0
Bank Sta=9517.228,10570.49
Exp/Cntr=0.3,0.1

Type RM Length L Ch R = 1 ,34312.63,235.743600,235.743600,235.743600
XS GIS Cut Line= 6
618827.253764426752736.008819609618678.022555411752927.208552574
618632.439077078753022.672671284618592.733471938753148.363113801
618531.906748686  753250.5387508618264.254477647753542.563483277
#Sta/Elev= 30
9606.803 660.233 9686.04644.07589712.551642.54249764.976645.15749835.411625.3024
9903.992594.67919926.054571.30569947.557543.81599958.235 538.1119968.668536.2782
9999.971509.847910010.33509.735610052.05521.179410095.26526.332910117.89537.4101
10125.61538.428110263.57541.874310418.51554.428810432.86558.122410447.08564.6032
10450.92568.7109 10461.3570.828910464.98574.316710475.52594.840710493.12605.9821
10507.18619.308410532.39633.349610549.39637.546110577.63635.8957 10603.4 637.385
#Mann= 3 , 0 , 0
9606.803  0.1145       09606.803  0.1145       0 10603.4  0.1145       0
#XS Ineff= 2 , 0
       0                               0
Bank Sta=9606.803,10603.4
Exp/Cntr=0.3,0.1

Type RM Length L Ch R = 1 ,34076.89,235.743500,235.743500,235.743500
XS GIS Cut Line= 6
618657.543181655752631.293779161618544.883935179752775.725452272
618409.208000981753001.930389488618320.272802176 753135.35242156
618254.490858922753224.751050969618130.243321079753367.686662357
#Sta/Elev= 30
9542.994 601.8639574.847591.51389639.483 560.8949651.768564.41449676.339575.6767
9700.909570.28849737.328557.88579801.717542.79039841.676541.60869861.655536.3338
9923.412533.49929940.935528.55659958.567515.62939970.306 510.9279993.844507.7932
10029.87509.607910053.91521.571310077.96523.685210102.01532.740210138.08537.7467
10159.42552.1543 10176.3560.4703   10237573.609310249.41579.483910260.66580.8336
10300.85593.869310326.85596.233910339.85592.122710365.86589.954210450.98 633.318
#Mann= 3 , 0 , 0
9542.994    0.06       09542.994    0.06       010450.98    0.06       0
#XS Ineff= 2 , 0
       0                               0
Bank Sta=9542.994,10450.98
Exp/Cntr=0.3,0.1

Type RM Length L Ch R = 1 ,33841.14,335.863500,335.863500,335.863500
XS GIS Cut Line= 6
618553.708741413752489.542889032618475.839111239752560.934448421
618428.204855263752611.231339887618374.541947871752673.280573145
618215.604001731752868.791183025618038.142740428753075.841484621
#Sta/Elev= 30
9494.168607.38899546.126584.49969587.274572.38199630.145554.05519674.095 539.246
9704.586536.13039750.447535.89659766.275537.81479782.129532.22989792.024531.3004
9817.798532.53359830.685535.80769845.545 532.8129908.961531.53419920.894526.8226
 9933.78514.84539940.669512.14059988.231503.783310019.55504.476310050.49 513.449
10081.57514.463410143.59521.476610168.26527.107510190.11527.214710194.43528.0139
10207.51536.317910235.75537.120110247.75542.1205 10265.6 553.37810275.83556.5766
#Mann= 3 , 0 , 0
9494.168    0.04       09494.168    0.04       010275.83    0.04       0
#XS Ineff= 2 , 0
       0                               0
Bank Sta=9494.168,10275.83
Exp/Cntr=0.3,0.1

Type RM Length L Ch R = 1 ,33505.28,58.509600,58.509600,58.509600
XS GIS Cut Line= 5
618322.719943762752340.175204083617970.914840043752481.738213986
617956.898700386 752697.58676371617962.016004324752947.055331334
617778.893727541 753021.35958834
#Sta/Elev= 30
9448.517558.65199467.617545.54549489.176534.52369510.734531.2542 9564.63 531.493
9596.968521.47359622.169517.07479650.864515.5113 9704.76519.19579801.773518.4541
9823.332509.88879831.004509.03269901.151511.20589961.278506.13389971.299500.4541
 9981.32498.093110011.38495.843710051.45499.310210071.46508.276810151.47509.8032
10181.48521.6136 10271.5 528.15710301.13531.680810333.51539.122110365.88559.3206
10376.67559.726510409.05587.205710452.22614.6845 10473.8623.319410491.18624.9848
#Mann= 3 , 0 , 0
9448.517  0.0484       09448.517  0.0484       010491.18  0.0484       0
#XS Ineff= 2 , 0
       09933.889        10091.99       0
Bank Sta=9448.517,10491.18
Exp/Cntr=0.3,0.1