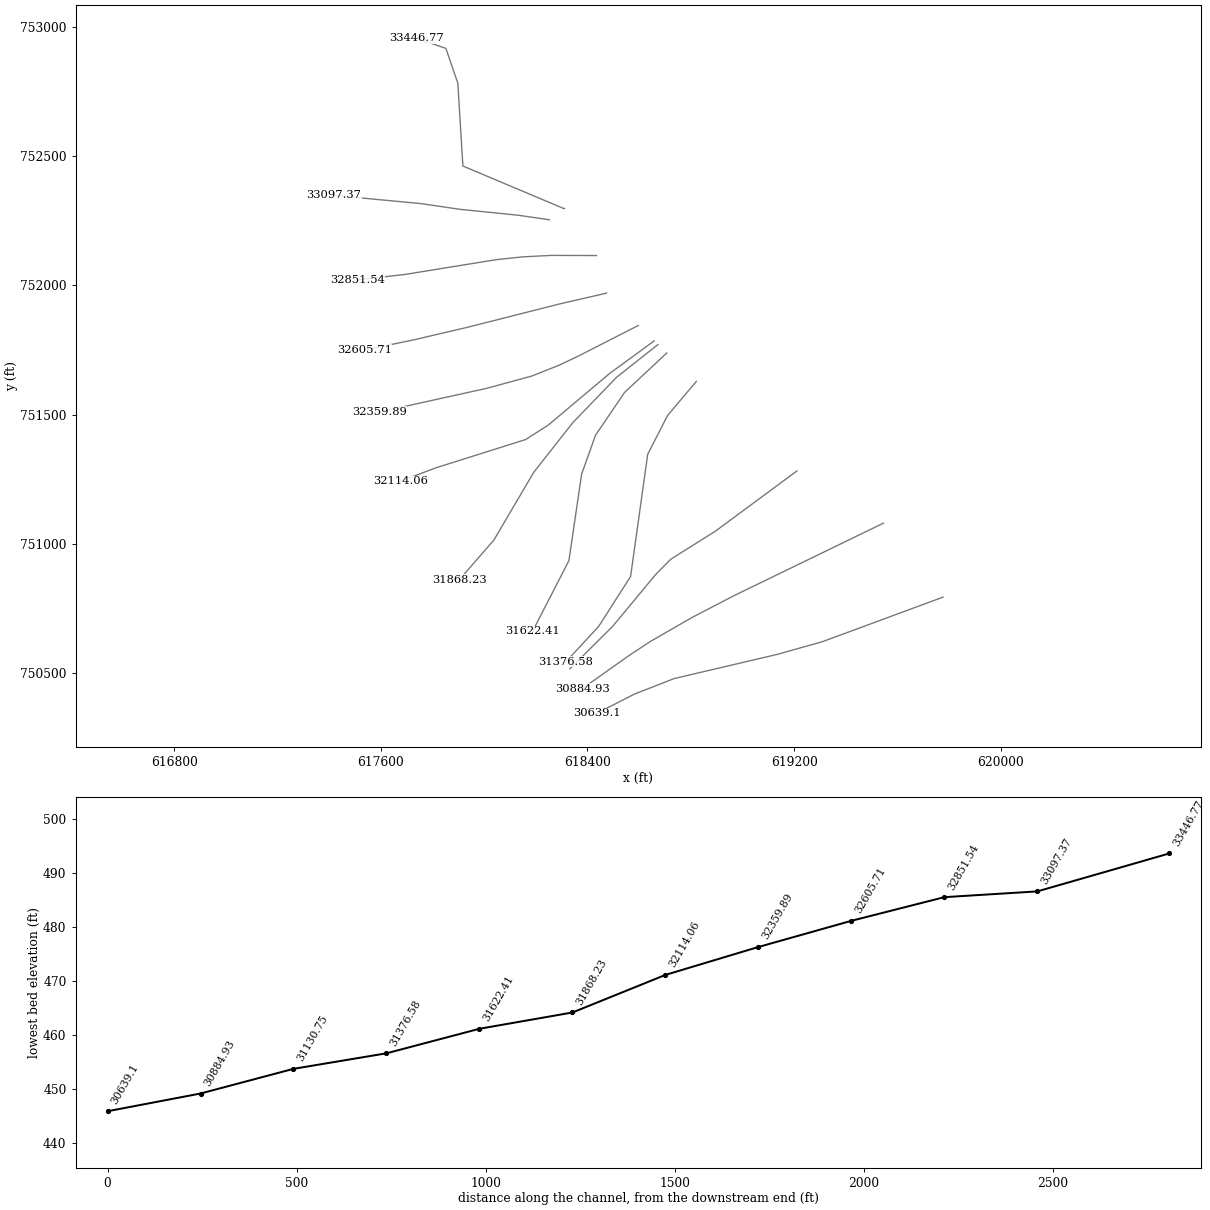
HEC-RAS study 3211_ras.prj: 3211

--- 3211_ras.g01 (geometry) --- (continued)

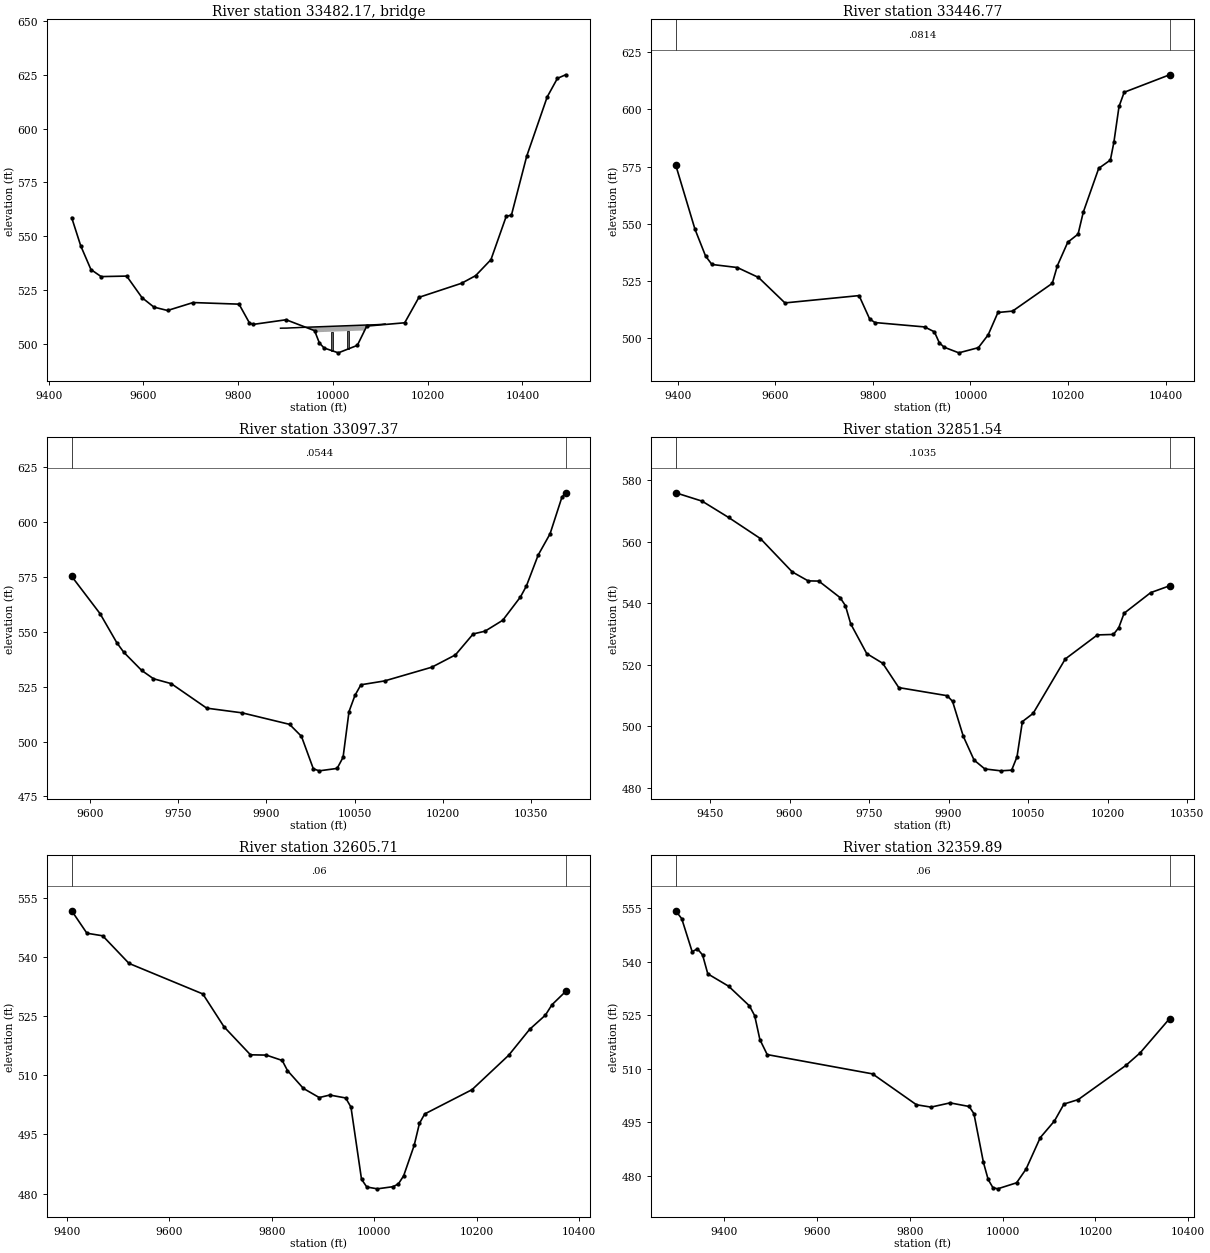
Type RM Length L Ch R = 3 ,33482.17,,,
BEGIN DESCRIPTION:
END DESCRIPTION:
Bridge Culvert--1,0,-1,-1, 0
Deck Dist Width WeirC Skew NumUp NumDn MinLoCord MaxHiCord MaxSubmerge Is_Ogee
16.754800,25.000000,2.6,0, 15, 15, , , 0.95, 0, 0,0,,
 9889.32 9892.57 9902.58 9912.59 9922.60 9930.49 9965.77 9965.7710063.7710063.77
10072.8210082.7310092.7310102.7410110.09
  507.28  507.31  507.33  507.45  507.53  507.62  507.91  507.91  508.71  508.71
  508.78  508.84  508.93  509.07  509.27
 -492.72 -492.69 -492.67 -492.55 -492.47 -492.38 -492.09  505.41  506.21 -491.29
 -491.22 -491.16 -491.07 -490.93 -490.73
 9889.32 9892.57 9902.58 9912.59 9922.60 9930.49 9943.35 9943.3510041.3510041.35
10072.8210082.7310092.7310102.7410110.09
  507.28  507.31  507.33  507.45  507.53  507.62  507.73  507.73  508.52  508.52
  508.78  508.84  508.93  509.07  509.27
 -492.72 -492.69 -492.67 -492.55 -492.47 -492.38 -492.27  505.23  506.02 -491.48
 -491.22 -491.16 -491.07 -490.93 -490.73
Pier Skew, UpSta & Num, DnSta & Num=  ,9997.93, 2 ,9975.51, 2 , 0 , 0 , 0 ,,
    3.00    3.00
 -491.83  508.17
    3.00    3.00
 -492.01  507.99
Pier Skew, UpSta & Num, DnSta & Num=  ,10031.60, 2 ,10009.18, 2 , 0 , 0 , 0 ,,
    3.00    3.00
 -491.55  508.45
    3.00    3.00
 -491.74  508.26
BR Coef=-1 , 0 , 0 ,, 0 ,,,0.8,0,1,0,
WSPro=,,,, 1 ,,,, 0 ,,,, 0 ,,,,-1 ,-1 ,-1 , 0 , 0 , 0 , 0 , 0
BC Design=,, 0 ,, 0 ,,,,,,

Type RM Length L Ch R = 1 ,33446.77,349.404000,349.404000,349.404000
XS GIS Cut Line= 6
618311.272167087752297.573715985618310.105418235752296.725171328
617917.653509527752462.115618542617898.030914068752783.085215256
617851.777653426752917.640155345 617736.68093731752956.397212819
#Sta/Elev= 30
9395.747575.73389435.285547.68079456.989535.97319469.997 532.2749522.099530.9405
9565.506526.61279619.765515.49139771.689518.68369793.392508.49219804.244506.9207
9906.107505.00579926.145502.86749936.163 498.1019946.182496.14719976.238493.6977
10016.31495.960810036.35501.540810056.39511.311610086.44511.916110167.81524.0311
10178.38531.807210199.53541.982610220.68545.524210231.26555.049310262.98574.2229
10286.92577.857310294.07 585.61810304.62601.232210315.17607.436310408.37615.0721
#Mann= 3 , 0 , 0
9395.747  0.0814       09395.747  0.0814       010408.37  0.0814       0
#XS Ineff= 2 , 0
       09914.796        10069.72       0
Bank Sta=9395.747,10408.37
Exp/Cntr=0.3,0.1

Type RM Length L Ch R = 1 ,33097.37,245.826600,245.826600,245.826600
XS GIS Cut Line= 6
618252.746934021752254.020376975618131.743893236 752271.50552237
617904.813273907752294.586828396617756.128954858752316.473745748
617530.826954156752337.697045669617418.628653973752349.508843511
#Sta/Elev= 30
9568.929575.24129617.171558.2492  9645.7544.99079657.587540.63449687.899532.3984
9708.019528.60229738.174526.37499798.483515.21229858.793513.06669939.327507.8359
9959.552502.38559979.778487.5806 9989.89486.663810020.21487.768610030.31492.8166
10040.41513.641610050.51521.014110060.62525.855410100.85527.6065 10181.2533.8637
10221.38539.476410251.51549.0047 10271.6550.257810301.74555.2275 10331.9565.8581
10341.96570.818810362.07584.965410382.18594.582310402.29611.2182 10408.7613.2908
#Mann= 3 , 0 , 0
9568.929  0.0544       09568.929  0.0544       0 10408.7  0.0544       0
#XS Ineff= 2 , 0
       0                               0
Bank Sta=9568.929,10408.7
Exp/Cntr=0.3,0.1

Type RM Length L Ch R = 1 ,32851.54,245.826600,245.826600,245.826600
XS GIS Cut Line= 6
618434.871066358752115.463324454618260.079487268752116.021837259
618151.036381903752110.452856352618047.048284781752099.525076722
617692.888981468752042.191093192617509.457961627752021.407316554
#Sta/Elev= 30
9385.136 575.9069435.017573.18619485.017567.88719545.017561.03219605.076550.2048
9635.115547.28649655.141  547.239695.303541.86379705.358539.25949715.413533.3317
9745.578523.67799775.755520.52919806.094512.63129897.341510.00189907.498508.1721
9927.813496.80929948.128489.09219968.443486.2088 9998.82485.595710019.05485.8216
10029.16 490.16910039.28501.588310059.52504.248610120.23  521.9310180.77529.7386
10211.03529.898110221.11532.086510231.17536.7716 10281.4543.475910317.11545.6979
#Mann= 3 , 0 , 0
9385.136  0.1035       09385.136  0.1035       010317.11  0.1035       0
#XS Ineff= 2 , 0
       0                               0
Bank Sta=9385.136,10317.11
Exp/Cntr=0.3,0.1

Type RM Length L Ch R = 1 ,32605.71,245.826600,245.826600,245.826600
XS GIS Cut Line= 6
618473.954326678751969.986744319618288.883793293751927.336628567
617941.276657451751839.046390565617729.033476137751789.373395551
617566.580605494751755.768024229617536.070435923751750.368804308
#Sta/Elev= 30
9409.907551.64259439.593545.95629470.385545.30379521.705538.31419665.743 530.574
9707.013522.25959758.601515.16239789.553515.08699820.506513.73339830.823511.1613
9861.776506.65399892.729504.33739913.364504.97159944.316504.23129954.634501.9124
9975.191483.6512 9985.46481.683310005.99481.2148 10036.8481.762410047.07482.4575
10057.34484.502910077.89492.213910088.16497.791810098.43500.179210190.78506.3372
10262.27515.052410303.11521.613810333.75525.195410346.75527.855910373.33531.2035
#Mann= 3 , 0 , 0
9409.907    0.06       09409.907    0.06       010373.33    0.06       0
#XS Ineff= 2 , 0
       0                               0
Bank Sta=9409.907,10373.33
Exp/Cntr=0.3,0.1

Type RM Length L Ch R = 1 ,32359.89,245.826600,245.826600,245.826600
XS GIS Cut Line= 6
618596.654137503751844.647507539618361.053886629751724.428997383
618292.227075685751691.723239055618185.399109372751649.163088074
618009.333421429751601.213696067617593.266256289751509.453076147
#Sta/Elev= 30
9295.448554.28459308.531552.06149330.985542.81169342.211543.62269353.438541.9044
9364.664536.60729409.571533.14699454.477527.62679465.704524.88659476.931518.1797
9492.686513.9849 9719.61508.5843  9814.3499.92799845.646499.26779886.776500.4537
9927.906 499.4439938.159497.42049958.587483.79279968.801 478.9859979.014476.7034
9989.228476.367310030.05478.061910050.46 481.90610081.07 490.71810111.69495.3914
10132.13500.126410162.86501.375910265.38 510.93110296.27514.465310359.85524.0833
#Mann= 3 , 0 , 0
9295.448    0.06       09295.448    0.06       010359.85    0.06       0
#XS Ineff= 2 , 0
       0                               0
Bank Sta=9295.448,10359.85
Exp/Cntr=0.3,0.1

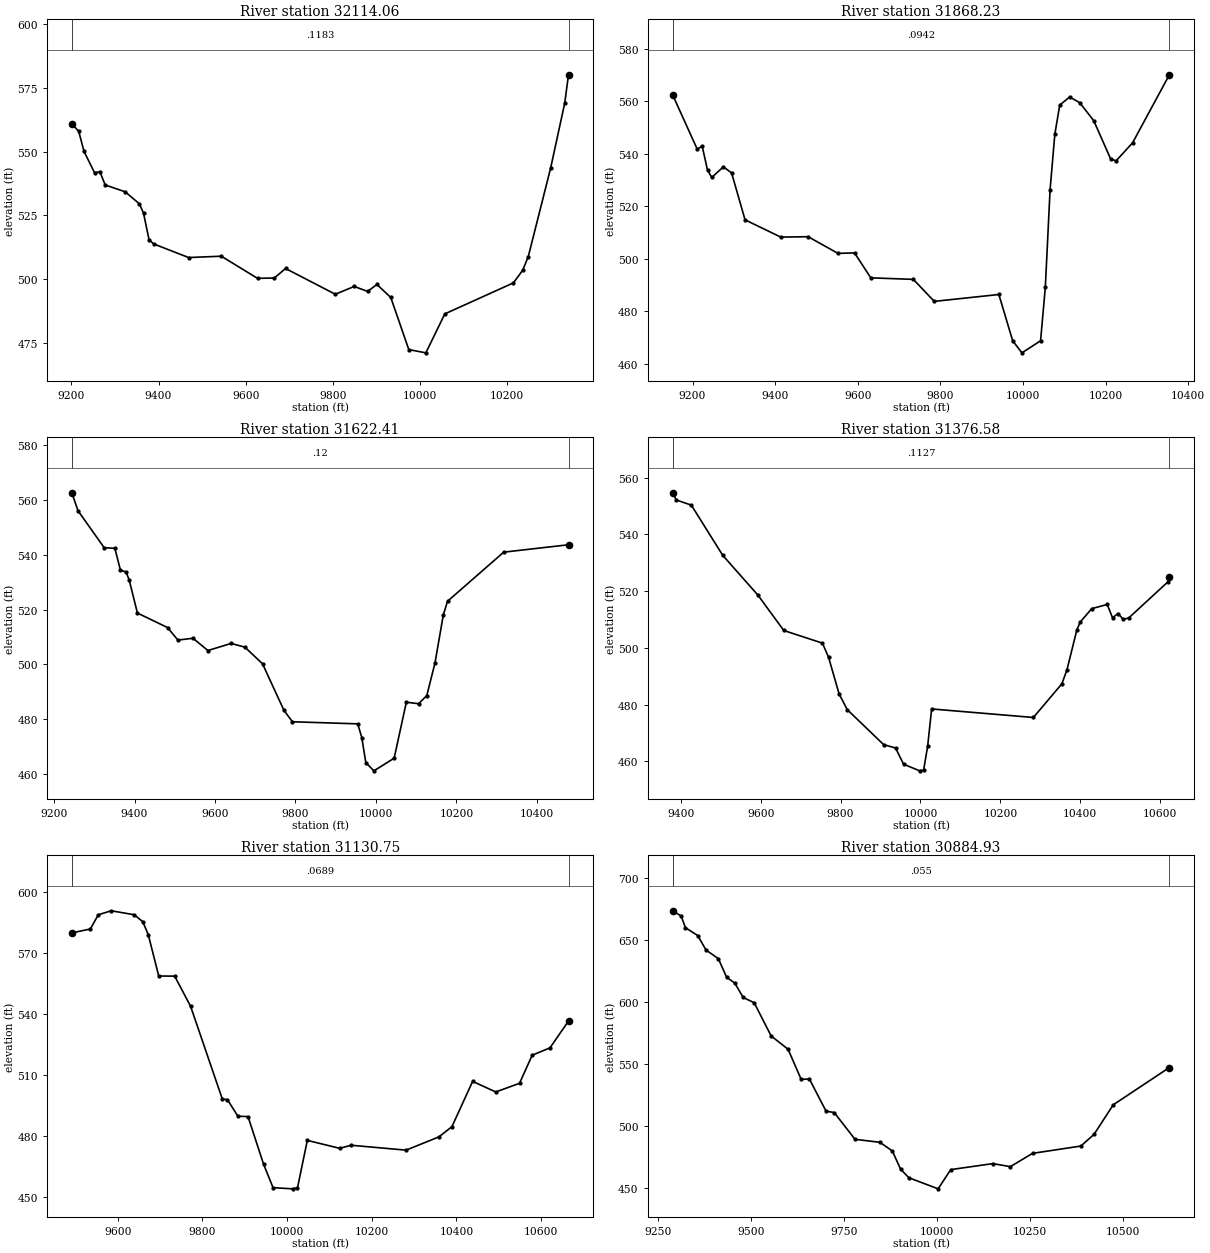
Type RM Length L Ch R = 1 ,32114.06,245.826600,245.826600,245.826600
XS GIS Cut Line= 6
 618658.52646811751785.154881957618486.241791063751659.195642511
618247.636915374751458.579767854618160.571669412751403.085028193
617811.228435676751292.964507869617676.888841398751241.955156998
#Sta/Elev= 30
 9201.11560.96619217.013557.92979229.024550.14459253.331541.70829265.484542.1732
9277.638536.95199323.585534.28639356.227529.54619365.622525.89379378.275515.5102
9388.869513.8661 9468.99508.53069544.011509.05579627.064500.38139665.751500.5142
9691.376 504.2399805.508494.15049848.816497.20129879.755495.2521 9900.95498.0029
9932.742492.87819974.069 472.46810013.18471.198410056.65486.453610213.99498.5997
10235.34503.549810248.15508.924410299.36543.555910331.65568.960410340.38 580.124
#Mann= 3 , 0 , 0
 9201.11  0.1183       0 9201.11  0.1183       010340.38  0.1183       0
#XS Ineff= 2 , 0
       09913.917                       0
Bank Sta=9201.11,10340.38
Exp/Cntr=0.3,0.1

Type RM Length L Ch R = 1 ,31868.23,245.826600,245.826600,245.826600
XS GIS Cut Line= 6
618673.170838822751771.073756274618512.751872489751644.095923628
  618343.9025673751469.236323798 618192.21781084751276.608068722
618037.935480088751014.268664778617903.991450792 750860.36077916
#Sta/Elev= 30
9151.909562.44819211.134541.8626 9223.44542.86619236.239533.82489246.586531.0265
9274.637535.0734 9294.55532.75159327.099514.89049413.666508.3073 9479.93508.4619
9551.872502.1249 9592.13 502.2869631.559492.79539734.499492.21319785.168483.8305
9941.469486.45649975.045  468.789997.429464.238610042.44468.832710053.95489.1712
10065.46526.321110076.97547.496110088.84 558.57810112.92561.679310137.22559.4968
10171.13552.655910212.05538.093410225.19 537.33810265.19544.2128 10354.2570.1214
#Mann= 3 , 0 , 0
9151.909  0.0942       09151.909  0.0942       0 10354.2  0.0942       0
#XS Ineff= 2 , 0
       09879.422                       0
Bank Sta=9151.909,10354.2
Exp/Cntr=0.3,0.1

Type RM Length L Ch R = 1 ,31622.41,245.826600,245.826600,245.826600
XS GIS Cut Line= 6
618707.184724504751738.368096966618544.030776191751585.982011494
618431.177476596751419.724760259618377.291679365751268.878289565
 618328.26651487750934.317083682618187.140925082750660.109236906
#Sta/Elev= 30
9244.085562.60339259.513556.04529324.472542.59949351.146 542.3469364.943534.3993
 9379.02533.73429386.735530.79919407.175 518.758 9482.05513.46659507.763508.8987
9545.338509.55729582.471505.09149640.094507.67619674.392506.31749718.189 500.254
9771.518483.25069792.492479.11769954.906478.35769964.955 473.3319975.003464.2015
  9995.1461.225310045.37465.8365 10075.7486.253110106.03 485.69610126.53488.6631
10147.02500.637410167.52518.009710178.02523.045210317.75540.956610478.81543.6519
#Mann= 3 , 0 , 0
9244.085    0.12       09244.085    0.12       010478.81    0.12       0
#XS Ineff= 2 , 0
       09876.403                       0
Bank Sta=9244.085,10478.81
Exp/Cntr=0.3,0.1

Type RM Length L Ch R = 1 ,31376.58,245.826600,245.826600,245.826600
XS GIS Cut Line= 6
618821.610407779751628.343401515618710.171866409751496.147939723
618633.238154133751345.984160017618566.961316815750872.861876553
618443.461265531 750679.69227882618316.108884184750542.176830212
#Sta/Elev= 30
9379.748554.63139388.917552.0946 9426.47550.27729505.173 532.5779593.547518.5121
9657.861506.12139754.669501.66289770.043496.66189796.255483.80619816.784478.2409
9907.677465.93489937.693464.71289957.712459.03559997.881456.682410007.93456.9405
10017.98465.329810028.03478.4833 10282.7475.478210354.05487.350410366.64492.2224
10391.25506.1879 10399.8509.075110428.86513.8225 10467.6515.284610480.79 510.595
10494.31 512.08710507.83510.053810521.35510.533410619.04523.193110623.08524.8867
#Mann= 3 , 0 , 0
9379.748  0.1127       09379.748  0.1127       010623.08  0.1127       0
#XS Ineff= 2 , 0
       09816.658                       0
Bank Sta=9379.748,10623.08
Exp/Cntr=0.3,0.1

Type RM Length L Ch R = 1 ,31130.75,245.826600,245.826600,245.826600
XS GIS Cut Line= 6
619210.728571866751281.363681186618896.334927925751049.043733307
618722.439307379750939.617794528 618664.47870558750881.166711041
618497.743597297750680.095354134618332.087000271750515.628575789
#Sta/Elev= 30
9491.241580.06929535.151581.98979553.796589.00369584.311590.97349638.852589.0132
9658.977585.57229671.933579.18519696.639558.79429734.302558.73119771.964543.8401
9846.789498.1699 9859.14497.74389883.788489.63279907.677489.43559944.442465.9391
9966.802454.381610012.82453.805510024.57454.326810047.79477.703910124.12473.8064
10151.51475.304910281.23 472.89210358.82 479.44610389.56 484.48410438.42 506.816
10493.08501.595810549.24505.865510579.25519.738910621.27523.358610665.02536.5781
#Mann= 3 , 0 , 0
9491.241  0.0689       09491.241  0.0689       010665.02  0.0689       0
#XS Ineff= 2 , 0
       0                               0
Bank Sta=9491.241,10665.02
Exp/Cntr=0.3,0.1

Type RM Length L Ch R = 1 ,30884.93,245.826600,245.826600,245.826600
XS GIS Cut Line= 6
619545.954327339751079.428457587618966.750661473750798.360750687
618804.848811723750714.177067356618645.129259696750622.353531786
618562.235008717750567.746786108618378.876732964750437.885635314
#Sta/Elev= 30
9290.334673.87999313.039669.68129324.702660.20889357.705653.86269379.882642.2226
9413.147635.15079435.324620.16719457.501615.36169479.678 603.8749509.386599.5742
9554.903572.75189600.419561.99669635.522537.72359657.786537.90459702.315512.0574
 9724.58510.81989780.241489.24189847.035486.83359880.432479.87889902.696465.1222
9924.961458.197810003.52449.2365 10037.4464.763810150.74469.623810197.52467.1581
10257.25477.896110386.97 483.81210422.21493.145210474.12517.138110624.85547.2341
#Mann= 3 , 0 , 0
9290.334   0.055       09290.334   0.055       010624.85   0.055       0
#XS Ineff= 2 , 0
       0                               0
Bank Sta=9290.334,10624.85
Exp/Cntr=0.3,0.1

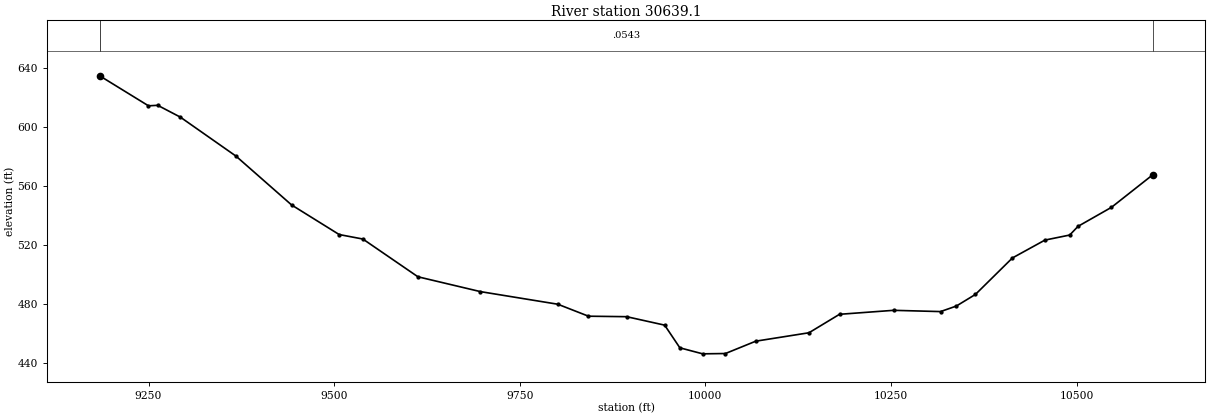
Type RM Length L Ch R = 1 , 30639.1,245.826600,245.826600,245.826600
XS GIS Cut Line= 6
619776.462449685750792.945928425619310.076183296750620.619800665
619135.663770714750571.571696238618735.666960639750477.673057736
618581.633505992750417.530827696618436.038020933750342.909956841
#Sta/Elev= 30
9184.126634.75269249.934614.35199262.325 614.7039292.762 606.7029367.711580.2372
9442.661547.05739506.804526.94949538.709523.90519612.885498.26789697.133488.1932
9801.304479.63819842.628471.5071 9894.01471.18059945.221465.43899965.705450.0379
9996.431 445.95510027.09 446.17110067.96 454.55110139.63460.267110180.74472.7979
10253.51475.500610316.84474.644810338.09478.396410363.86486.304510413.64511.0514
10457.46523.190710490.82526.613510502.07532.5318 10547.1 545.435 10602.7567.5265
#Mann= 3 , 0 , 0
9184.126  0.0543       09184.126  0.0543       0 10602.7  0.0543       0
#XS Ineff= 2 , 0
       0                               0
Bank Sta=9184.126,10602.7
Exp/Cntr=0.3,0.1