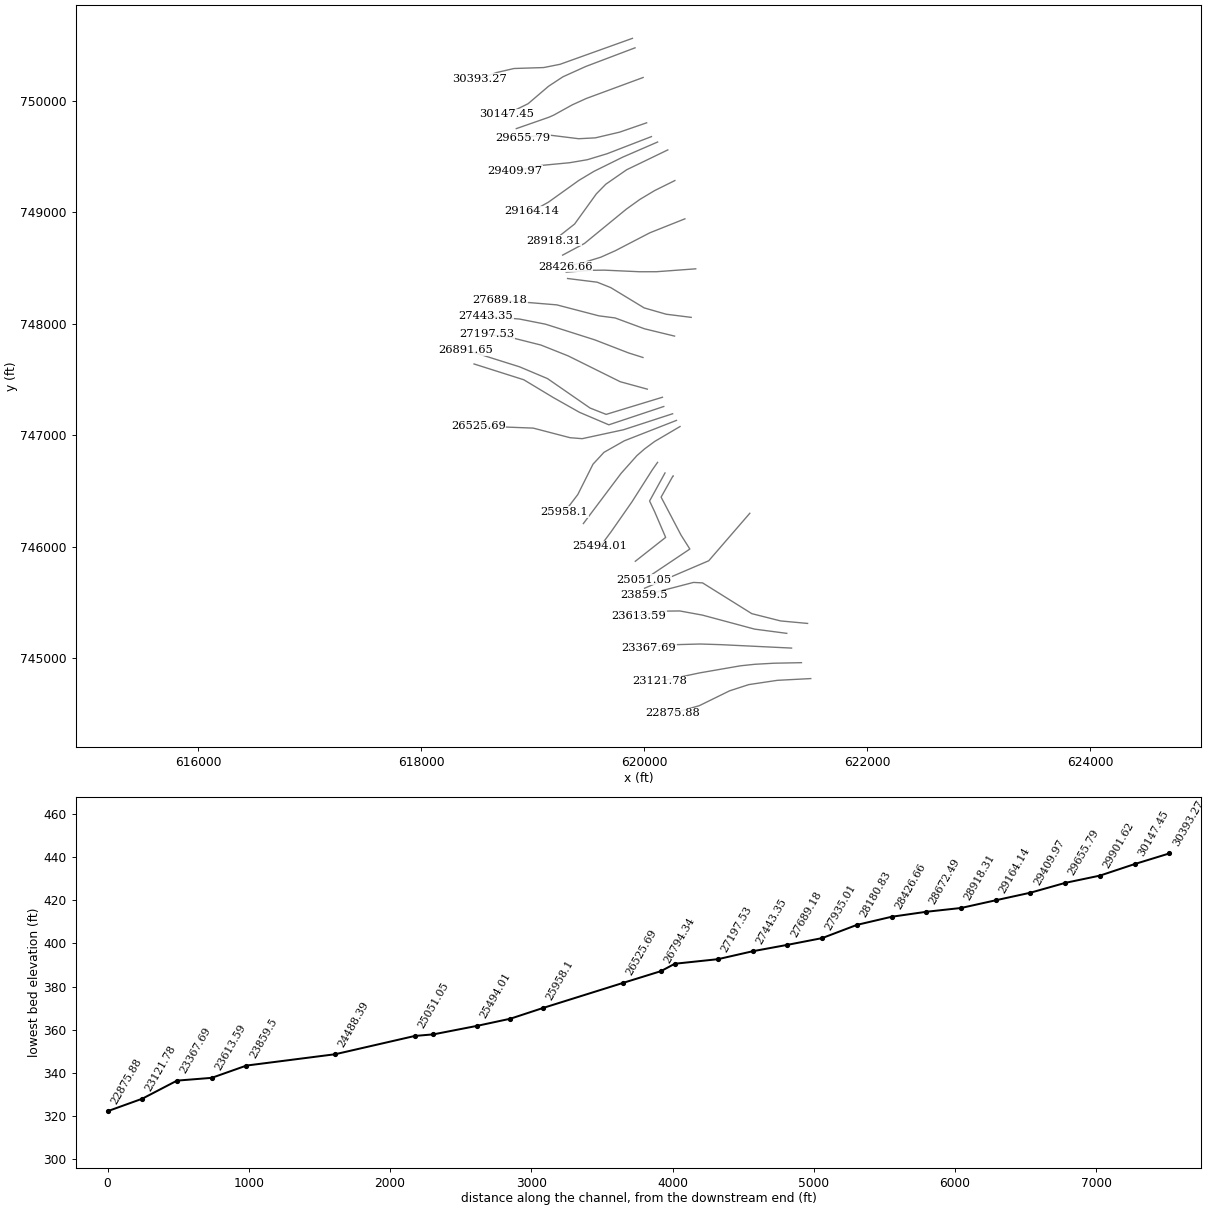
HEC-RAS study 3211_ras.prj: 3211

--- 3211_ras.g01 (geometry) --- (continued)

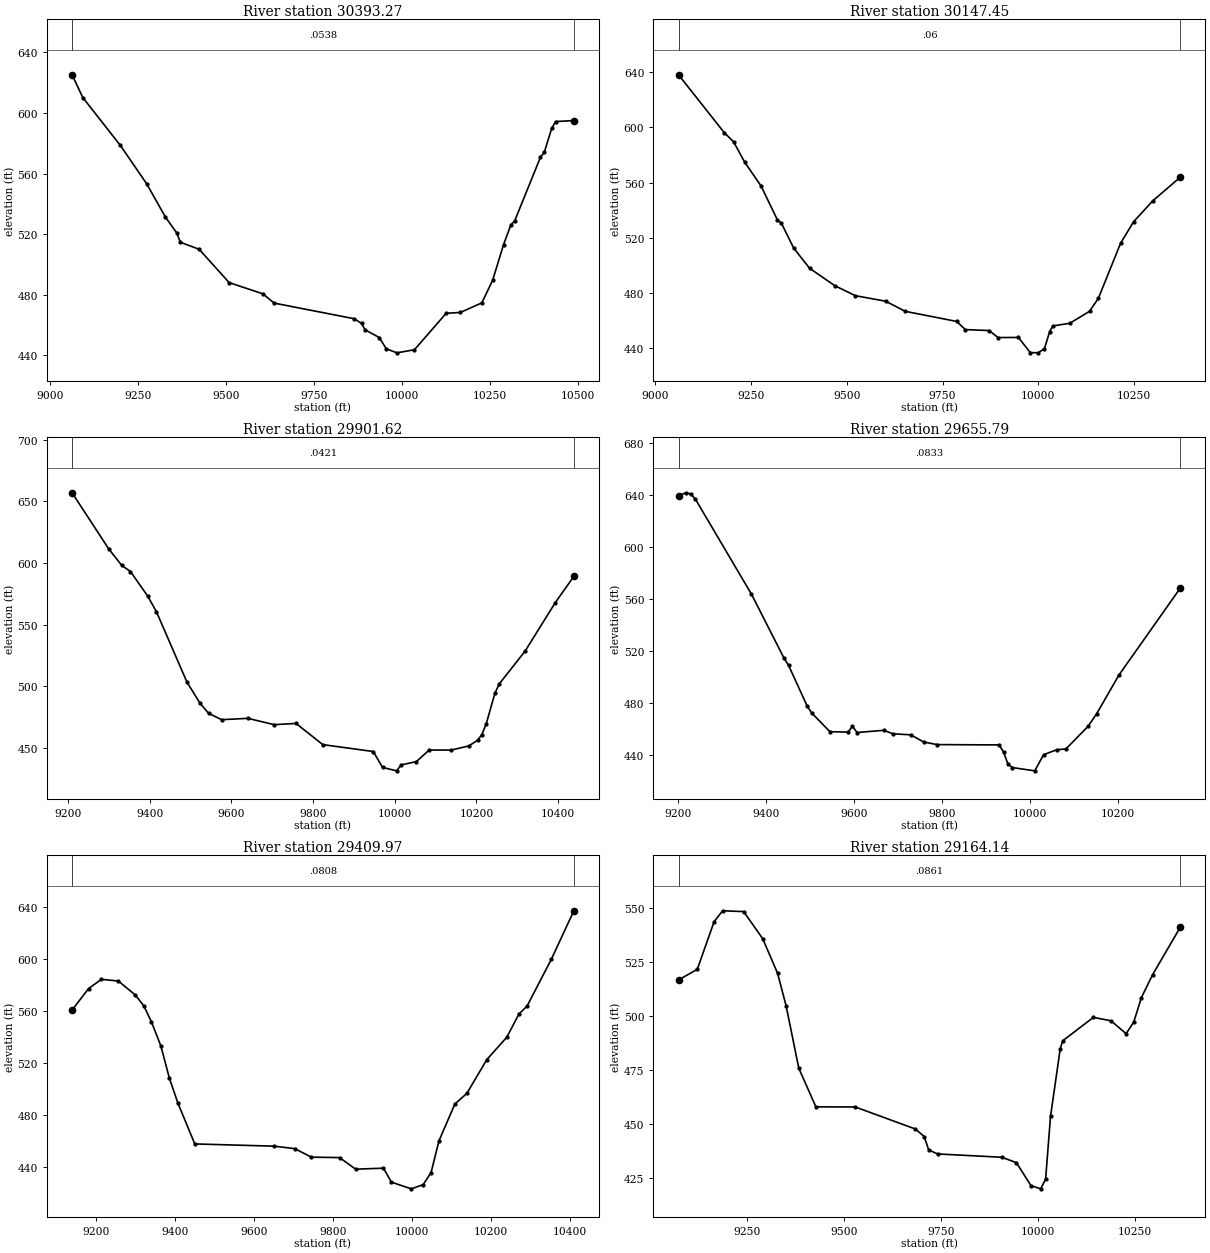
Type RM Length L Ch R = 1 ,30393.27,245.826600,245.826600,245.826600
XS GIS Cut Line= 6
619893.739308171750560.086074627619244.267308067750327.187325334
619097.592087942750297.995813933618831.505954899750289.501548993
 618675.37928703750253.298488216618526.789740958750198.388944562
#Sta/Elev= 30
9063.637625.22519094.263610.12129200.825578.56719275.419553.2641  9328.7531.2728
9360.669520.86819371.325514.59269424.607509.97329509.857487.93669605.621480.5697
9637.346474.43359865.758464.0659 9885.94460.94989896.005456.78729936.082451.6993
9956.099444.26929986.112441.568610036.12443.605110126.26467.705610166.54468.2329
10227.49474.575610258.29489.521510289.29513.108210310.07526.089910320.46528.5171
 10394.1570.802110404.75573.914310426.27589.990910437.04594.328310488.93     595
#Mann= 3 , 0 , 0
9063.637  0.0538       09063.637  0.0538       010488.93  0.0538       0
#XS Ineff= 2 , 0
       0                               0
Bank Sta=9063.637,10488.93
Exp/Cntr=0.3,0.1

Type RM Length L Ch R = 1 ,30147.45,245.826500,245.826500,245.826500
XS GIS Cut Line= 6
619916.951641732750474.974184917619476.026001438750308.037295135
 619270.11653001750215.088320039619141.261051115750130.358850387
618957.435221348 749973.52007755618763.076005566749878.068778502
#Sta/Elev= 30
9060.193638.16419179.544596.24539204.133 589.564 9232.92574.8757 9275.62557.6439
 9318.32533.08279328.995530.51549361.049512.53839402.384497.9688 9468.38 485.317
9522.045478.07239601.172474.05419652.416466.72669786.568459.41059809.573453.4766
9871.603452.8019 9894.85447.71769947.902447.79899978.994436.8581    9999436.6364
10016.07439.620810029.74452.093910037.73456.100310082.38458.071610133.87466.7411
10156.98476.166210214.96516.046210248.85531.636610299.44546.905810371.03563.9827
#Mann= 3 , 0 , 0
9060.193    0.06       09060.193    0.06       010371.03    0.06       0
#XS Ineff= 2 , 0
       0                               0
Bank Sta=9060.193,10371.03
Exp/Cntr=0.3,0.1

Type RM Length L Ch R = 1 ,29901.62,245.826600,245.826600,245.826600
XS GIS Cut Line= 6
619989.552566994750208.770792343619479.410072791750020.496302669
619352.839361861749962.867879715619188.964044935749872.042036036
619144.888561194749852.515941993 618851.71294498749750.178337347
#Sta/Elev= 30
9209.684656.96219299.555611.36719331.442597.9952  9352.7593.07099395.217572.9726
9416.475560.31389490.878503.44589522.765486.31419544.024477.9537 9576.01472.8117
9640.319473.90739704.627468.77229758.299469.76649823.717452.5799  9947.3446.9716
9970.173434.077610004.49431.299110015.91436.116910053.18438.824810084.29448.1664
10138.76448.172610181.65451.5573 10202.9456.122510213.49460.723710224.08469.4723
10245.26494.176210255.85501.7936 10319.4528.515210393.19567.802510438.73589.1357
#Mann= 3 , 0 , 0
9209.684  0.0421       09209.684  0.0421       010438.73  0.0421       0
#XS Ineff= 2 , 0
       0                               0
Bank Sta=9209.684,10438.73
Exp/Cntr=0.3,0.1

Type RM Length L Ch R = 1 ,29655.79,245.826600,245.826600,245.826600
XS GIS Cut Line= 6
620021.040097021749802.341116717619778.660680579749718.566207909
619561.143008351749667.416152355619411.787060487 749659.58753035
619117.949564105749695.919083167 618907.58908949749669.557043125
#Sta/Elev= 30
9202.027639.93369219.113 642.0339229.765641.06779240.416637.07759367.512563.9751
9441.284514.76969451.823509.10299493.493478.11219503.887472.63819545.465458.0866
9586.527  457.769596.792462.24439607.057 457.4549668.092459.14679688.338456.4797
9728.592455.66969758.667 450.1319788.697448.14559929.462447.88969939.578442.3778
9949.694433.0595 9959.81430.454410010.37 427.93810030.58440.410510060.88 444.243
10080.95444.744910131.11 462.10310151.11472.065110201.23501.604210340.71568.6807
#Mann= 3 , 0 , 0
9202.027  0.0833       09202.027  0.0833       010340.71  0.0833       0
#XS Ineff= 2 , 0
       0                               0
Bank Sta=9202.027,10340.71
Exp/Cntr=0.3,0.1

Type RM Length L Ch R = 1 ,29409.97,245.826600,245.826600,245.826600
XS GIS Cut Line= 6
620063.970925038749678.601956778619666.238136572749524.980357589
  619489.1514894749471.342780485619330.577351883749444.378169887
619081.335543042749420.457281553618839.679916176749370.091006744
#Sta/Elev= 30
9139.699560.66329181.587577.15559213.833584.24999256.828582.94539299.823572.1758
 9321.32563.85279340.425551.70099364.315533.19199385.812508.52959407.309489.3904
9450.217457.87569651.561456.15169703.652454.22239745.117447.72689816.612 447.391
9857.267438.50179927.763439.26039947.834428.53159998.014423.399210028.12426.5991
 10048.2435.920810068.27460.326810108.51488.572710138.72496.664610189.25522.5965
10239.95539.832810270.52557.6292   10291563.645710352.46599.562510409.54636.8619
#Mann= 3 , 0 , 0
9139.699  0.0808       09139.699  0.0808       010409.54  0.0808       0
#XS Ineff= 2 , 0
       0                               0
Bank Sta=9139.699,10409.54
Exp/Cntr=0.3,0.1

Type RM Length L Ch R = 1 ,29164.14,245.826600,245.826600,245.826600
XS GIS Cut Line= 6
620119.449875628749630.057875002619805.347382655749493.829039916
 619549.65420815749367.582719182 619413.84978704749286.340217129
619140.543405353749090.812596346618991.588496548749007.333206995
#Sta/Elev= 30
9073.231516.55279121.482521.44329164.943543.52949186.673548.54729240.999548.1699
9289.954535.69599328.407519.63329350.305504.64439383.151475.65339427.089457.8379
9528.708457.75979683.479447.57199706.197444.09089717.739437.86779740.822436.0365
9906.162434.50239943.632432.01929981.323421.366710006.43419.890510019.03424.4286
10031.64453.385710056.77  484.8110063.31488.430310142.19499.236210187.64497.6307
10226.37491.690110246.02497.035210265.67508.311310294.42518.9014 10366.1540.9725
#Mann= 3 , 0 , 0
9073.231  0.0861       09073.231  0.0861       0 10366.1  0.0861       0
#XS Ineff= 2 , 0
       0                               0
Bank Sta=9073.231,10366.1
Exp/Cntr=0.3,0.1

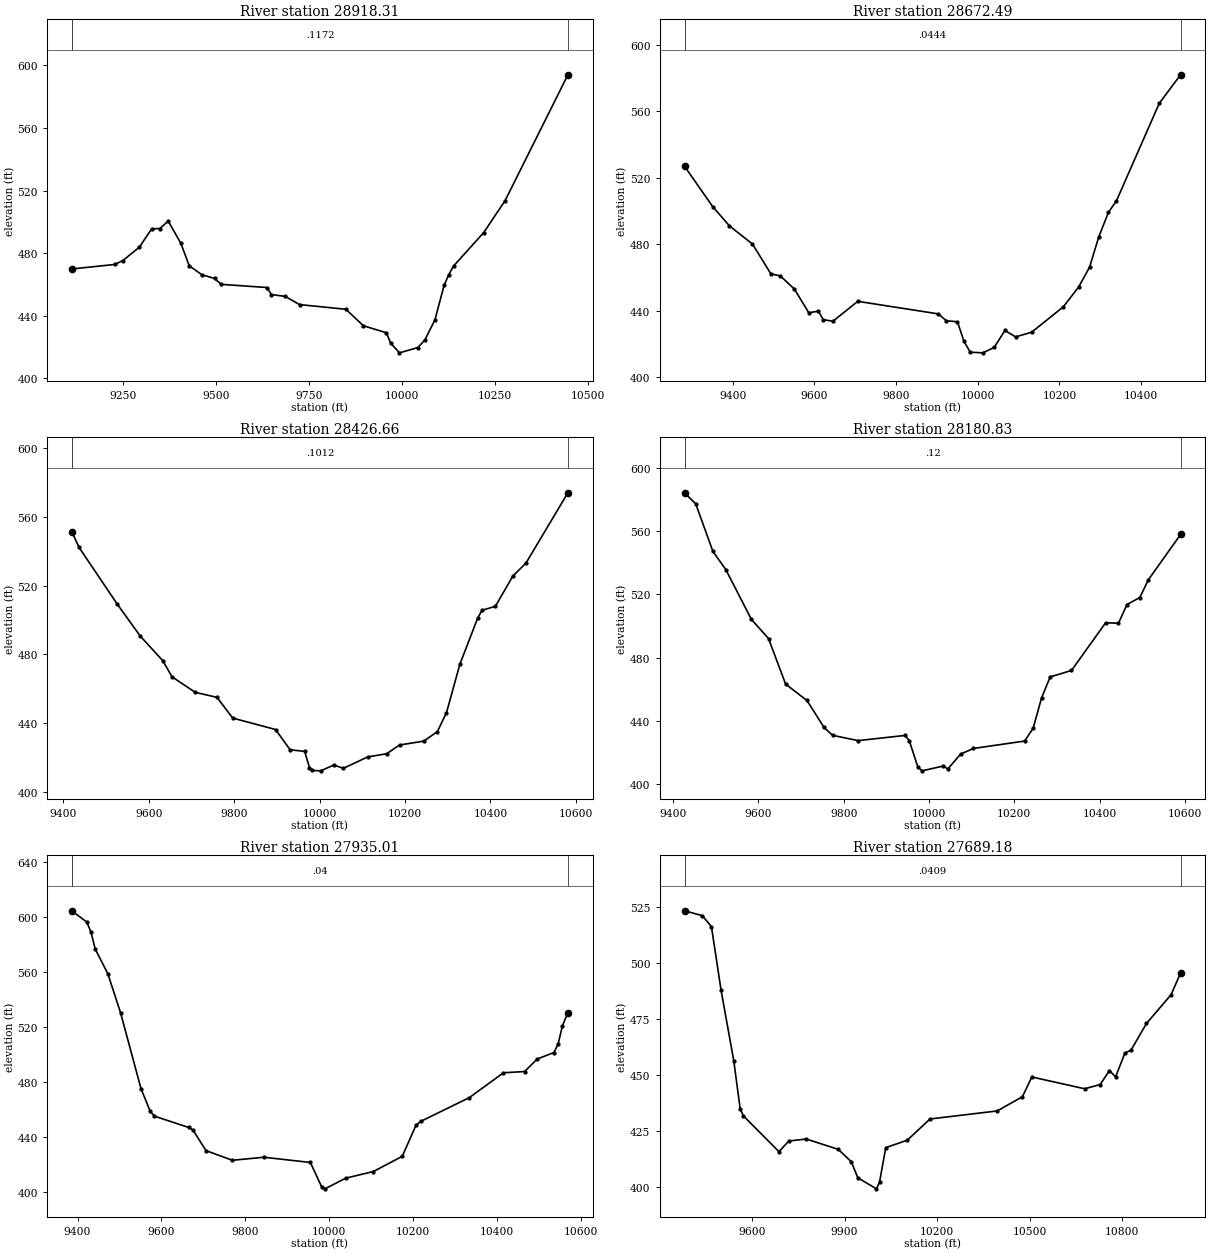
Type RM Length L Ch R = 1 ,28918.31,245.826600,245.826600,245.826600
XS GIS Cut Line= 6
620210.898493788749559.332658866619841.524337556 749380.97975277
619654.078627656749250.972098743 619569.81042778749164.797795333
619374.921319484748894.379080837619186.786558761748746.361884668
#Sta/Elev= 30
9112.357469.89749227.974472.75879249.809475.29449293.898483.77529327.186495.5393
9349.379495.70899371.571500.47199405.394486.3821 9428.08471.90529462.109466.2158
9496.138463.81229514.249460.06119636.931458.04649649.038453.54639686.227452.3643
9724.501447.13549849.083444.14399896.198433.63129957.943429.15349969.847422.4116
9993.231416.323210042.53 419.69110061.39424.501310088.61437.4352 10113.3459.5648
10125.65466.231310138.71471.797310219.29493.018810277.15513.542910445.91593.9108
#Mann= 3 , 0 , 0
9112.357  0.1172       09112.357  0.1172       010445.91  0.1172       0
#XS Ineff= 2 , 0
       0                               0
Bank Sta=9112.357,10445.91
Exp/Cntr=0.3,0.1

Type RM Length L Ch R = 1 ,28672.49,245.826600,245.826600,245.826600
XS GIS Cut Line= 6
620274.291969288749284.405751608620093.173559955749194.618065691
619960.550791746749115.247997779619839.357176472 749028.29174217
619463.674505378748720.413576955619267.381479717748615.530787914
#Sta/Elev= 30
 9281.81526.97359350.761502.66749391.738491.05099448.116480.13879493.427 462.123
 9516.49460.91169551.083 452.903  9586.1438.70499609.718439.67419621.528434.5484
9645.336433.6035 9706.09445.59369903.468438.02029922.833433.90789950.254433.2637
 9965.85421.65639981.445414.9479 10012.6414.566310040.26417.901810066.44428.0365
10092.61424.186910131.88426.990510209.39442.284610246.93454.219510273.61466.1422
10295.87484.146110319.72499.123310339.58506.176410444.42564.8905 10496.6582.0487
#Mann= 3 , 0 , 0
 9281.81  0.0444       0 9281.81  0.0444       0 10496.6  0.0444       0
#XS Ineff= 2 , 0
       09861.014                       0
Bank Sta=9281.81,10496.6
Exp/Cntr=0.3,0.1

Type RM Length L Ch R = 1 ,28426.66,245.826600,245.826600,245.826600
XS GIS Cut Line= 6
620364.130694569748940.988278142620049.462747749748815.587941626
619740.858330621 748655.37371245619610.616217809 748597.18611946
619466.136396974748552.427685061619289.138403895748512.789757138
#Sta/Elev= 30
9419.485 551.4719436.614542.28489525.292509.54949579.634490.75999632.629476.3862
9654.248466.9854 9708.56457.96779759.665455.0242 9796.57442.95159896.816436.3105
9930.841424.51959964.865423.60229976.207414.16719981.283 412.52810002.49412.2599
10033.05415.608510055.83413.751610112.61420.355610156.98422.2109 10187.2427.3024
 10244.1429.561410275.96435.145810297.14446.094410328.43474.224910370.08501.0978
10380.49505.772210411.57 507.98210452.64525.630210483.44533.243410581.53574.1213
#Mann= 3 , 0 , 0
9419.485  0.1012       09419.485  0.1012       010581.53  0.1012       0
#XS Ineff= 2 , 0
       0                               0
Bank Sta=9419.485,10581.53
Exp/Cntr=0.3,0.1

Type RM Length L Ch R = 1 ,28180.83,245.826600,245.826600,245.826600
XS GIS Cut Line= 6
620461.199036419748492.545368715620109.782012955 748466.63176474
619959.223862371748466.330739534619640.396119733748480.763180922
619525.381835859748479.344734787619299.708012637748462.877715887
#Sta/Elev= 30
9426.584584.30339452.972 577.2929493.169547.24649523.311535.78369583.524504.2299
9623.634492.14729663.729463.3375 9713.78  452.98 9753.82435.9468 9773.84430.9627
9833.852427.60539943.882430.89099953.896427.51419973.924410.86419983.939 408.499
10034.03411.580610044.05409.665710074.11419.059210104.17422.654310224.23427.3169
10244.24435.389110264.24454.748410284.24467.889410334.25471.961210414.32502.1237
10444.37 501.826 10464.4513.651510494.47518.068310514.56529.309610590.18557.9541
#Mann= 3 , 0 , 0
9426.584    0.12       09426.584    0.12       010590.18    0.12       0
#XS Ineff= 2 , 0
       0                               0
Bank Sta=9426.584,10590.18
Exp/Cntr=0.3,0.1

Type RM Length L Ch R = 1 ,27935.01,245.826600,245.826600,245.826600
XS GIS Cut Line= 6
620420.732054301748057.179008654620196.799032965748085.278872994
  619998.6712226748142.096807688619698.933481824748324.095581316
619577.855977739748372.561835471619311.811206664748405.723744133
#Sta/Elev= 30
9386.322604.75119422.184596.51749432.221589.16549442.257576.89089472.366 558.891
 9502.56530.6676 9551.51475.22169573.412458.82469583.559455.28069665.265447.0525
9675.514  445.139706.584430.16019769.503423.16259844.299425.37899955.424421.5872
9982.633403.6619 9990.25402.385210039.86410.169510105.66414.982510174.59426.0326
10207.69448.824310218.73451.485910334.64468.762610416.08  486.8610466.45487.7486
10496.53496.872310536.55   501.610546.56507.875810556.56520.842410569.76530.6113
#Mann= 3 , 0 , 0
9386.322    0.04       09386.322    0.04       010569.76    0.04       0
#XS Ineff= 2 , 0
       0                               0
Bank Sta=9386.322,10569.76
Exp/Cntr=0.3,0.1

Type RM Length L Ch R = 1 ,27689.18,245.826600,245.826600,245.826600
XS GIS Cut Line= 6
620271.571510851747889.104822381620002.083498625747954.537752664
619738.104891041748051.971314947619592.649906597748070.834878378
619214.733127545748169.282674455618704.239666609748211.441249989
#Sta/Elev= 30
9380.605523.20519438.109521.04199467.917516.18959499.354 487.6999540.574456.2082
9561.183434.95269571.582431.79619687.024415.83229718.906420.5895 9775.74421.4624
9879.795416.84389921.944411.30279942.866404.193110003.46399.266710013.49402.3188
10033.55417.6248 10103.6420.963610177.24 430.41410394.99 433.978   10477440.3159
10507.43449.128910679.07443.871810729.26 445.76410759.32451.967210779.36449.1809
10809.42459.759410829.46461.1008 10879.5472.973310959.51485.830410990.27495.5297
#Mann= 3 , 0 , 0
9380.605  0.0409       09380.605  0.0409       010990.27  0.0409       0
#XS Ineff= 2 , 0
       0                               0
Bank Sta=9380.605,10990.27
Exp/Cntr=0.3,0.1

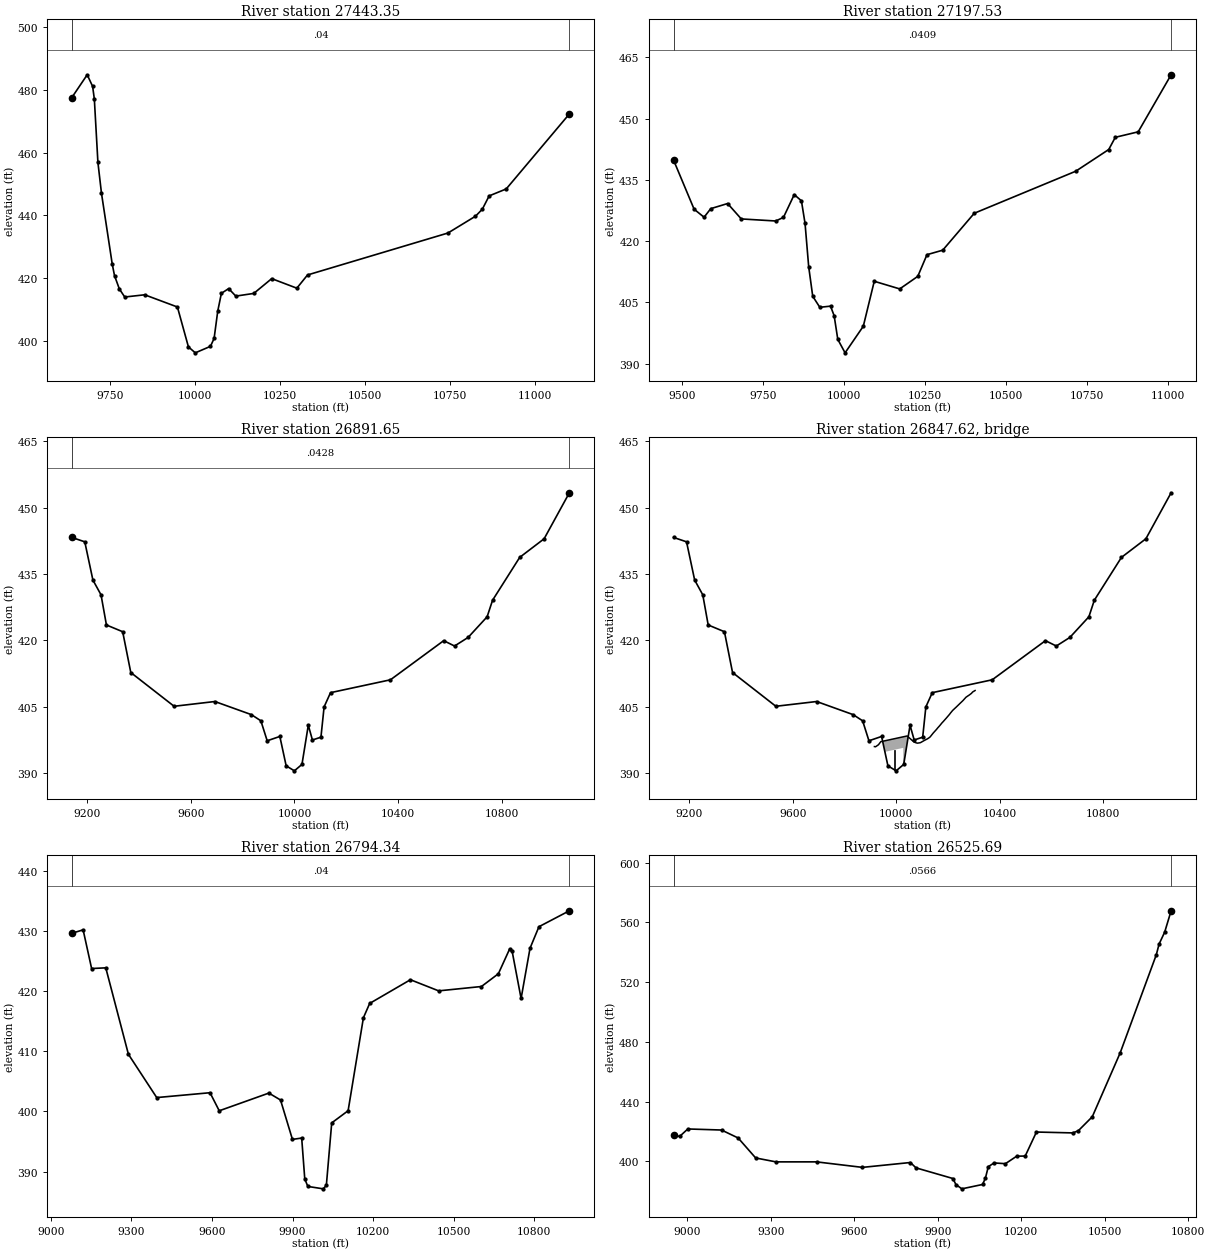
Type RM Length L Ch R = 1 ,27443.35,245.826600,245.826600,245.826600
XS GIS Cut Line= 6
619988.293880021747697.207072448619858.298715984747738.343599254
619557.464448331747854.820351804619114.664281628747995.768048474
618880.544846432748042.067650204618579.531614085748067.547343222
#Sta/Elev= 30
9637.529477.50619682.695484.73979698.643481.06419703.733477.03249714.252456.8686
9724.771447.03779756.327424.61039763.117420.86769777.408416.62069793.255414.0638
9851.953414.77099948.331410.88829980.759398.1993   10001396.3106 10045.7398.3833
 10056.4400.9183 10067.1409.5916 10077.8 415.23510099.16416.738110120.29414.3536
10173.13415.205510225.97419.909810299.93416.873810331.44421.077210744.85434.4151
10825.86439.752610846.03441.977810866.19446.223310916.45448.433411102.35472.2766
#Mann= 3 , 0 , 0
9637.529    0.04       09637.529    0.04       011102.35    0.04       0
#XS Ineff= 2 , 0
       0                               0
Bank Sta=9637.529,11102.35
Exp/Cntr=0.3,0.1

Type RM Length L Ch R = 1 ,27197.53,305.881600,305.881600,305.881600
XS GIS Cut Line= 6
620027.243502229747413.192925394619783.878655761747479.960111469
619317.288434058747711.435375303619073.023195326747808.775831074
618801.771741569747877.064252973618583.967449134747906.094058568
#Sta/Elev= 30
 9473.41439.82699536.741427.83019567.542425.86259588.076427.96389640.235429.2219
9682.418425.44859788.882424.94319812.827425.83989846.065431.40919868.224429.8816
9879.411424.35559890.651413.7492 9903.13406.50269925.036403.79939958.087404.0843
9969.327401.73349980.566395.940910003.05392.643910059.39399.162910093.19410.1746
10171.88408.303910227.61411.379210256.04416.690510304.69417.791810402.08426.8359
10715.49437.132610817.49442.454510837.76445.445910908.49446.785611010.15460.7621
#Mann= 3 , 0 , 0
 9473.41  0.0409       0 9473.41  0.0409       011010.15  0.0409       0
#XS Ineff= 2 , 0
       09955.382                       0
Bank Sta=9473.41,11010.15
Exp/Cntr=0.3,0.1

Type RM Length L Ch R = 1 ,26891.65,97.301100,97.301100,97.301100
XS GIS Cut Line= 6
620162.755371362747340.593258992619657.755452305747186.832089603
619513.039057583  747244.1156625619131.651059031747507.921590373
618881.412293166747613.443961531618402.039235741747764.190206021
#Sta/Elev= 30
9140.328443.28189190.248442.29349221.607433.65149252.967430.31299273.874423.4943
9336.593421.97179367.953412.74759535.205405.11689692.691406.19389833.674403.2286
9870.304401.83529894.724397.31729943.564398.29829967.984391.66199999.679 390.524
10029.03 391.97810053.45400.832810069.39397.499710102.29398.1281 10114.5404.9738
10139.31408.1947 10370.8 411.10410576.39419.948910618.32 418.73810670.74420.6841
10744.12425.348110765.08429.083810869.91438.774610964.26442.9807 11061.7453.3783
#Mann= 3 , 0 , 0
9140.328  0.0428       09140.328  0.0428       0 11061.7  0.0428       0
#XS Ineff= 2 , 0
       09934.452         10058.4       0
Bank Sta=9140.328,11061.7
Exp/Cntr=0.3,0.1

Type RM Length L Ch R = 3 ,26847.62,,,
BEGIN DESCRIPTION:
END DESCRIPTION:
Bridge Culvert--1,0,-1,-1, 0
Deck Dist Width WeirC Skew NumUp NumDn MinLoCord MaxHiCord MaxSubmerge Is_Ogee
36.150550,25.000000,2.6,0, 49, 49, , , 0.95, 0, 0,0,,
 9915.87 9920.14 9931.62 9933.16 9940.52 9957.32 9957.3210027.3210027.3210042.57
10046.4510055.2510057.9310069.4110072.4010075.0510081.5910091.9010094.0210106.44
10108.7410118.8710125.5910131.3010142.4310143.7210156.1510159.2810168.5810176.12
10181.0010192.9710193.4310205.8610209.8110218.2810220.0310226.3610231.0010242.44
10243.7710256.5410258.5210269.3110274.6010282.0810290.6810294.8510304.58
  396.01  395.96  396.43  396.55  397.12  397.33  397.33  398.22  398.22  398.41
  398.18  397.74  397.59  397.02  396.96  396.89  396.78  396.87  396.91  397.32
  397.40  397.70  397.94  398.21  399.03  399.12  399.92  400.16  400.77  401.32
  401.62  402.41  402.44  403.29  403.60  404.20  404.29  404.64  404.89  405.54
  405.62  406.33  406.45  407.15  407.37  407.66  408.04  408.33  408.68
 -603.99 -604.04 -603.57 -603.45 -602.88 -602.67  394.83  395.72 -601.78 -601.59
 -601.82 -602.26 -602.41 -602.98 -603.04 -603.11 -603.22 -603.13 -603.09 -602.68
 -602.60 -602.30 -602.06 -601.79 -600.97 -600.88 -600.08 -599.84 -599.23 -598.68
 -598.38 -597.59 -597.56 -596.71 -596.40 -595.80 -595.71 -595.36 -595.11 -594.46
 -594.38 -593.67 -593.55 -592.85 -592.63 -592.34 -591.96 -591.67 -591.32
 9915.87 9920.14 9931.62 9933.16 9940.52 9959.14 9959.1410029.1410029.1410042.57
10046.4510055.2510057.9310069.4110072.4010075.0510081.5910091.9010094.0210106.44
10108.7410118.8710125.5910131.3010142.4310143.7210156.1510159.2810168.5810176.12
10181.0010192.9710193.4310205.8610209.8110218.2810220.0310226.3610231.0010242.44
10243.7710256.5410258.5210269.3110274.6010282.0810290.6810294.8510304.58
  396.01  395.96  396.43  396.55  397.12  397.36  397.36  398.24  398.24  398.41
  398.18  397.74  397.59  397.02  396.96  396.89  396.78  396.87  396.91  397.32
  397.40  397.70  397.94  398.21  399.03  399.12  399.92  400.16  400.77  401.32
  401.62  402.41  402.44  403.29  403.60  404.20  404.29  404.64  404.89  405.54
  405.62  406.33  406.45  407.15  407.37  407.66  408.04  408.33  408.68
 -603.99 -604.04 -603.57 -603.45 -602.88 -602.64  394.86  395.74 -601.76 -601.59
 -601.82 -602.26 -602.41 -602.98 -603.04 -603.11 -603.22 -603.13 -603.09 -602.68
 -602.60 -602.30 -602.06 -601.79 -600.97 -600.88 -600.08 -599.84 -599.23 -598.68
 -598.38 -597.59 -597.56 -596.71 -596.40 -595.80 -595.71 -595.36 -595.11 -594.46
 -594.38 -593.67 -593.55 -592.85 -592.63 -592.34 -591.96 -591.67 -591.32
Pier Skew, UpSta & Num, DnSta & Num=  ,9992.32, 2 ,9994.14, 2 , 0 , 0 , 0 ,,
    3.00    3.00
 -602.22  397.78
    3.00    3.00
 -602.20  397.80
BR Coef=-1 , 0 , 0 ,, 0 ,,,0.8,0,1,0,
WSPro=,,,, 1 ,,,, 0 ,,,, 0 ,,,,-1 ,-1 ,-1 , 0 , 0 , 0 , 0 , 0
BC Design=,, 0 ,, 0 ,,,,,,

Type RM Length L Ch R = 1 ,26794.34,268.656300,268.656300,268.656300
XS GIS Cut Line= 6
620174.815071046747257.682824492619681.874851555 747093.36941801
619419.576386005747204.921638921619184.412244588747337.578334078
618919.098854274 747497.36935325618472.889970571747639.070823088
#Sta/Elev= 30
9078.002429.6551 9119.97 430.2299151.593423.78779204.298423.90439288.625409.5106
9394.035402.3083 9592.45403.11669626.811 400.1099811.546403.05469855.013401.9039
9899.376395.3432 9933.82395.57329945.301 388.7589956.783387.515110014.19387.1163
10025.67387.710910045.63398.092510106.69400.118310163.63415.590710186.97417.9794
10338.73421.924310443.79420.071710603.17420.796310666.17422.919110708.11427.0397
10717.57426.638310750.81418.800210784.04427.161210817.28430.750910930.53433.4016
#Mann= 3 , 0 , 0
9078.002    0.04       09078.002    0.04       010930.53    0.04       0
#XS Ineff= 2 , 0
       09923.852        10058.11       0
Bank Sta=9078.002,10930.53
Exp/Cntr=0.3,0.1

Type RM Length L Ch R = 1 ,26525.69,567.589600,567.589600,567.589600
XS GIS Cut Line= 6
620253.962644618747192.465132473 619812.92444698747048.863722841
619442.495980196 746969.00008806619333.856551829746977.748380762
619003.577307355747063.794877835618511.859114783747082.616618698
#Sta/Elev= 30
8950.706417.3841 8972.57416.78899001.858421.74919122.886 421.0379182.622415.7127
9245.619402.33499318.633399.71529464.216399.72279629.334396.03649801.728 399.298
9821.729395.71369954.434388.57829965.122384.56339986.497  381.6710060.89384.5865
10071.23388.830110081.56396.499610102.24398.996910143.18398.519210183.85403.5436
10214.18403.608910254.57419.6953 10385.2419.102610405.22420.588710455.28429.9243
10555.37472.616410685.37 538.36610695.38545.549310715.39553.486710738.54567.7893
#Mann= 3 , 0 , 0
8950.706  0.0566       08950.706  0.0566       010738.54  0.0566       0
#XS Ineff= 2 , 0
       0                10096.45       0
Bank Sta=8950.706,10738.54
Exp/Cntr=0.3,0.1

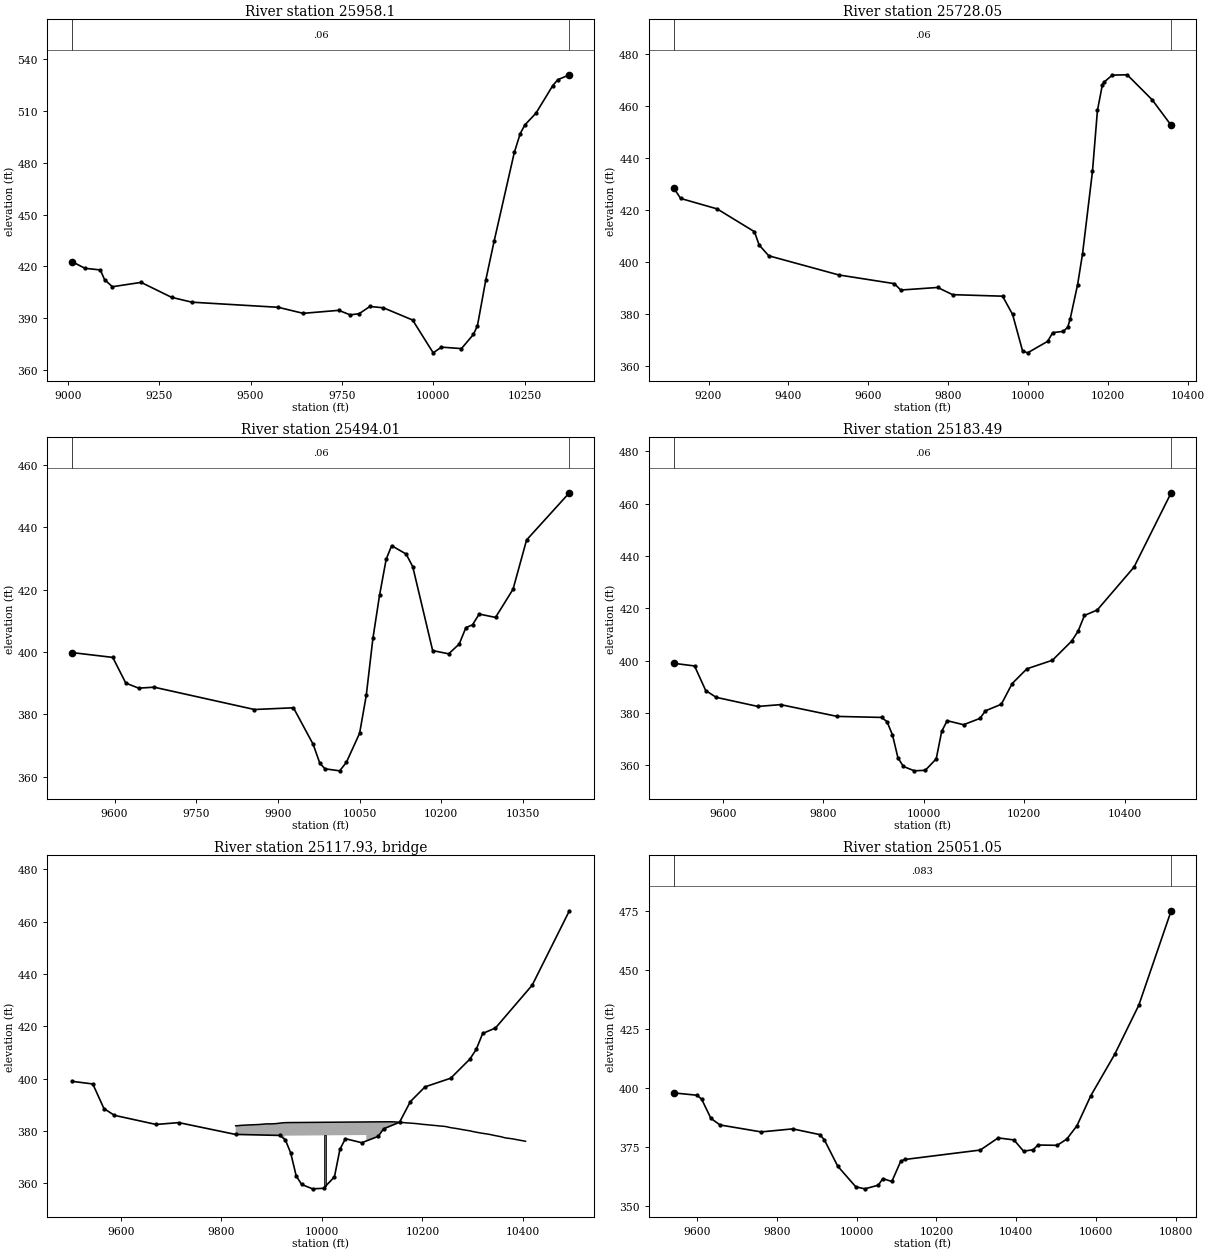
Type RM Length L Ch R = 1 , 25958.1,230.047100,230.047100,230.047100
XS GIS Cut Line= 6
620288.527394926747132.981608661619820.769161227746949.874006923
619638.211411092746846.326077394619539.943315602746740.112046676
619403.541703606746467.819169561619283.894632224746310.884688908
#Sta/Elev= 30
9011.455422.80959047.378418.92329089.379417.98579100.951 412.3369122.381408.2799
9200.773410.78599284.319402.13649340.015399.33199575.695396.38369644.018392.8903
9741.496394.62629772.278392.0188 9796.87392.65589826.641396.86699863.512396.0798
9943.249389.02849999.601370.049810022.12373.341910076.86 372.50810109.71380.7366
10120.66385.805510143.27412.017110166.11434.540710221.39485.902210237.63496.8297
10250.01501.737810280.79 508.68110326.58 524.57810340.39527.959310372.01530.8255
#Mann= 3 , 0 , 0
9011.455    0.06       09011.455    0.06       010372.01    0.06       0
#XS Ineff= 2 , 0
       0                               0
Bank Sta=9011.455,10372.01
Exp/Cntr=0.3,0.1

Type RM Length L Ch R = 1 ,25728.05,234.042700,234.042700,234.042700
XS GIS Cut Line= 6
620320.496874884747077.964364058620093.131227064746944.079591092
620003.413515716 746877.78966392619933.927055874746817.201749208
619791.805424944746657.809272166 619453.66083408746207.767440379
#Sta/Elev= 30
9112.686 428.5029130.154424.42059221.447420.40769314.716411.65259326.667406.5184
9350.568402.38979525.973395.02679664.683391.68979680.766 389.2339773.193390.2216
9810.258387.45919935.491386.87239960.537379.85619985.584365.80469998.107365.1048
10048.32369.527610060.89 372.86410087.61373.354310098.37374.950210104.52378.0666
10123.17391.306710135.57 403.21110160.37434.848410172.77 458.21810185.17468.1109
10189.07469.078410209.97471.798410247.17471.930210309.92462.280910357.17452.5268
#Mann= 3 , 0 , 0
9112.686    0.06       09112.686    0.06       010357.17    0.06       0
#XS Ineff= 2 , 0
       0                               0
Bank Sta=9112.686,10357.17
Exp/Cntr=0.3,0.1

Type RM Length L Ch R = 1 ,25494.01,310.516100,310.516100,310.516100
XS GIS Cut Line= 6
620119.080650926746756.449134901620071.680080146746689.162604257
619889.402553797746402.370952159619705.841311902746139.079283059
619637.994169682746047.250493094619602.791520631746003.000228398
#Sta/Elev= 30
9521.577399.81469596.742398.26319620.618 390.0129644.251388.38739672.732388.6904
 9856.95381.5237 9928.61382.07969964.839370.31789977.004364.27639986.566362.4668
10013.53 361.81910025.73364.532110050.12373.903410062.32386.051210074.51404.3586
10086.71418.2234 10098.9429.805410108.92434.161810135.49 431.47610147.69427.4179
10184.28400.450610213.73399.416110233.06402.558610245.25407.814410257.45408.7397
10269.74412.187210299.74411.111110331.91420.167910356.78435.995310435.39 451.153
#Mann= 3 , 0 , 0
9521.577    0.06       09521.577    0.06       010435.39    0.06       0
#XS Ineff= 2 , 0
       0                               0
Bank Sta=9521.577,10435.39
Exp/Cntr=0.3,0.1

Type RM Length L Ch R = 1 ,25183.49,132.441200,132.441200,132.441200
XS GIS Cut Line= 5
620185.756820142746661.519367009620047.411730647746409.831312582
620092.415554941746314.823239058620191.527045608746083.563094214
619919.404185236 745869.23768416
#Sta/Elev= 30
9502.344398.97589544.016397.95699566.195388.55739586.955385.97139669.995382.4809
9715.183383.18019828.089378.66959916.243378.28479927.123376.65189938.002 371.574
9948.882362.80219959.762359.53479981.521357.867110003.28358.081210025.04362.4386
10035.92372.9505 10046.8377.032110079.44375.494910112.08377.911310122.96380.8127
10154.59 383.31710176.28 391.249 10205.5396.870410256.42400.149610294.61407.4634
10307.34411.196410320.07417.256810345.53419.350210418.71435.737610492.67464.1573
#Mann= 3 , 0 , 0
9502.344    0.06       09502.344    0.06       010492.67    0.06       0
#XS Ineff= 2 , 0
       0                10185.49       0
Bank Sta=9502.344,10492.67
Exp/Cntr=0.3,0.1

Type RM Length L Ch R = 3 ,25117.93,,,
BEGIN DESCRIPTION:
END DESCRIPTION:
Bridge Culvert--1,0,-1,-1, 0
Deck Dist Width WeirC Skew NumUp NumDn MinLoCord MaxHiCord MaxSubmerge Is_Ogee
42.220600,48.000000,2.6,0, 58, 58, , , 0.95, 0, 0,0,,
 9828.46 9833.52 9839.66 9851.48 9852.28 9863.30 9871.04 9875.12 9886.94 9889.80
 9898.76 9908.56 9910.58 9922.40 9925.48 9925.48 9927.33 9928.9210088.4810088.48
10136.2110144.8310155.9210157.3510167.0110178.1110180.4410189.2010200.2910203.54
10211.3910222.4810226.6310233.5810244.6710249.7310255.7610266.8610272.8210275.33
10277.9610289.1110295.5110300.2610311.4110318.1410322.5510333.7010340.7710344.85
10355.9910363.4010367.1410378.2910386.0410389.4410400.5810405.41
  381.96  382.03  382.14  382.27  382.28  382.36  382.43  382.46  382.66  382.70
  382.70  382.80  382.85  383.12  383.15  383.15  383.17  383.19  383.44  383.44
  383.51  383.46  383.30  383.28  383.10  382.96  382.93  382.78  382.53  382.47
  382.34  382.13  382.06  381.91  381.73  381.55  381.27  380.95  380.76  380.67
  380.57  380.21  380.01  379.78  379.37  379.14  379.02  378.68  378.38  378.22
  377.81  377.43  377.28  377.02  376.74  376.61  376.23  376.04
 -618.04 -617.97 -617.86 -617.73 -617.72 -617.64 -617.57 -617.54 -617.34 -617.30
 -617.30 -617.20 -617.15 -616.88 -616.85  378.15  378.17  378.19  378.44 -616.56
 -616.49 -616.54 -616.70 -616.72 -616.90 -617.04 -617.07 -617.22 -617.47 -617.53
 -617.66 -617.87 -617.94 -618.09 -618.27 -618.45 -618.73 -619.05 -619.24 -619.33
 -619.43 -619.79 -619.99 -620.22 -620.63 -620.86 -620.98 -621.32 -621.62 -621.78
 -622.19 -622.57 -622.72 -622.98 -623.26 -623.39 -623.77 -623.96
 9828.46 9833.52 9839.66 9851.48 9852.28 9863.30 9871.04 9875.12 9886.94 9889.80
 9898.76 9908.56 9910.58 9922.40 9927.33 9928.92 9931.60 9931.6010094.6010094.60
10136.2110144.8310155.9210157.3510167.0110178.1110180.4410189.2010200.2910203.54
10211.3910222.4810226.6310233.5810244.6710249.7310255.7610266.8610272.8210275.33
10277.9610289.1110295.5110300.2610311.4110318.1410322.5510333.7010340.7710344.85
10355.9910363.4010367.1410378.2910386.0410389.4410400.5810405.41
  381.96  382.03  382.14  382.27  382.28  382.36  382.43  382.46  382.66  382.70
  382.70  382.80  382.85  383.12  383.17  383.19  383.19  383.19  383.45  383.45
  383.51  383.46  383.30  383.28  383.10  382.96  382.93  382.78  382.53  382.47
  382.34  382.13  382.06  381.91  381.73  381.55  381.27  380.95  380.76  380.67
  380.57  380.21  380.01  379.78  379.37  379.14  379.02  378.68  378.38  378.22
  377.81  377.43  377.28  377.02  376.74  376.61  376.23  376.04
 -618.04 -617.97 -617.86 -617.73 -617.72 -617.64 -617.57 -617.54 -617.34 -617.30
 -617.30 -617.20 -617.15 -616.88 -616.83 -616.81 -616.81  378.19  378.45 -616.55
 -616.49 -616.54 -616.70 -616.72 -616.90 -617.04 -617.07 -617.22 -617.47 -617.53
 -617.66 -617.87 -617.94 -618.09 -618.27 -618.45 -618.73 -619.05 -619.24 -619.33
 -619.43 -619.79 -619.99 -620.22 -620.63 -620.86 -620.98 -621.32 -621.62 -621.78
 -622.19 -622.57 -622.72 -622.98 -623.26 -623.39 -623.77 -623.96
Pier Skew, UpSta & Num, DnSta & Num=  ,10006.98, 2 ,10013.10, 2 , 0 , 0 , 0 ,,
    4.00    4.00
 -616.69  383.31
    4.00    4.00
 -616.68  383.32
BR Coef=-1 , 0 , 0 ,, 0 ,,,0.8,0,1,0,
WSPro=,,,, 1 ,,,, 0 ,,,, 0 ,,,,-1 ,-1 ,-1 , 0 , 0 , 0 , 0 , 0
BC Design=,, 0 ,, 0 ,,,,,,

Type RM Length L Ch R = 1 ,25051.05,562.661100,562.661100,562.661100
XS GIS Cut Line= 6
620259.232326746746634.687473714 620257.42957738746634.850434095
620150.753845811746444.834287047620329.102334708 746104.80539234
 620408.58958295745978.950582579619997.696831137745703.441492826
#Sta/Elev= 30
9541.091397.75939600.071396.75659611.539395.03999634.475386.97379657.411384.1791
9760.624381.23129839.671382.51449907.424380.08269918.716377.93249952.592366.6895
9997.761357.973110020.34357.119110054.22358.669410065.51361.4563 10088.1 360.237
10110.68368.895310121.97369.580510309.99373.555210354.59378.693610394.27 377.833
10418.35373.062510442.43373.682910454.47375.678210502.63 375.55310526.71378.1963
10552.11383.817610586.91396.564810647.11414.180910707.31 434.94110788.34474.8911
#Mann= 3 , 0 , 0
9541.091   0.083       09541.091   0.083       010788.34   0.083       0
#XS Ineff= 2 , 0
       0                10140.17       0
Bank Sta=9541.091,10788.34
Exp/Cntr=0.3,0.1

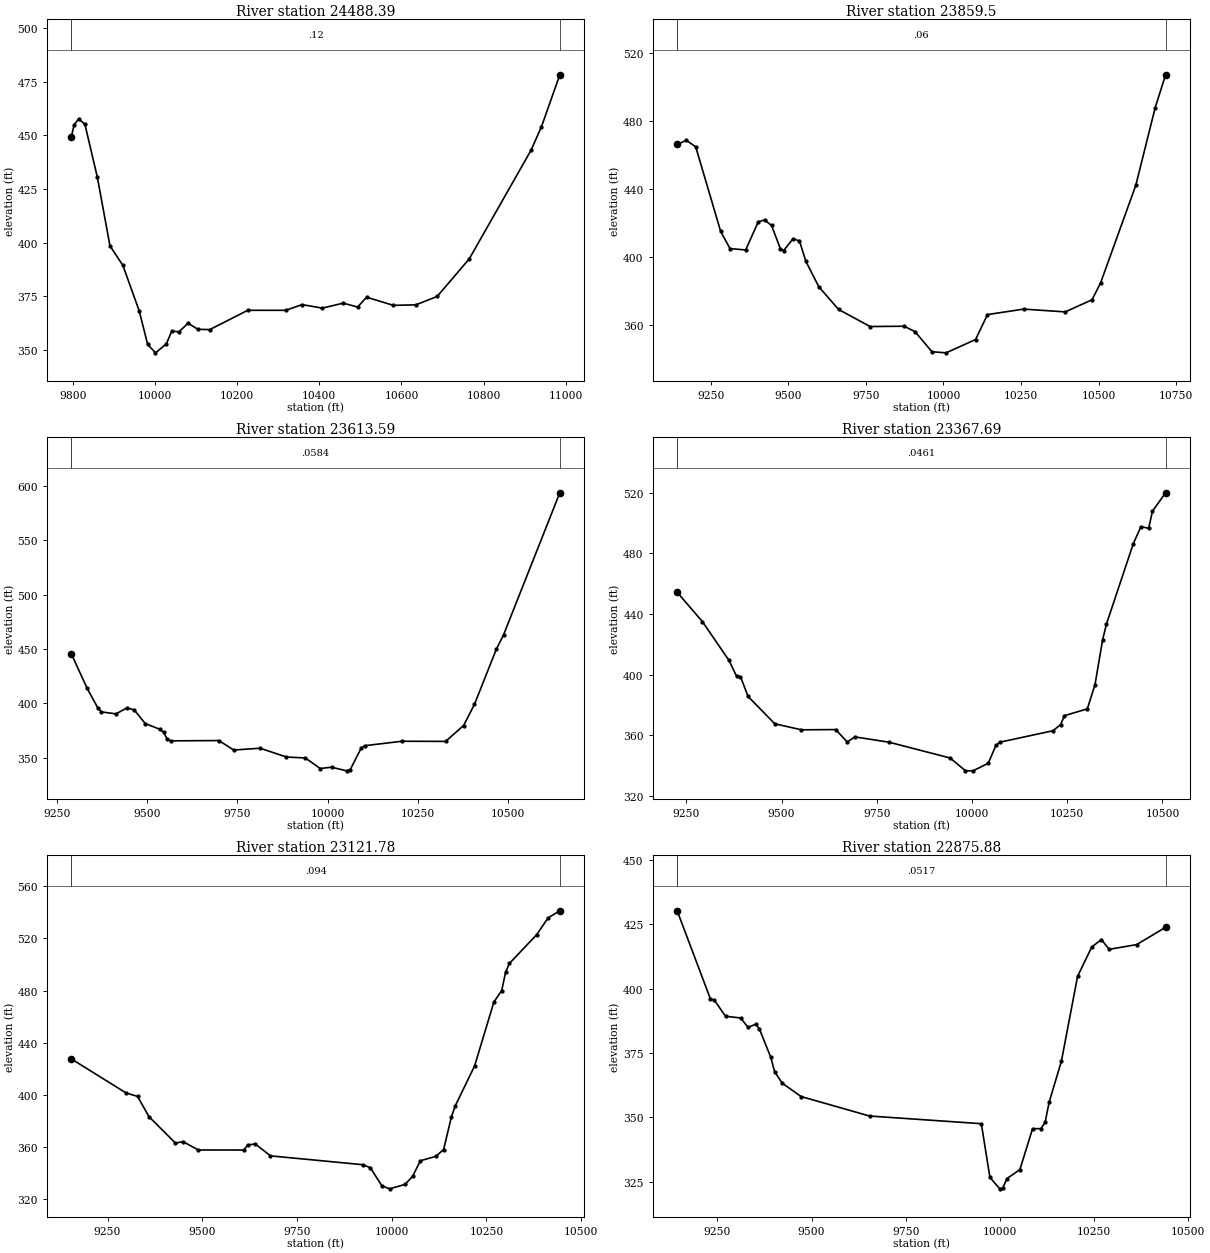
Type RM Length L Ch R = 1 ,24488.39,628.890500,628.890500,628.890500
XS GIS Cut Line= 3
620946.419481635746299.847236693620577.983500868745873.843133911
620002.302280933745627.451571792
#Sta/Elev= 30
9796.226449.36329802.634454.77049813.683457.63279829.077455.15449859.544430.3609
9890.118398.50939921.625389.38649961.288 368.2339981.839352.655210000.95348.6756
10027.39352.824810040.62358.805110058.27358.466410080.28362.483910104.14359.6349
10133.16359.496710225.71 368.48610318.26368.481310357.92371.142510407.34369.4931
10458.17371.825810493.23370.011510514.98374.596510580.25370.800110634.63371.0036
 10686.9374.929410765.16392.449510915.63443.050810941.05  454.0110985.65478.1764
#Mann= 3 , 0 , 0
9796.226    0.12       09796.226    0.12       010985.65    0.12       0
#XS Ineff= 2 , 0
       0                10124.61       0
Bank Sta=9796.226,10985.65
Exp/Cntr=0.3,0.1

Type RM Length L Ch R = 1 , 23859.5,245.905000,245.905000,245.905000
XS GIS Cut Line= 6
621464.645417631 745311.72892414621222.567222118745334.150111303
620964.326576233745399.416897491620522.686501026745675.391886801
620441.026868701745679.518848956620002.302280933745565.278000012
#Sta/Elev= 30
9142.118465.95199171.782468.36659201.842464.58559282.171414.86949312.333 404.724
 9362.71403.91569403.221420.42299423.548421.54769446.166418.33129474.431404.6984
9484.706403.43619515.532410.57539536.083409.18969556.873397.15439598.544382.2485
9662.263368.91119763.783358.89039873.575359.06979908.541355.85689962.721344.0843
10008.32343.423510103.27351.232110141.77  365.9210258.11369.136210392.32367.5027
10478.44374.623810505.98384.496510619.65442.017310681.65487.357310715.44506.9316
#Mann= 3 , 0 , 0
9142.118    0.06       09142.118    0.06       010715.44    0.06       0
#XS Ineff= 2 , 0
       0                10153.11       0
Bank Sta=9142.118,10715.44
Exp/Cntr=0.3,0.1

Type RM Length L Ch R = 1 ,23613.59,245.904900,245.904900,245.904900
XS GIS Cut Line= 6
621277.970915919745222.686466322620989.504840573745260.702154607
620521.688877203745386.261239792620317.957922927745423.657144622
620151.784191656745421.600582543619953.474576358745379.505824232
#Sta/Elev= 30
9290.599445.43589333.747414.04999363.871395.67059373.913392.05459414.223390.2247
9444.455395.79889464.609393.90369495.022381.34669535.574376.01659545.712373.3304
 9555.85366.97389565.988365.3722 9698.99365.65159740.246 356.9089813.034358.5984
9885.948350.4846 9938.03349.63169979.695339.884510010.92341.120210052.44337.7442
10062.83 338.88110093.69359.180910103.96360.950710206.06365.021210326.64364.8759
10376.66379.486710406.69399.028510467.07449.651510487.28463.071410643.02593.9608
#Mann= 3 , 0 , 0
9290.599  0.0584       09290.599  0.0584       010643.02  0.0584       0
#XS Ineff= 2 , 0
       0                10116.08       0
Bank Sta=9290.599,10643.02
Exp/Cntr=0.3,0.1

Type RM Length L Ch R = 1 ,23367.69,245.905000,245.905000,245.905000
XS GIS Cut Line= 6
621321.070200459 745090.55396856620688.471911495745121.220909263
620502.091066416745127.114275299620247.507308984745120.307894167
620148.870351444745111.089798255620041.070713913745095.573516298
#Sta/Elev= 30
9225.724454.35759291.832435.05879361.884409.36049381.899398.85029391.907398.7181
9411.922 385.5859481.998367.52989552.104363.55049642.239363.70499672.284355.4838
9692.314358.8863 9782.45355.34649942.615  344.939982.639336.526210002.65336.4588
10042.66341.494710062.66353.208210072.66355.349910212.69362.943810232.71366.9953
10242.72372.906510302.83  377.3810322.91393.2938   10343423.054510353.04433.3983
10423.46486.399210443.64497.729610463.82496.612510473.91507.9129 10508.3520.0694
#Mann= 3 , 0 , 0
9225.724  0.0461       09225.724  0.0461       0 10508.3  0.0461       0
#XS Ineff= 2 , 0
       0                10103.61       0
Bank Sta=9225.724,10508.3
Exp/Cntr=0.3,0.1

Type RM Length L Ch R = 1 ,23121.78,245.904900,245.904900,245.904900
XS GIS Cut Line= 6
621409.675968958744959.754976976621161.209051629744954.717785417
620991.674651494 744945.22925599620864.318682594744931.836259499
620498.039031797744868.345358568 620134.83639434744791.643379749
#Sta/Elev= 30
9154.549427.63439299.255401.51039329.261398.92069359.267383.41679429.317363.1251
9449.349  364.289489.411357.87529609.744 357.8169619.799361.72069639.909362.4592
 9680.13353.3631 9923.33346.60679943.656344.27879974.145330.46559994.471328.0916
10035.12331.466910055.45337.7143 10075.8349.624810116.69352.999610137.14358.2364
10157.58383.0676 10167.8391.621310218.91422.246110270.02471.360310290.47479.9784
10300.69494.029810310.91500.823910382.47 522.74110413.12535.782210443.91541.1767
#Mann= 3 , 0 , 0
9154.549   0.094       09154.549   0.094       010443.91   0.094       0
#XS Ineff= 2 , 0
       0                               0
Bank Sta=9154.549,10443.91
Exp/Cntr=0.3,0.1

Type RM Length L Ch R = 1 ,22875.88,245.905000,245.905000,245.905000
XS GIS Cut Line= 6
621493.269959798744817.077375204621193.032820393744801.278631472
620937.618145809744763.017555691620765.573109486744707.306930336
 620492.98014495744573.706142706 620250.06585239 744504.89388353
#Sta/Elev= 30
9143.189430.20619231.515395.98959241.521395.5984 9271.54389.27939311.613388.6113
9331.658384.92019351.703386.20829361.726384.28039391.794373.31239401.817367.8115
9421.862363.32379472.094358.13129653.918350.55589950.746347.57899973.395326.7765
9999.516322.298110007.43322.546610018.83326.291310053.03329.747510086.63345.6131
10108.91345.676410119.96 348.06210130.81355.960910163.33371.862810206.25404.7541
10243.78416.135310269.42419.0513 10290.2415.241210362.94417.077210439.87423.7792
#Mann= 3 , 0 , 0
9143.189  0.0517       09143.189  0.0517       010439.87  0.0517       0
#XS Ineff= 2 , 0
       0                               0
Bank Sta=9143.189,10439.87
Exp/Cntr=0.3,0.1