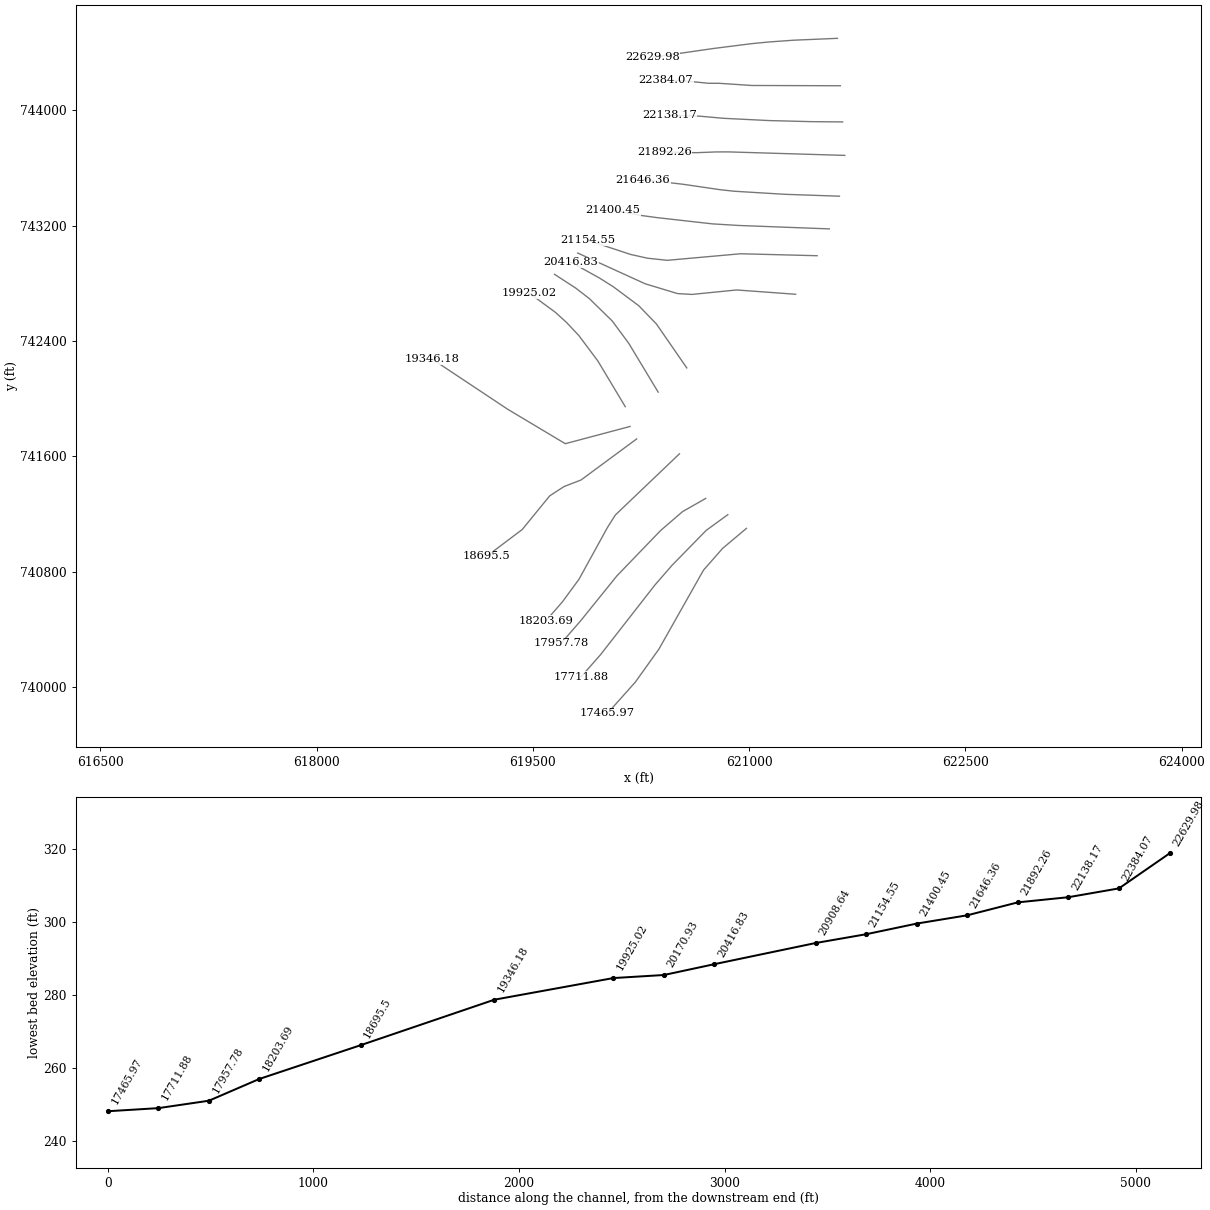
HEC-RAS study 3211_ras.prj: 3211

--- 3211_ras.g01 (geometry) --- (continued)

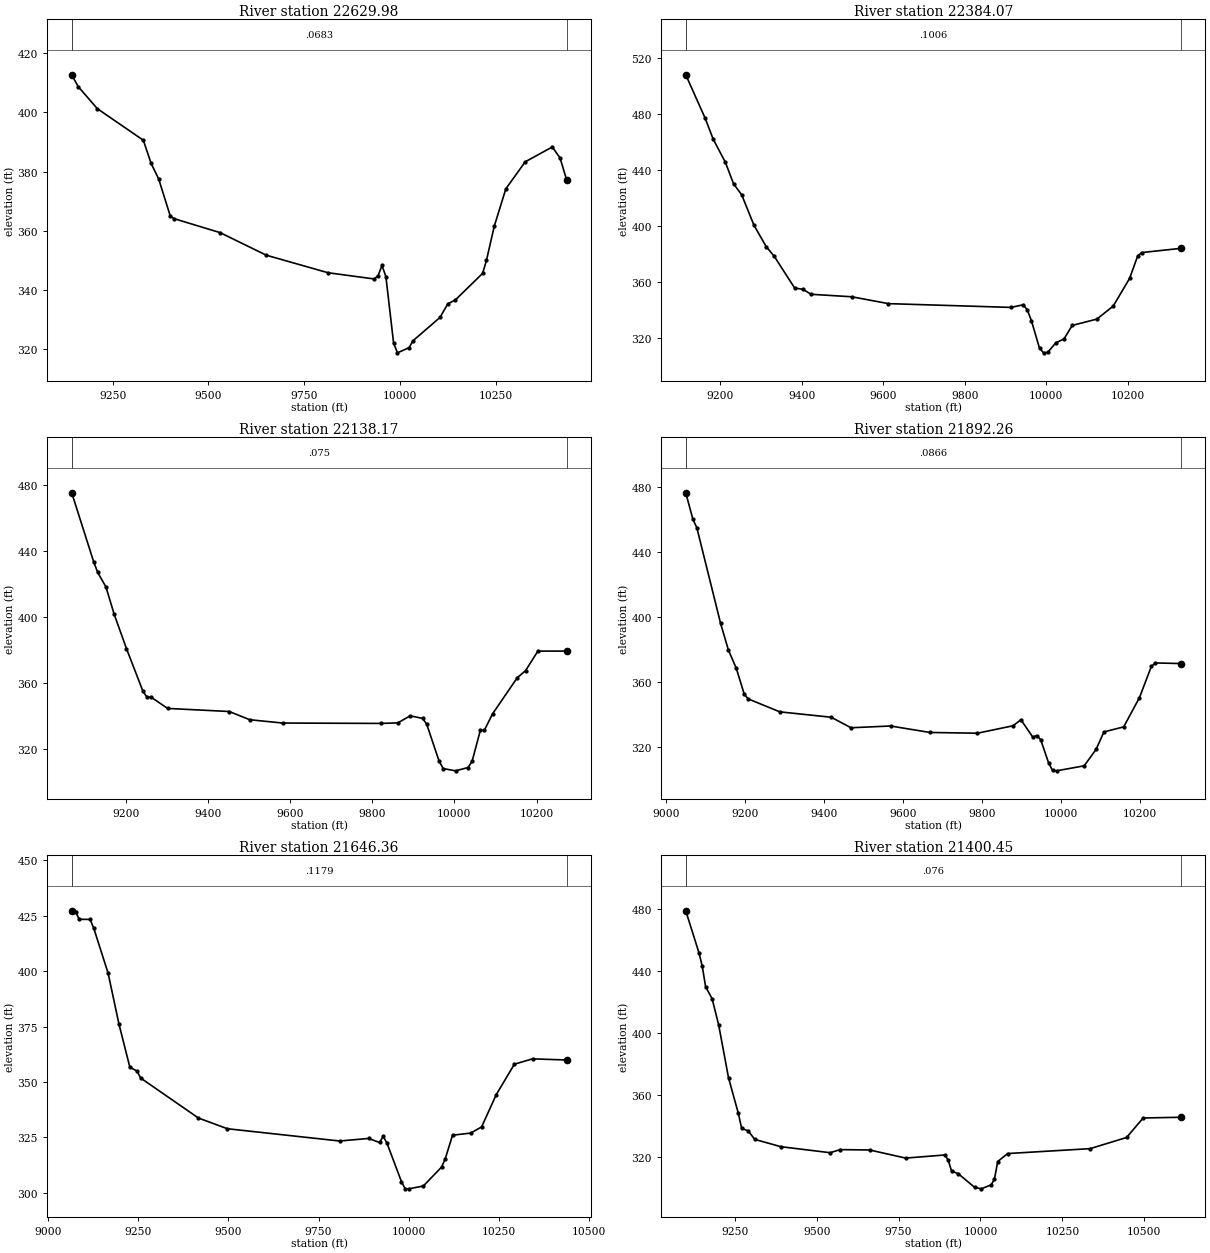
Type RM Length L Ch R = 1 ,22629.98,245.904900,245.904900,245.904900
XS GIS Cut Line= 6
621611.750592798744499.967445643621307.249817285744486.985521854
621135.310891814744474.614809634621016.744773694744463.062973207
620757.386513081744430.265104741620328.044751278744368.430810459
#Sta/Elev= 30
9143.272412.76159160.032408.7847 9210.06 401.2949330.165390.61329350.189382.8607
9370.214377.4986 9400.25365.04819410.262364.07879530.521359.35119650.896351.7199
9811.829345.78879932.777343.67259942.868344.84329952.959348.2317 9963.05344.5045
9983.232321.97259993.323318.6786 10023.6320.431310033.69322.748710104.35330.6633
10124.54335.243810144.73336.622210215.48345.558410225.59349.985110245.81361.4712
10276.13374.181810326.67383.307410397.42388.337310417.64384.604810434.78377.1673
#Mann= 3 , 0 , 0
9143.272  0.0683       09143.272  0.0683       010434.78  0.0683       0
#XS Ineff= 2 , 0
       0                               0
Bank Sta=9143.272,10434.78
Exp/Cntr=0.3,0.1

Type RM Length L Ch R = 1 ,22384.07,245.905000,245.905000,245.905000
XS GIS Cut Line= 6
621632.205245618744171.051495435621017.702269385 744172.94275016
620793.697573071744187.888614187620716.929836954744188.171306528
620534.528035195744206.670736714620419.731482897744207.979030106
#Sta/Elev= 30
9115.576507.71719162.784476.94069182.786461.80559212.787445.18829232.788429.8729
 9252.79421.98219282.791 400.3179312.793385.00259332.794377.98959382.794355.3576
9402.794  354.539422.795350.92749522.795349.15089612.806344.24719913.236341.5531
9943.322343.4011 9953.35339.81919963.354332.17899983.354 312.3879993.354309.1007
10003.36309.411210023.36316.267510043.44319.013810063.59328.694910124.02333.1822
10164.19342.5069 10204.3 362.24410224.34378.402810234.34380.730910329.63383.7179
#Mann= 3 , 0 , 0
9115.576  0.1006       09115.576  0.1006       010329.63  0.1006       0
#XS Ineff= 2 , 0
       0                               0
Bank Sta=9115.576,10329.63
Exp/Cntr=0.3,0.1

Type RM Length L Ch R = 1 ,22138.17,245.904900,245.904900,245.904900
XS GIS Cut Line= 6
621648.226242831  743920.0558723621428.065809994743922.110010611
621138.647329158743929.543236732620823.587581376743945.129758281
620651.932498969743960.341336065620444.986688113 743965.52024889
#Sta/Elev= 30
9068.783475.44749122.012433.68599132.012427.10219152.013 418.3279172.014401.7848
9202.015380.86739242.017355.06829252.017351.33449262.018351.40649302.023344.5733
9452.073342.70099502.089337.70579582.119335.69899822.412335.46919862.461335.8084
9892.498340.07729922.612338.52049932.652335.0301 9962.77312.6405 9972.81308.0792
10002.94306.688110033.05308.690110043.09312.394910063.16331.199810073.18331.4046
10093.18341.3668 10153.2363.234410173.21367.476410203.22379.353310273.25379.3652
#Mann= 3 , 0 , 0
9068.783   0.075       09068.783   0.075       010273.25   0.075       0
#XS Ineff= 2 , 0
       0                               0
Bank Sta=9068.783,10273.25
Exp/Cntr=0.3,0.1

Type RM Length L Ch R = 1 ,21892.26,245.905000,245.905000,245.905000
XS GIS Cut Line= 6
621663.038182606743688.002149049620854.793877951743712.259048955
620769.030149005743711.968820404620634.226920689743706.831775395
 620526.99628118743707.922583181620410.880498824743713.134447987
#Sta/Elev= 30
9050.678476.26429068.719459.98129078.721454.76449138.732396.06269158.735379.4781
9178.738  368.229198.742352.37029208.744349.50469288.786341.55359418.856338.2346
9468.883331.76839568.937332.85699668.991328.86679789.055328.41559879.093 332.992
9899.093336.68849929.093326.02869939.093326.96049949.097324.43059969.114310.1547
9979.123305.53329989.131305.276210059.18308.376610089.19318.412210109.19329.2064
 10159.2332.314210199.21350.348110229.24369.486510239.25371.627310303.43371.2545
#Mann= 3 , 0 , 0
9050.678  0.0866       09050.678  0.0866       010303.43  0.0866       0
#XS Ineff= 2 , 0
       0                               0
Bank Sta=9050.678,10303.43
Exp/Cntr=0.3,0.1

Type RM Length L Ch R = 1 ,21646.36,245.904900,245.904900,245.904900
XS GIS Cut Line= 6
621625.851307321743404.986651111621246.512674784743418.043816592
620896.939825249743439.277893233620799.718379579743449.752151427
620541.572201546743487.612012277620261.222044935743520.470422593
#Sta/Elev= 30
9066.389427.26149077.244426.63719087.247423.41369117.257423.3542 9127.26419.4617
9167.282399.01059197.302376.03729227.322356.69679247.335354.84669257.342351.7507
9417.449333.69299497.538328.86789808.208323.33349888.671324.4829 9918.96 322.659
9929.064325.40469939.169322.50359979.587305.02069989.692301.82049999.798301.7359
10040.23303.006110090.78311.553210100.88315.2621 10121.1325.947310171.58326.9156
10201.78329.713210242.06344.2163 10292.4358.002610342.74360.418310437.16359.8946
#Mann= 3 , 0 , 0
9066.389  0.1179       09066.389  0.1179       010437.16  0.1179       0
#XS Ineff= 2 , 0
       0                               0
Bank Sta=9066.389,10437.16
Exp/Cntr=0.3,0.1

Type RM Length L Ch R = 1 ,21400.45,245.905000,245.905000,245.905000
XS GIS Cut Line= 6
621555.445266614743178.122742171620925.281610945743202.016260238
620744.677520244743212.978292756620358.362504399743256.593598359
620259.999718932743269.964770247620052.411132396743305.859206941
#Sta/Elev= 30
9100.564478.60519141.038451.40799151.045442.79099161.052429.73449181.067421.8821
9201.081404.98659231.103370.98859261.124348.01179271.131338.41819291.146336.7826
 9311.16331.31949391.218326.60049541.325322.74339571.347324.72369661.412324.5105
9771.511 319.2789891.752321.28729901.779 317.7459911.806310.84269931.911309.2587
9982.175300.400510002.28299.465610032.48302.030510042.55 305.65210052.62317.0617
10082.82322.200510334.57325.359410445.76332.547810496.42345.116510610.86345.5713
#Mann= 3 , 0 , 0
9100.564   0.076       09100.564   0.076       010610.86   0.076       0
#XS Ineff= 2 , 0
       0                               0
Bank Sta=9100.564,10610.86
Exp/Cntr=0.3,0.1

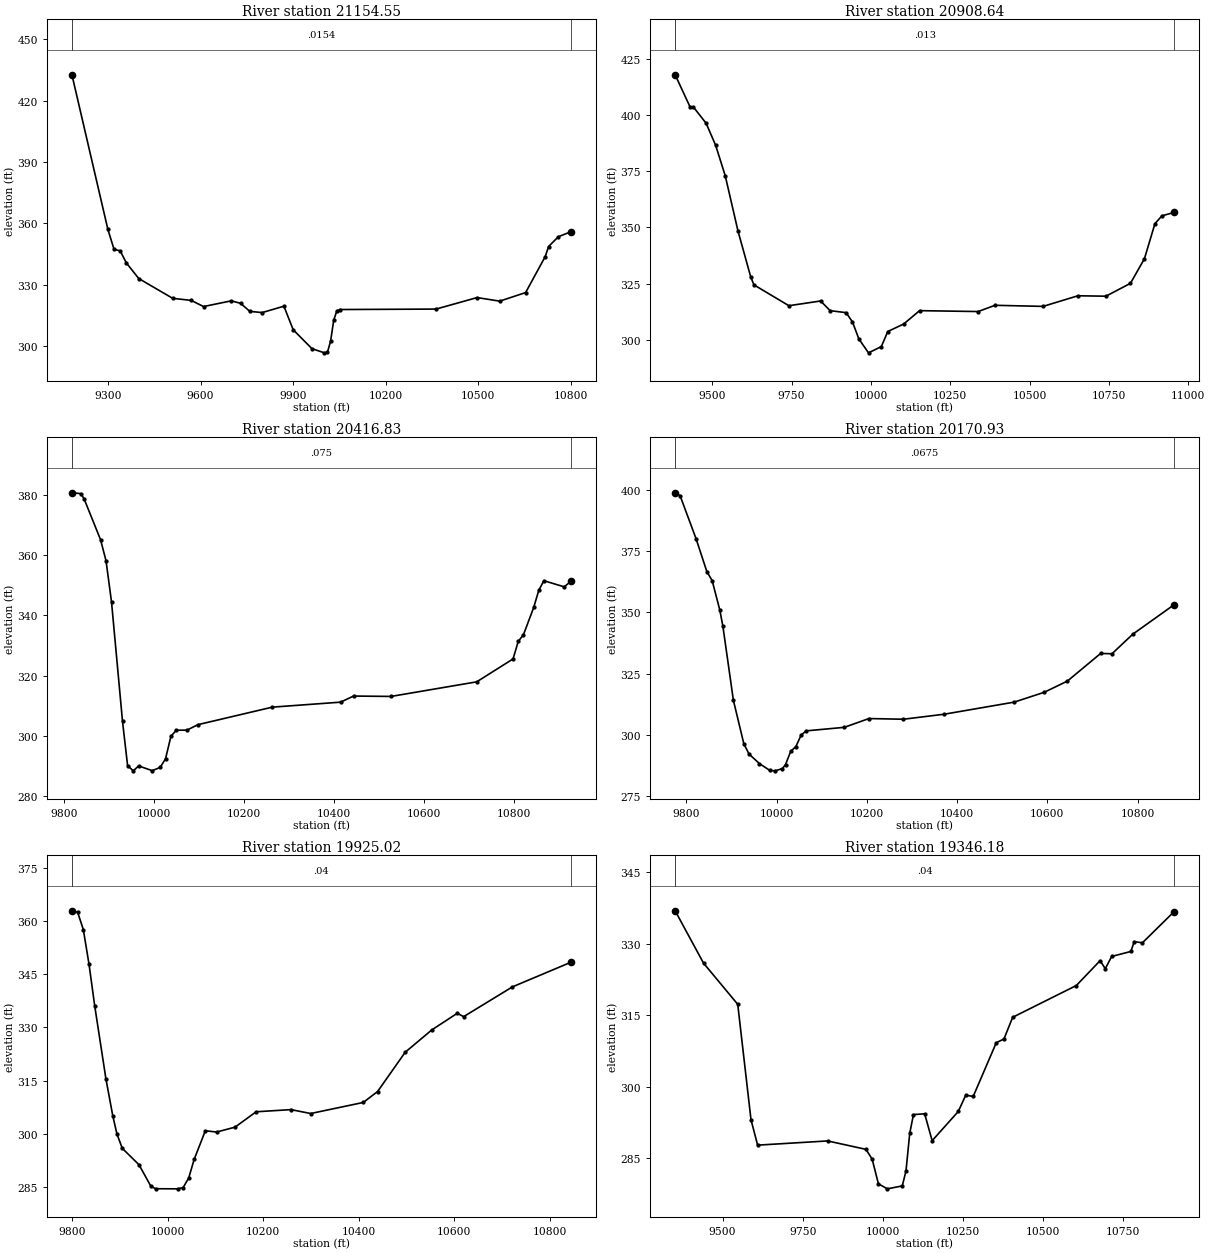
Type RM Length L Ch R = 1 ,21154.55,245.904900,245.904900,245.904900
XS GIS Cut Line= 6
621471.250279587742992.014281702620940.264829828743005.661794797
620430.979043579742960.123566588620294.306279882742974.771921768
620177.126071852743001.009714696619877.075607112743099.941326993
#Sta/Elev= 30
9183.064 432.7079299.468357.07889319.495347.25789339.521 346.4759359.548340.5792
9399.591332.94319509.646323.24559569.653322.23539609.658319.21689699.671322.0211
9729.703320.79779759.761316.85119799.839316.27119870.133319.39199900.317307.8419
9960.884298.610410001.32296.550610011.42 296.87210021.53 302.31110031.63312.5124
10041.73317.121710051.84317.757610363.11317.977910496.52 323.61510569.59321.8654
10653.61326.060110717.28 343.71610727.89 348.59310759.72353.406410799.96355.8108
#Mann= 3 , 0 , 0
9183.064  0.0154       09183.064  0.0154       010799.96  0.0154       0
#XS Ineff= 2 , 0
       0                               0
Bank Sta=9183.064,10799.96
Exp/Cntr=0.3,0.1

Type RM Length L Ch R = 1 ,20908.64,491.809900,491.809900,491.809900
XS GIS Cut Line= 6
 621322.09105669742724.653410495620912.625674899742754.495938655
 620602.41863957742723.527370106620503.027033213 742729.39992506
 620279.24687075742796.978386026619810.505277355743010.708757322
#Sta/Elev= 30
9383.257417.90019430.599403.48029440.652403.56379480.865 396.3289511.025386.4624
9541.178372.90939581.324348.34489621.458 327.9189631.477324.40619741.624315.1218
9841.666317.22079871.686 312.9159921.917312.03119942.023307.91229962.208300.3233
9992.571294.143510033.05296.926110053.28303.635410103.51306.987310153.52312.9172
10338.06312.522910391.08315.301810542.72314.820610652.54319.542710740.75319.3509
10817.94325.078210862.05336.014710895.13 351.63410917.18355.136410955.22356.6149
#Mann= 3 , 0 , 0
9383.257   0.013       09383.257   0.013       010955.22   0.013       0
#XS Ineff= 2 , 0
       0                               0
Bank Sta=9383.257,10955.22
Exp/Cntr=0.3,0.1

Type RM Length L Ch R = 1 ,20416.83,245.905000,245.905000,245.905000
XS GIS Cut Line= 6
620566.868742514742213.754652417620356.771281029742517.951292499
620234.272000629  742644.8968736620057.269458174742776.733181099
619959.336903487 742838.44178985619762.035538584 742947.75987976
#Sta/Elev= 30
9817.368 380.6959836.837380.4237 9844.17378.77079880.963365.1199 9893.19358.1127
9905.418344.38349929.817304.75459941.105290.0922 9953.73288.36049965.687289.9931
9995.829288.4169 10013.5289.499810025.44292.380710037.39299.831410049.33301.8383
10073.22301.8842 10097.1303.683610262.84309.5146 10414.5311.167810443.29313.1959
10526.61313.068810716.97317.912410797.76325.5189 10809.3331.343610820.84333.5322
10843.68342.628810854.97348.302310866.25351.5043 10911.4349.460310926.03 351.242
#Mann= 3 , 0 , 0
9817.368   0.075       09817.368   0.075       010926.03   0.075       0
#XS Ineff= 2 , 0
       0                               0
Bank Sta=9817.368,10926.03
Exp/Cntr=0.3,0.1

Type RM Length L Ch R = 1 ,20170.93,245.904900,245.904900,245.904900
XS GIS Cut Line= 6
620368.357092313742045.837065755620164.512162669 742384.18718202
  620049.4378024742539.674795992619891.256728901742694.350842684
619797.002717812742767.160704636619649.182709472742863.227532476
#Sta/Elev= 30
9775.198 398.6869786.075397.52839821.688379.9114 9845.43 366.581  9857.3362.8603
9874.217350.86879881.042344.26959904.231314.1729 9927.36296.47329938.924292.2319
9962.052288.32769985.181285.54219996.745285.387510013.06286.320910019.81287.9349
10031.34293.349810042.88295.286910054.41300.003410065.95301.680710150.19303.1148
10204.64306.692810280.99306.412210371.06308.444810526.63 313.38710593.32317.4066
10644.55321.9651 10718.2333.220510743.34333.090110789.42341.066910880.77353.0418
#Mann= 3 , 0 , 0
9775.198  0.0675       09775.198  0.0675       010880.77  0.0675       0
#XS Ineff= 2 , 0
       0                               0
Bank Sta=9775.198,10880.77
Exp/Cntr=0.3,0.1

Type RM Length L Ch R = 1 ,19925.02,578.840600,578.840600,578.840600
XS GIS Cut Line= 6
620140.097211243741944.917542783619950.343863774742261.462106446
 619818.41692112742438.119713933619733.157402475742528.775518443
619656.319314388742598.752376287619474.541600957742732.412709745
#Sta/Elev= 30
 9799.69362.87159811.667362.44119823.547357.57889835.426 347.8669847.305336.1596
9870.739315.61429885.092305.19149893.852300.02899905.041295.9697 9940.08291.3301
9964.888285.2932 9974.75284.583710020.94 284.55210032.49284.922210044.03 287.582
10055.58292.8701 10078.9300.915410102.42300.550310140.96301.921710185.27306.2595
10258.19306.866210299.38305.767910409.36308.882110439.35311.956910497.11323.0162
10552.87329.320710606.11333.998410619.55333.057210721.56341.439510843.66348.3559
#Mann= 3 , 0 , 0
 9799.69    0.04       0 9799.69    0.04       010843.66    0.04       0
#XS Ineff= 2 , 0
       0                               0
Bank Sta=9799.69,10843.66
Exp/Cntr=0.3,0.1

Type RM Length L Ch R = 1 ,19346.18,650.684200,650.684200,650.684200
XS GIS Cut Line= 4
620173.799999833741807.774227679619724.206187278741688.157525256
619324.108941227741927.390930086618802.928400338742273.701684266
#Sta/Elev= 30
9351.891336.86589440.469325.90099547.259317.27219588.651293.10279609.346 287.778
9827.852288.65979947.373286.89919966.859284.85129986.345279.678710014.27 278.626
10060.88279.240210072.53282.404210084.18290.280110095.83294.184210130.79294.3411
10154.09288.711710235.65294.829110258.95298.240910282.25297.979110354.26 309.229
10378.27310.017710405.45314.555810604.21321.212210678.43 326.42210694.56 324.731
10714.45327.296410774.48328.3485 10784.9330.4003 10810.5330.159710909.04336.6648
#Mann= 3 , 0 , 0
9351.891    0.04       09351.891    0.04       010909.04    0.04       0
#XS Ineff= 2 , 0
       09825.192                       0
Bank Sta=9351.891,10909.04
Exp/Cntr=0.3,0.1

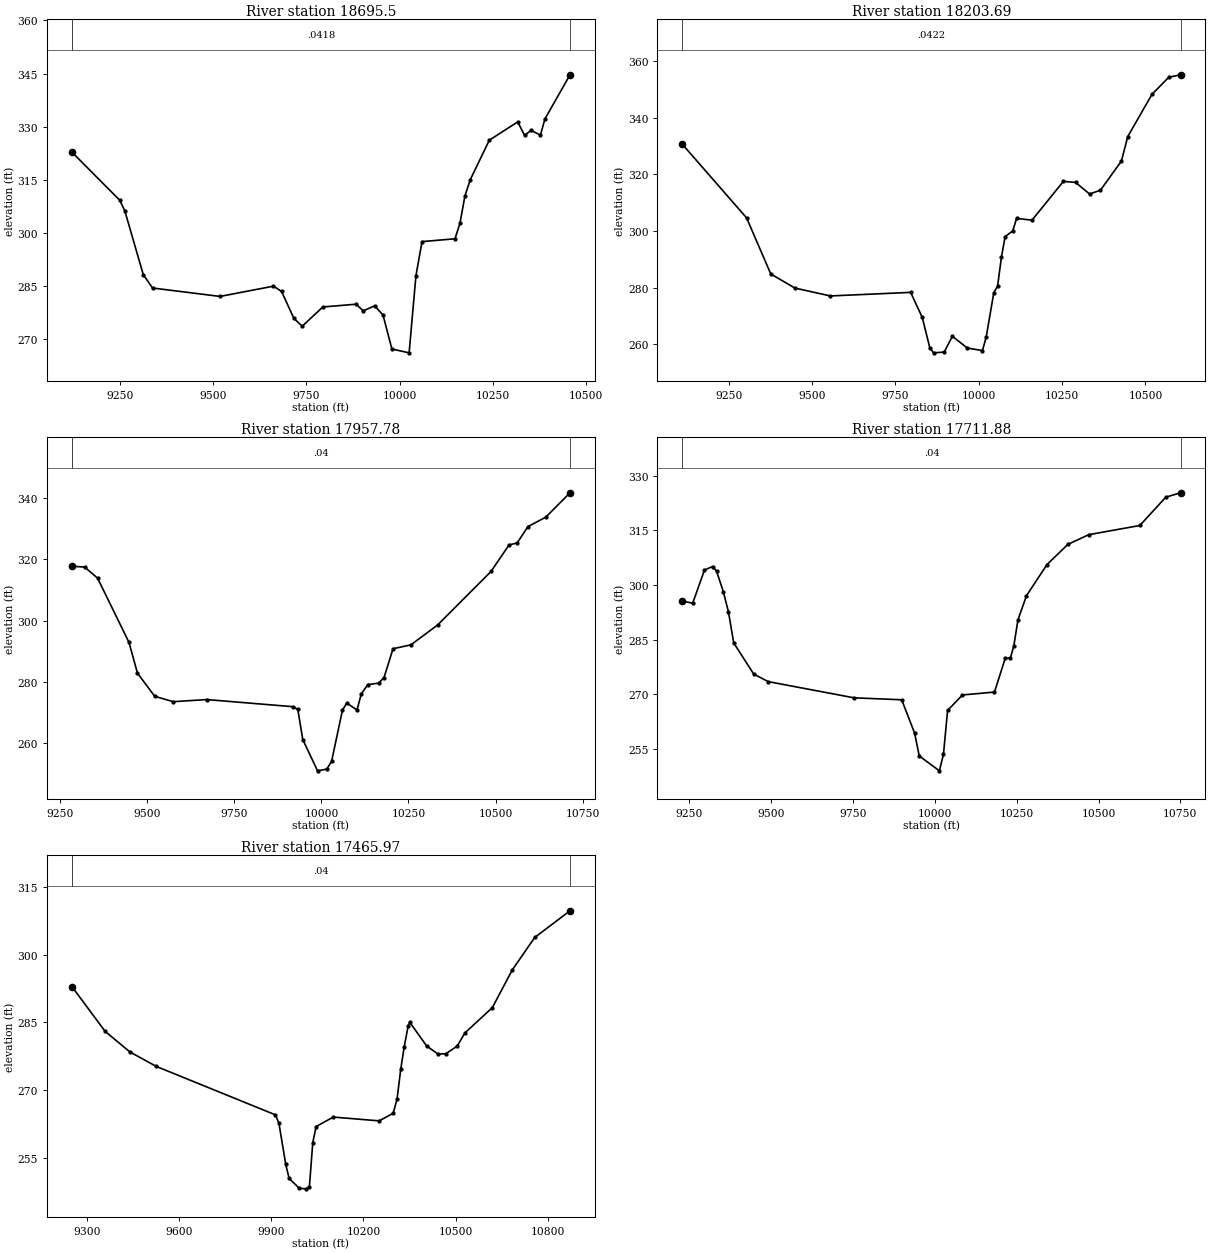
Type RM Length L Ch R = 1 , 18695.5,491.809900,491.809900,491.809900
XS GIS Cut Line= 6
620219.171852469741721.155236259619833.511666387741436.459465563
619715.643139899741390.899029404619616.209077001741326.454601094
619425.664184719741093.092355832 619178.63499999740907.091351658
#Sta/Elev= 30
9120.615322.83569248.842309.27249262.526306.30479312.244 288.2429337.103284.4667
9518.244 282.0929661.765284.98449683.387283.49379716.399275.91939738.779273.6815
9794.238279.11419883.419279.89119902.673278.01789933.322279.43139955.805276.8216
9979.581267.2353 10025.8266.164910044.05287.897510060.44297.566910148.83298.3579
10162.26 302.717 10175.7310.5121   10190315.056410240.98326.190110317.26331.3608
10335.67327.580410353.16328.948110378.21327.6329 10390.4332.209410457.63344.6597
#Mann= 3 , 0 , 0
9120.615  0.0418       09120.615  0.0418       010457.63  0.0418       0
#XS Ineff= 2 , 0
       09596.876                       0
Bank Sta=9120.615,10457.63
Exp/Cntr=0.3,0.1

Type RM Length L Ch R = 1 ,18203.69,245.905000,245.905000,245.905000
XS GIS Cut Line= 6
620516.151251584741618.037389338620071.041904926741193.178629011
 620015.97365436741105.774405658619819.661607981740748.553036898
619704.489136815740591.434983924619590.999852419740461.082373589
#Sta/Elev= 30
9111.053330.57879303.732304.58159376.148284.79279448.563 279.8139555.018277.0283
9795.699278.29569830.597269.43169853.173258.72869864.461256.93979896.491257.2157
9920.902262.78539966.054258.609510011.26257.746210022.58262.663110045.23278.2152
10056.55280.535610068.11290.7884 10079.2297.997210102.07300.010610113.57304.4463
10159.56303.769910253.92317.489510290.28317.132910332.43313.039210365.04314.3584
10427.87324.641410447.01333.314410519.49348.205910569.89 354.25110605.22355.1354
#Mann= 3 , 0 , 0
9111.053  0.0422       09111.053  0.0422       010605.22  0.0422       0
#XS Ineff= 2 , 0
       09740.615        10096.49       0
Bank Sta=9111.053,10605.22
Exp/Cntr=0.3,0.1

Type RM Length L Ch R = 1 ,17957.78,245.904900,245.904900,245.904900
XS GIS Cut Line= 6
620698.006690675741308.389409259620537.411902131741216.883757358
620385.198164738741085.654700891620082.641652108740771.821892482
 619828.46421915740456.974469685619694.643783828740303.313522864
#Sta/Elev= 30
9283.121 317.7439319.764317.47079356.787313.88389447.089292.89279471.394282.8819
9521.055275.29299574.051273.5377 9670.34274.22929917.968271.90489932.135 270.994
9946.302261.19519988.776250.967410015.44251.537910029.21254.108710060.17 270.722
10072.68 273.09310102.03270.811910114.39276.050510132.99279.121110164.16279.5794
10179.74281.415110205.66290.819310256.91292.086210333.64298.564210487.11 316.034
10538.89324.7041 10562.1325.334610593.14330.6701 10644.5333.774910713.95341.7167
#Mann= 3 , 0 , 0
9283.121    0.04       09283.121    0.04       010713.95    0.04       0
#XS Ineff= 2 , 0
       09877.357         10136.7       0
Bank Sta=9283.121,10713.95
Exp/Cntr=0.3,0.1

Type RM Length L Ch R = 1 ,17711.88,245.905000,245.905000,245.905000
XS GIS Cut Line= 6
620851.465472488741195.792433253620701.453574441741086.702837749
620466.247953364740846.353097929  620346.3736713 740708.63931522
619968.288484812740224.103719635619834.611361255740072.626219324
#Sta/Elev= 30
 9228.95295.55929260.483295.03079296.404304.1386  9321.2305.10049333.598303.7613
9353.759298.22789369.761292.59469385.611284.11769446.764 275.5369491.123273.4602
9753.063269.01179898.792268.46749938.336259.28399952.366253.030510013.95248.9377
10026.46253.540110038.97265.5433 10084.5269.794510182.21270.588910214.78279.8154
10231.07280.005810241.26283.255910253.93290.447210279.93297.072710342.63305.6312
10405.98311.1575 10470.1313.846610626.12316.372610705.45324.150710750.42325.3645
#Mann= 3 , 0 , 0
 9228.95    0.04       0 9228.95    0.04       010750.42    0.04       0
#XS Ineff= 2 , 0
       0 9834.68        10066.51       0
Bank Sta=9228.95,10750.42
Exp/Cntr=0.3,0.1

Type RM Length L Ch R = 1 ,17465.97,245.904900,245.904900,245.904900
XS GIS Cut Line= 6
620980.827603025741100.875840433620815.618067984740962.206590286
620682.792947027740810.998765255620373.554175642740263.200170272
620209.979911099740034.287044061620016.395796454739817.462429315
#Sta/Elev= 30
9251.826292.91739360.137282.97069440.983278.40669526.927275.20219913.872264.4834
9925.257262.58749947.335253.49449958.341250.4062 9991.36248.206510013.31248.0896
10024.29248.555210035.26258.357210046.23261.899610101.86263.992410250.89263.1566
 10296.7264.821810309.42268.007610321.48274.691410332.73279.5823 10345.6 284.243
10350.62284.996610405.89279.730310442.25277.968910467.31 278.01210504.91279.7084
10529.97282.641510619.15288.245710684.32296.630110757.05303.796410871.78309.7101
#Mann= 3 , 0 , 0
9251.826    0.04       09251.826    0.04       010871.78    0.04       0
#XS Ineff= 2 , 0
       09859.999        10083.96       0
Bank Sta=9251.826,10871.78
Exp/Cntr=0.3,0.1