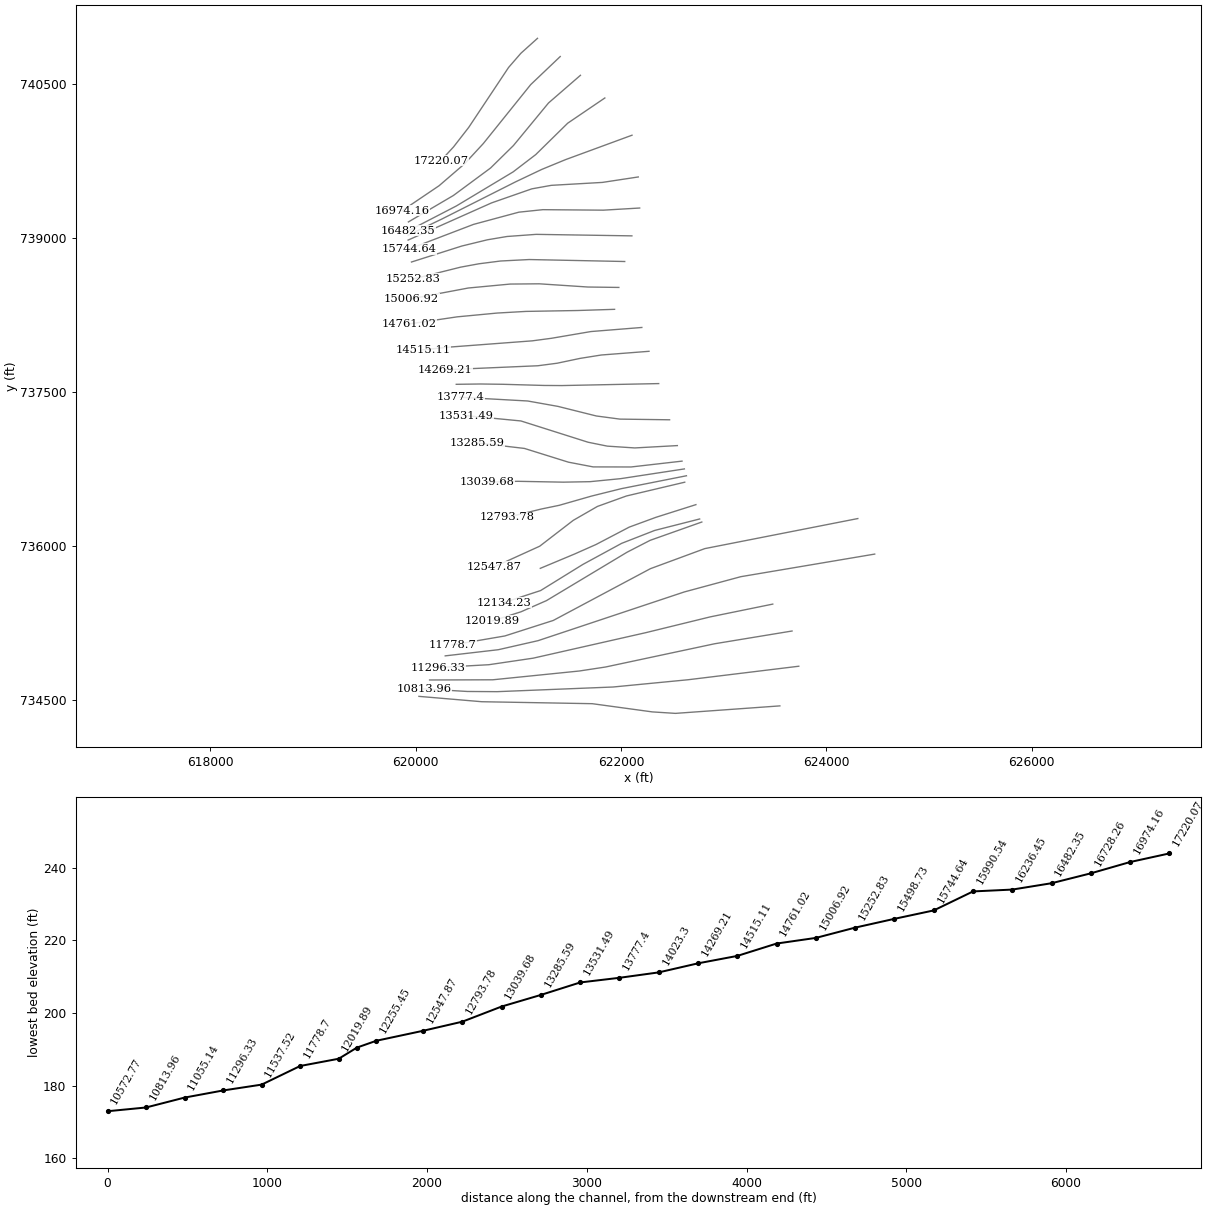
HEC-RAS study 3211_ras.prj: 3211

--- 3211_ras.g01 (geometry) --- (continued)

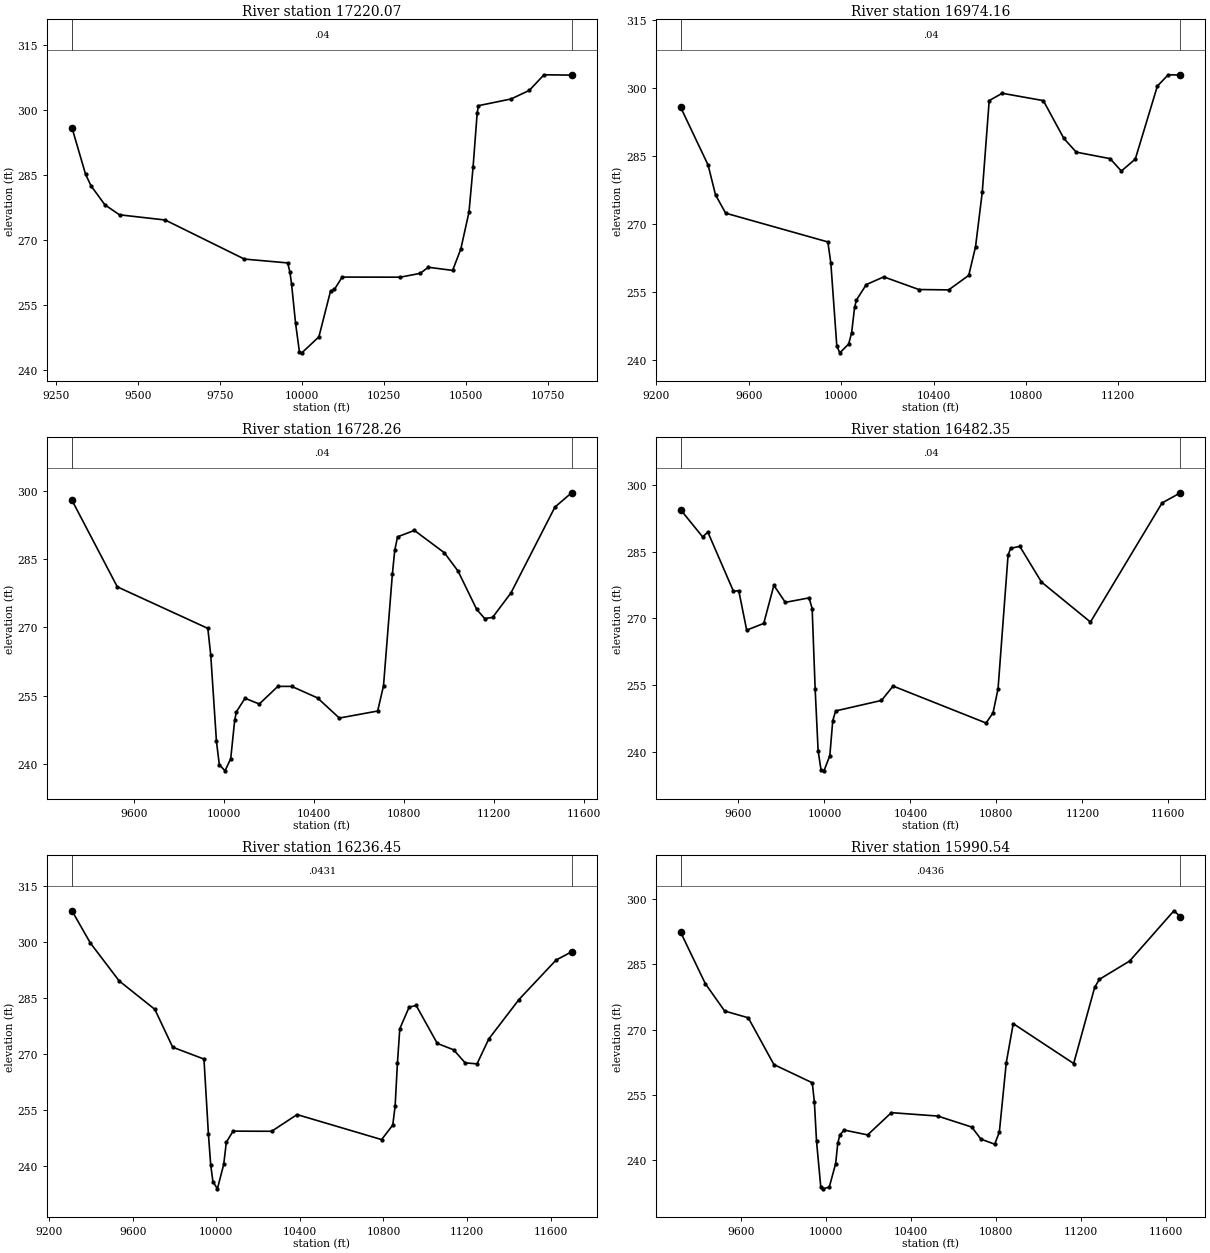
Type RM Length L Ch R = 1 ,17220.07,245.905000,245.905000,245.905000
XS GIS Cut Line= 6
621187.168536863  740949.4777588621025.321673901740803.913640852
620905.424719654740665.639610524620517.499685315740082.343090174
620369.129432384739891.395490376620247.158597065739759.044172593
#Sta/Elev= 30
9298.188295.90199339.513285.19099356.169282.51529398.795278.09229443.166275.8063
9582.442274.60889823.938 265.5939955.866264.7094 9962.72 262.6239967.842259.7852
9979.817250.88419991.793244.13279999.072243.965610051.09 247.656 10086.6258.2238
10098.44258.601510122.11261.440310299.67261.420810360.26262.306410384.51263.7116
10458.87 262.979 10483.8267.913210508.73276.419210521.19286.824110533.75299.3135
10537.67300.985610637.08302.5287 10692.7304.5114 10737.5308.109710821.75308.0315
#Mann= 3 , 0 , 0
9298.188    0.04       09298.188    0.04       010821.75    0.04       0
#XS Ineff= 2 , 0
       09899.889        10118.63       0
Bank Sta=9298.188,10821.75
Exp/Cntr=0.3,0.1

Type RM Length L Ch R = 1 ,16974.16,245.904900,245.904900,245.904900
XS GIS Cut Line= 6
621408.627371824740772.191883534621121.090112453 740498.74960923
620659.147281287 739924.34858093620477.189894807739727.647539412
620228.561043678739513.737245835619869.994618782739271.451566886
#Sta/Elev= 30
 9305.52295.76139423.923283.05129456.131276.46729499.875272.43049942.517266.0773
9955.427261.41599981.245243.14329994.155241.593510032.61243.539510045.41245.9994
10058.21251.619510066.27253.244210108.89256.664310184.77258.363910336.53 255.571
10465.66255.4895 10552.6258.701510581.89264.969610611.19277.0844 10641.2297.2869
10697.74298.898210875.63297.274410964.34288.940811018.16285.900211164.73284.4658
 11213.5 281.72411273.92284.376111369.47 300.49211416.43302.981511469.28302.9261
#Mann= 3 , 0 , 0
 9305.52    0.04       0 9305.52    0.04       011469.28    0.04       0
#XS Ineff= 2 , 0
       0 9880.88        10105.61       0
Bank Sta=9305.52,11469.28
Exp/Cntr=0.3,0.1

Type RM Length L Ch R = 1 ,16728.26,245.905000,245.905000,245.905000
XS GIS Cut Line= 6
621605.455150114740589.346406432621294.435850079740319.784842183
 620952.51790623739904.804239781620730.279513887739686.486596239
620367.931343966739418.596248557 619929.63694697 739161.00848095
#Sta/Elev= 30
 9323.49297.98019525.051278.94049927.494269.80439940.436 263.9349965.823244.9598
9978.516239.835710003.89238.4822 10029.3 241.16710046.85249.5898 10054.7 251.485
 10092.8254.437510156.31253.1786 10238.9257.058310300.53257.045610415.06254.5194
10512.03250.088410682.51251.634110708.47257.176610747.86281.7265 10758.4286.9704
10770.89289.934710845.79291.3457 10979.3  286.4211039.77282.405811122.83273.9737
11158.16271.977511193.31272.208911274.98277.600811470.63 296.48311544.84299.6213
#Mann= 3 , 0 , 0
 9323.49    0.04       0 9323.49    0.04       011544.84    0.04       0
#XS Ineff= 2 , 0
       09868.562        10108.93       0
Bank Sta=9323.49,11544.84
Exp/Cntr=0.3,0.1

Type RM Length L Ch R = 1 ,16482.35,245.904900,245.904900,245.904900
XS GIS Cut Line= 6
621843.178379249740368.510619802621481.600963285 740122.98440961
621170.244669896 739817.15265276620949.454338744739648.298028102
620396.374205441739316.363241347619928.298802319739074.029077837
#Sta/Elev= 30
9331.435294.37929433.519288.30319457.313 289.4129576.687276.09219601.309276.2323
9638.242267.37019717.565268.87279764.754277.43279817.898273.60169928.546274.6159
9942.811 272.2069956.796254.13529970.578240.25799984.162235.94219997.846235.7546
10025.03239.162310038.63247.017610052.24249.214710265.33 251.569 10319.4254.8011
10752.01 246.49710784.53248.796610807.77254.185210854.27284.145310865.89285.7488
10908.96286.181411009.65278.178911237.66269.186611570.89295.936811656.34298.2248
#Mann= 3 , 0 , 0
9331.435    0.04       09331.435    0.04       011656.34    0.04       0
#XS Ineff= 2 , 0
       09895.032        10146.95       0
Bank Sta=9331.435,11656.34
Exp/Cntr=0.3,0.1

Type RM Length L Ch R = 1 ,16236.45,245.905000,245.905000,245.905000
XS GIS Cut Line= 6
 622107.96030119740005.861153265621460.728192656739768.030704272
621229.682282979 739673.04849212620973.659599808739551.452273797
620255.831090475739189.439667736619927.652455035739032.016503975
#Sta/Elev= 30
9309.408308.30899397.281299.70749535.133289.57349705.836281.97379791.346271.8505
 9940.99268.68639962.368248.58059973.056240.50179983.745235.951610005.14234.0023
 10035.5240.535610047.95246.457310080.18249.419610265.02249.385610386.38253.8478
10790.91247.162710844.38251.044110855.58256.070210866.78267.674510877.98276.7916
10922.78282.571910956.38282.9997 11057.4272.862411135.58 271.15411190.65267.6698
11247.57267.398311303.57274.039211448.31284.597911625.85295.148111700.23297.3439
#Mann= 3 , 0 , 0
9309.408  0.0431       09309.408  0.0431       011700.23  0.0431       0
#XS Ineff= 2 , 0
       09888.741        10157.88       0
Bank Sta=9309.408,11700.23
Exp/Cntr=0.3,0.1

Type RM Length L Ch R = 1 ,15990.54,245.904900,245.904900,245.904900
XS GIS Cut Line= 6
622168.848579507 739599.21443733621819.030504449739546.017326161
621321.940331698739517.546025457621131.573892224739483.257294901
 620740.09260449739346.642782477619926.917989112738984.276218545
#Sta/Elev= 30
9318.229292.33719433.678280.59919524.777274.30429635.804 272.753 9756.55262.0137
9936.972257.83759946.973253.37559956.975244.43959976.977233.92939986.979233.4909
10016.98233.895410046.99239.273110056.99243.974810066.99 245.877   10087246.9842
10197.42245.871910309.14250.977310527.33250.195710687.38247.668710730.46244.9058
10795.28243.738510817.09246.5122 10849.8262.472510882.51271.404411166.83262.2538
 11265.6279.723611287.54281.5674 11430.2285.778611638.51297.311811669.11295.9592
#Mann= 3 , 0 , 0
9318.229  0.0436       09318.229  0.0436       011669.11  0.0436       0
#XS Ineff= 2 , 0
       09882.129        10136.95       0
Bank Sta=9318.229,11669.11
Exp/Cntr=0.3,0.1

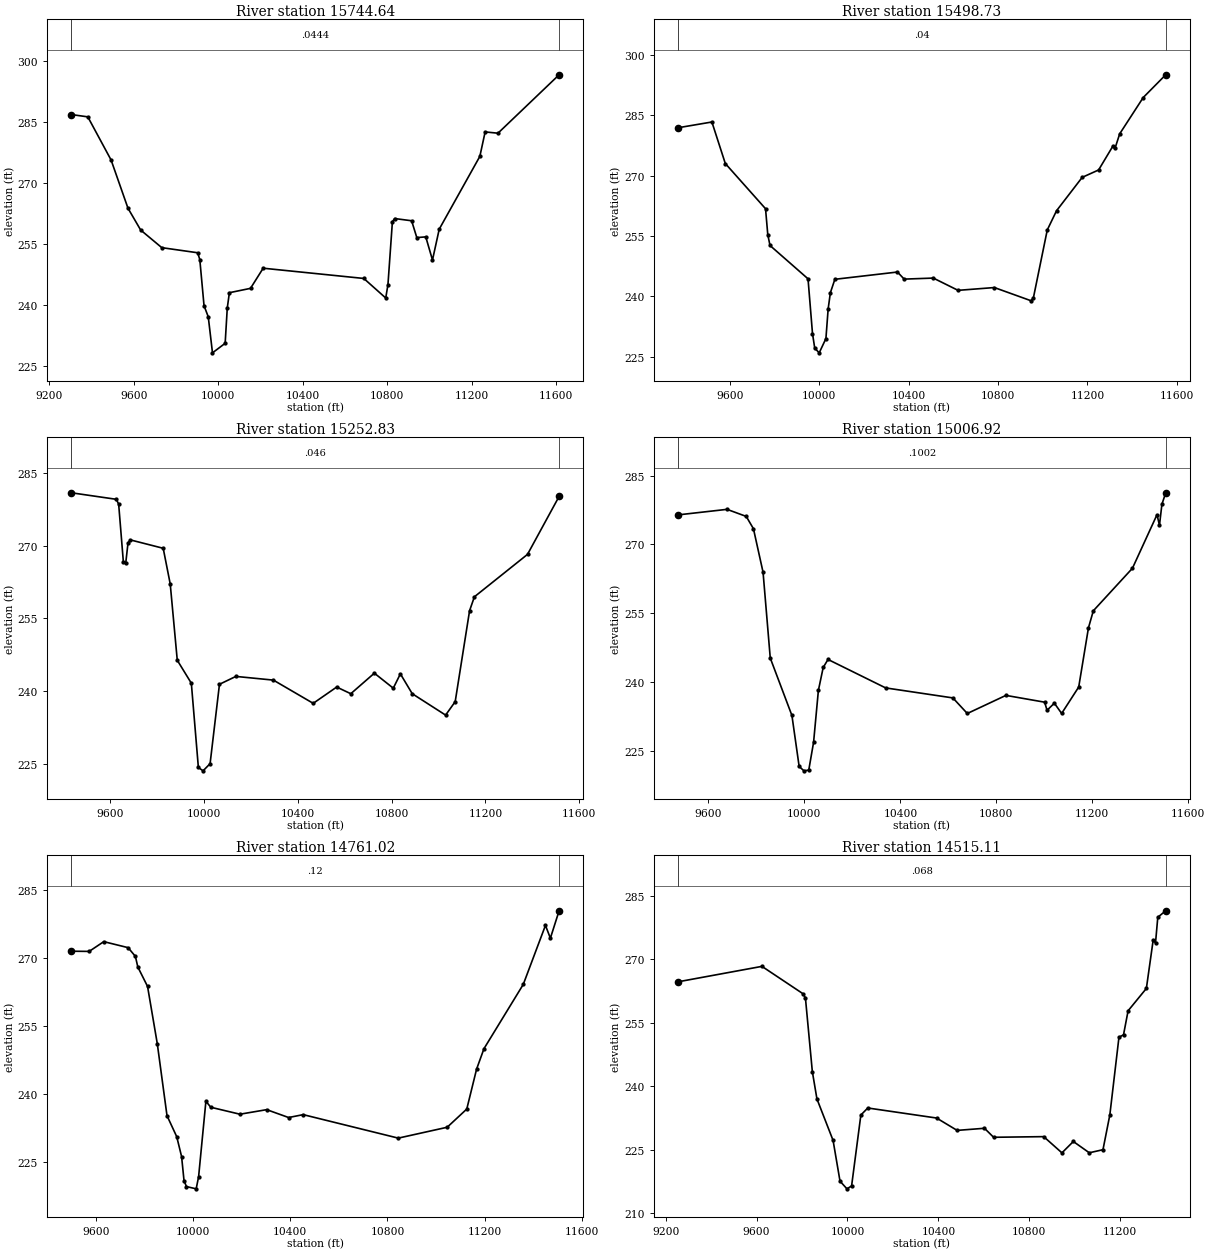
Type RM Length L Ch R = 1 ,15744.64,245.905000,245.905000,245.905000
XS GIS Cut Line= 6
 622182.60248769739296.588917605621828.904489964739275.719837584
621239.447729725739280.548687102621005.736854019739256.139693803
620563.771224818739137.033642513619935.552212271738896.916407943
#Sta/Elev= 30
9304.923286.83399382.763286.2703 9493.05275.66179573.121263.79629633.174258.4431
9733.198254.11459903.223252.85919913.226251.18089933.232239.84639953.238237.1142
9973.243228.257910033.26230.603610043.26239.263410053.26243.040610153.28244.1107
10213.29249.062510689.83 246.54410793.75241.736410804.26245.053210825.28260.4838
10835.79261.2726 10916.3260.725810940.89256.591310983.31256.761711015.13251.0787
11047.03258.6587 11239.4  276.5511264.45282.564811325.28282.251411614.77296.6134
#Mann= 3 , 0 , 0
9304.923  0.0444       09304.923  0.0444       011614.77  0.0444       0
#XS Ineff= 2 , 0
       09901.293        10120.55       0
Bank Sta=9304.923,11614.77
Exp/Cntr=0.3,0.1

Type RM Length L Ch R = 1 ,15498.73,245.904900,245.904900,245.904900
XS GIS Cut Line= 6
622106.721396434739025.354378617621174.024685613739040.007826703
620890.401426145739019.268553149620699.679031953738987.136641774
620449.558388404738926.218146898  619959.6909414 738770.65228629
#Sta/Elev= 30
9367.846281.89419519.602283.32719579.605273.0081 9759.63261.76979769.632255.3478
9779.633252.62889949.766244.34749969.783230.73199979.792 227.1069999.809225.9453
10029.83229.493210039.84236.874910049.85240.902910069.86244.224410349.95246.0326
10379.97244.271810510.36244.529210621.16241.479310783.63242.1754 10947.9238.8884
10958.24239.618711020.34256.495111061.88261.273111176.63269.567811250.03271.4039
11312.94277.243111323.43276.7729 11344.4280.386711449.74289.412911550.36295.0654
#Mann= 3 , 0 , 0
9367.846    0.04       09367.846    0.04       011550.36    0.04       0
#XS Ineff= 2 , 0
       09913.046        10141.14       0
Bank Sta=9367.846,11550.36
Exp/Cntr=0.3,0.1

Type RM Length L Ch R = 1 ,15252.83,245.905000,245.905000,245.905000
XS GIS Cut Line= 6
622036.836877847738775.554397256621106.440384732738794.792958759
620826.904935021738780.374333203620615.878910874738753.270116944
620439.168695723738720.742148962619975.088133685738604.921715122
#Sta/Elev= 30
9433.208280.93649625.059279.58819635.061 278.5899655.064266.67919665.065266.3385
9675.067270.61589685.068271.20569825.139 269.4759855.156262.10569885.173246.3551
9945.206241.61969975.223224.22099995.234223.523410025.25225.002310065.26241.3947
10135.29243.019510295.32242.257110465.36237.460710565.53240.823110625.71239.4471
10726.29243.688110807.05240.590410837.34243.545610887.97239.448111030.39235.0315
 11071.3237.8108 11132.7256.594611153.23259.456611379.92268.219211514.75280.1843
#Mann= 3 , 0 , 0
9433.208   0.046       09433.208   0.046       011514.75   0.046       0
#XS Ineff= 2 , 0
       0                10142.38       0
Bank Sta=9433.208,11514.75
Exp/Cntr=0.3,0.1

Type RM Length L Ch R = 1 ,15006.92,245.904900,245.904900,245.904900
XS GIS Cut Line= 6
621979.472461039 738523.01945695621678.753391775738527.028348463
621204.949482805738558.339338939620921.577533676738555.897158631
620513.601046708738517.466085282619959.530318749738413.041997642
#Sta/Elev= 30
9473.175276.4405 9677.66277.64719757.701276.10619787.728273.42399827.785263.9572
9857.828245.25419948.109232.74459978.203221.65079998.266220.688210018.33220.8567
10038.38226.905510058.44238.2169 10078.5 243.20910098.55244.948410338.81238.7519
10619.01236.572910679.19233.178810840.04237.122911001.46235.643511011.57233.8782
11041.93235.4247 11072.4 233.19111143.51 238.94611184.14251.840511204.45255.5509
11367.51264.820111469.86276.4814 11480.1274.183911490.34278.746711506.18281.2562
#Mann= 3 , 0 , 0
9473.175  0.1002       09473.175  0.1002       011506.18  0.1002       0
#XS Ineff= 2 , 0
       0                10113.57       0
Bank Sta=9473.175,11506.18
Exp/Cntr=0.3,0.1

Type RM Length L Ch R = 1 ,14761.02,245.905000,245.905000,245.905000
XS GIS Cut Line= 6
621938.195394202738309.754611693621579.262196103738298.210608278
621074.587827644738289.488485336620795.064160313738273.506111295
620404.371139834738236.448773267619939.631047996738167.617658431
#Sta/Elev= 30
9499.965271.56739573.218271.52849633.265273.68039733.314272.35679763.324270.4325
9773.327268.0865 9813.34263.79639853.353251.17759893.356235.27329933.356230.6367
9953.357226.25089963.357220.93929973.357219.631710013.36219.131310023.36221.8123
10053.36238.465510073.36237.135410193.38235.599710303.44236.605210393.52234.8691
10453.61235.503410844.63230.322811045.78232.720911126.41236.7378 11166.8 245.552
11197.13250.058711358.85264.251611450.05277.267411470.33274.444411506.19280.4922
#Mann= 3 , 0 , 0
9499.965    0.12       09499.965    0.12       011506.19    0.12       0
#XS Ineff= 2 , 0
       0                10085.53       0
Bank Sta=9499.965,11506.19
Exp/Cntr=0.3,0.1

Type RM Length L Ch R = 1 ,14515.11,245.904900,245.904900,245.904900
XS GIS Cut Line= 6
622203.461928007738133.095083957621707.756020822738093.281938622
 621324.10197878738027.837672969621135.800476444738002.735177931
620329.145678518737941.836391552 620070.33377463737915.683373319
#Sta/Elev= 30
9254.231264.63749623.651268.28819804.888261.79829814.983260.79949845.271243.4489
9865.546236.96949936.554227.17139967.107217.5377 9997.66215.726410018.05216.4117
 10058.8233.161510089.24234.828510391.93232.455910482.29229.534710602.65230.0353
10642.74 227.90710863.23228.058810943.41224.227710993.57226.913211063.78224.2465
11123.97224.971711154.09233.173611194.29251.544711214.38252.123511234.48257.7936
11314.88263.071811345.03274.575411355.08273.803911365.13279.889511400.01281.4222
#Mann= 3 , 0 , 0
9254.231   0.068       09254.231   0.068       011400.01   0.068       0
#XS Ineff= 2 , 0
       0                10090.05       0
Bank Sta=9254.231,11400.01
Exp/Cntr=0.3,0.1

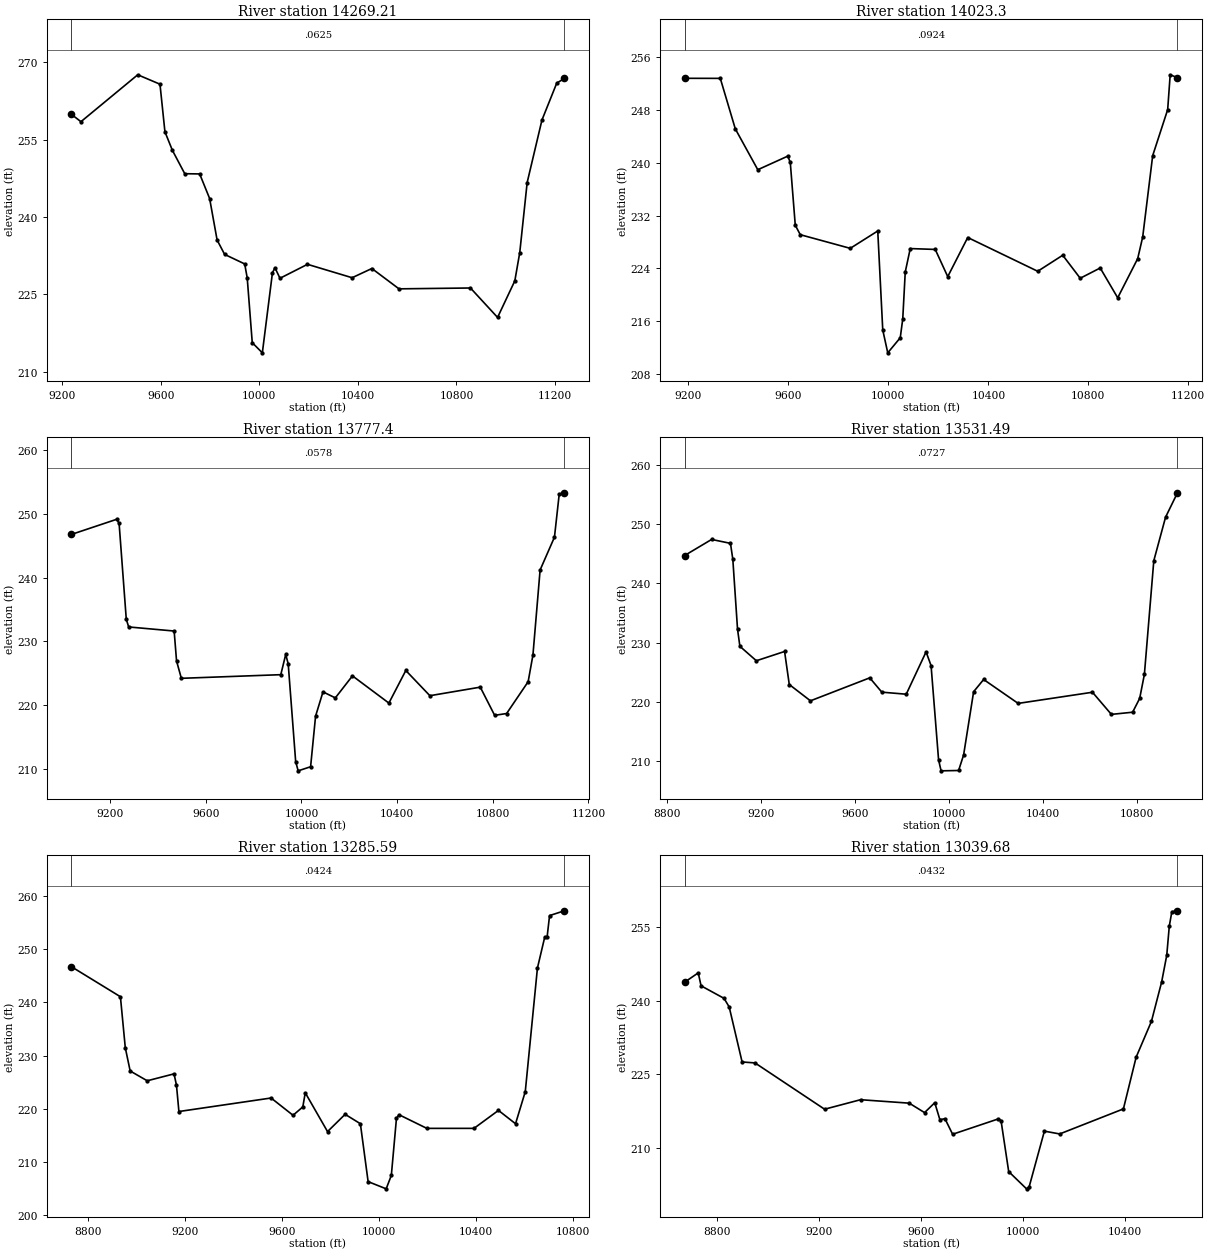
Type RM Length L Ch R = 1 ,14269.21,245.905000,245.905000,245.905000
XS GIS Cut Line= 6
622273.321080825737900.844040824 621808.81575612737864.858535796
621602.746498706737831.996967175621378.919125722737784.814743344
621190.597637934737760.111567847620284.054142741737720.833877901
#Sta/Elev= 30
9237.449259.87049275.837258.46129506.349267.54829596.643265.72369616.733256.5047
9646.911252.92429697.207248.38349757.775248.34069798.171  243.589828.556235.5357
9859.041232.75239940.535230.90589950.769228.20179971.236 215.65210012.19213.6835
10053.18229.1885 10063.4230.170610083.78228.126210195.46230.8303 10376.6 228.234
 10456.8230.019610566.91226.079810857.04 226.245 10967.1220.543411037.15227.6311
11057.17233.1172 11087.2246.672111147.26258.781911207.38265.942611238.38266.8335
#Mann= 3 , 0 , 0
9237.449  0.0625       09237.449  0.0625       011238.38  0.0625       0
#XS Ineff= 2 , 0
       09915.865           10122       0
Bank Sta=9237.449,11238.38
Exp/Cntr=0.3,0.1

Type RM Length L Ch R = 1 , 14023.3,245.904900,245.904900,245.904900
XS GIS Cut Line= 6
 622367.90964309737586.378557512 621424.30853332737567.110055622
621251.602469632737568.223626813620851.766947604737579.482493605
620631.514997438737582.437327649620395.838498735737579.364757629
#Sta/Elev= 30
9184.357252.84039327.333252.83069387.358245.17179477.364238.97129597.373 241.032
9607.374 240.0829627.375230.54579647.377229.11399847.395227.04219957.437 229.676
9977.444  214.669997.452211.188110047.47213.472710057.47216.333910067.47223.4553
10087.48227.0084 10187.5 226.876 10237.5222.7516 10317.5228.686910597.62223.5633
10697.66225.996610767.66222.503710847.67224.061210917.68219.539310997.68225.4829
11017.68228.762611057.68241.111111117.69248.092911127.69253.375611156.86252.9341
#Mann= 3 , 0 , 0
9184.357  0.0924       09184.357  0.0924       011156.86  0.0924       0
#XS Ineff= 2 , 0
       09940.453        10163.28       0
Bank Sta=9184.357,11156.86
Exp/Cntr=0.3,0.1

Type RM Length L Ch R = 1 , 13777.4,245.905000,245.905000,245.905000
XS GIS Cut Line= 6
 622473.97307315 737233.76417162621989.866343293737240.353700992
 621760.27723218  737270.8974664621385.780851893737364.416542711
621091.400438553737416.919706656620433.436571811737453.300630199
#Sta/Elev= 30
9038.558246.81059227.601249.18359237.602248.54099267.603233.49429277.603232.2827
9467.781231.64239477.806226.94399497.855224.22069913.685224.7906 9934.27227.9679
9944.666226.49969975.854211.16089986.251209.696110038.31 210.33810059.13218.2849
 10090.1222.0905 10141.7221.147910213.34224.602610365.66220.332210436.41225.4481
10537.04221.490210747.77222.833710807.85218.410610857.91218.693210947.94223.6882
10967.94227.867110997.95241.225611057.95246.373111077.96253.167311099.52253.3443
#Mann= 3 , 0 , 0
9038.558  0.0578       09038.558  0.0578       011099.52  0.0578       0
#XS Ineff= 2 , 0
       09934.993        10187.18       0
Bank Sta=9038.558,11099.52
Exp/Cntr=0.3,0.1

Type RM Length L Ch R = 1 ,13531.49,245.904900,245.904900,245.904900
XS GIS Cut Line= 6
622549.559156084736982.473597662622134.897524208736959.582350354
621867.592085461736977.087083772621680.279501371737015.008617184
621025.786783836737222.411400632620494.419396564 737273.86030527
#Sta/Elev= 30
8876.433244.70698991.464247.42299071.658246.76439081.672244.0806  9101.7232.2896
9111.714229.4082 9181.77226.97179301.795228.53519321.798222.96569411.891220.2175
9664.086224.09079715.445221.6771 9819.24221.33249903.684  228.479924.918226.1504
9956.854210.2644  9967.5208.413810042.03208.471710063.33211.089510105.92221.7545
10148.52223.812510295.34 219.78210611.36221.664410691.83217.931410782.18218.2959
10812.22220.625110832.25224.670410872.31243.842410922.38251.180110972.97255.2899
#Mann= 3 , 0 , 0
8876.433  0.0727       08876.433  0.0727       010972.97  0.0727       0
#XS Ineff= 2 , 0
       09918.772        10170.12       0
Bank Sta=8876.433,10972.97
Exp/Cntr=0.3,0.1

Type RM Length L Ch R = 1 ,13285.59,245.905000,245.905000,245.905000
XS GIS Cut Line= 6
622595.113618126736831.024991405622097.986275638736774.112924725
621729.295515855736774.777770965621488.739833783736820.872564028
621059.811595067736954.797479271620593.893422053737009.468816524
#Sta/Elev= 30
8730.306246.67218932.195241.04268952.313231.46118972.431227.10359042.843225.2645
 9153.49226.5636 9163.54224.44039173.572219.49459554.047 222.0319644.571218.7857
9684.936220.35849695.027223.01469786.969215.72419859.528218.96839922.513217.2021
9954.433206.332510028.97204.977710050.28207.508610071.36218.185110081.89 218.894
10196.92216.329410391.38216.331510492.37219.704810562.84217.198110603.03223.2222
 10653.2246.426510683.25252.224810693.27252.301210703.29256.2783 10764.5257.1801
#Mann= 3 , 0 , 0
8730.306  0.0424       08730.306  0.0424       0 10764.5  0.0424       0
#XS Ineff= 2 , 0
       0 9886.58        10107.15       0
Bank Sta=8730.306,10764.5
Exp/Cntr=0.3,0.1

Type RM Length L Ch R = 1 ,13039.68,245.904900,245.904900,245.904900
XS GIS Cut Line= 6
622617.933182808736755.159947422621998.033024646736660.447672558
621698.667102143736630.943907659621439.506139968736626.235273043
620991.977222809736634.542630468620692.980452936736626.292444079
#Sta/Elev= 30
8671.864243.70578725.461245.61158736.632242.98028826.715240.43888846.965238.6898
8897.592227.52768948.219227.33469221.258217.93779362.423219.86799553.366219.1673
9613.519217.25169653.548 219.2569673.563215.82969693.577216.00929723.599212.8549
9903.615215.98469913.618215.61399943.627205.278610013.65201.779910023.65202.1437
10083.68213.489110143.69212.919310393.71218.002210443.72228.505710503.74235.7773
10543.77 243.76710563.79249.1816 10573.8255.111510583.81258.027910605.85258.2108
#Mann= 3 , 0 , 0
8671.864  0.0432       08671.864  0.0432       010605.85  0.0432       0
#XS Ineff= 2 , 0
       09880.553        10103.96       0
Bank Sta=8671.864,10605.85
Exp/Cntr=0.3,0.1

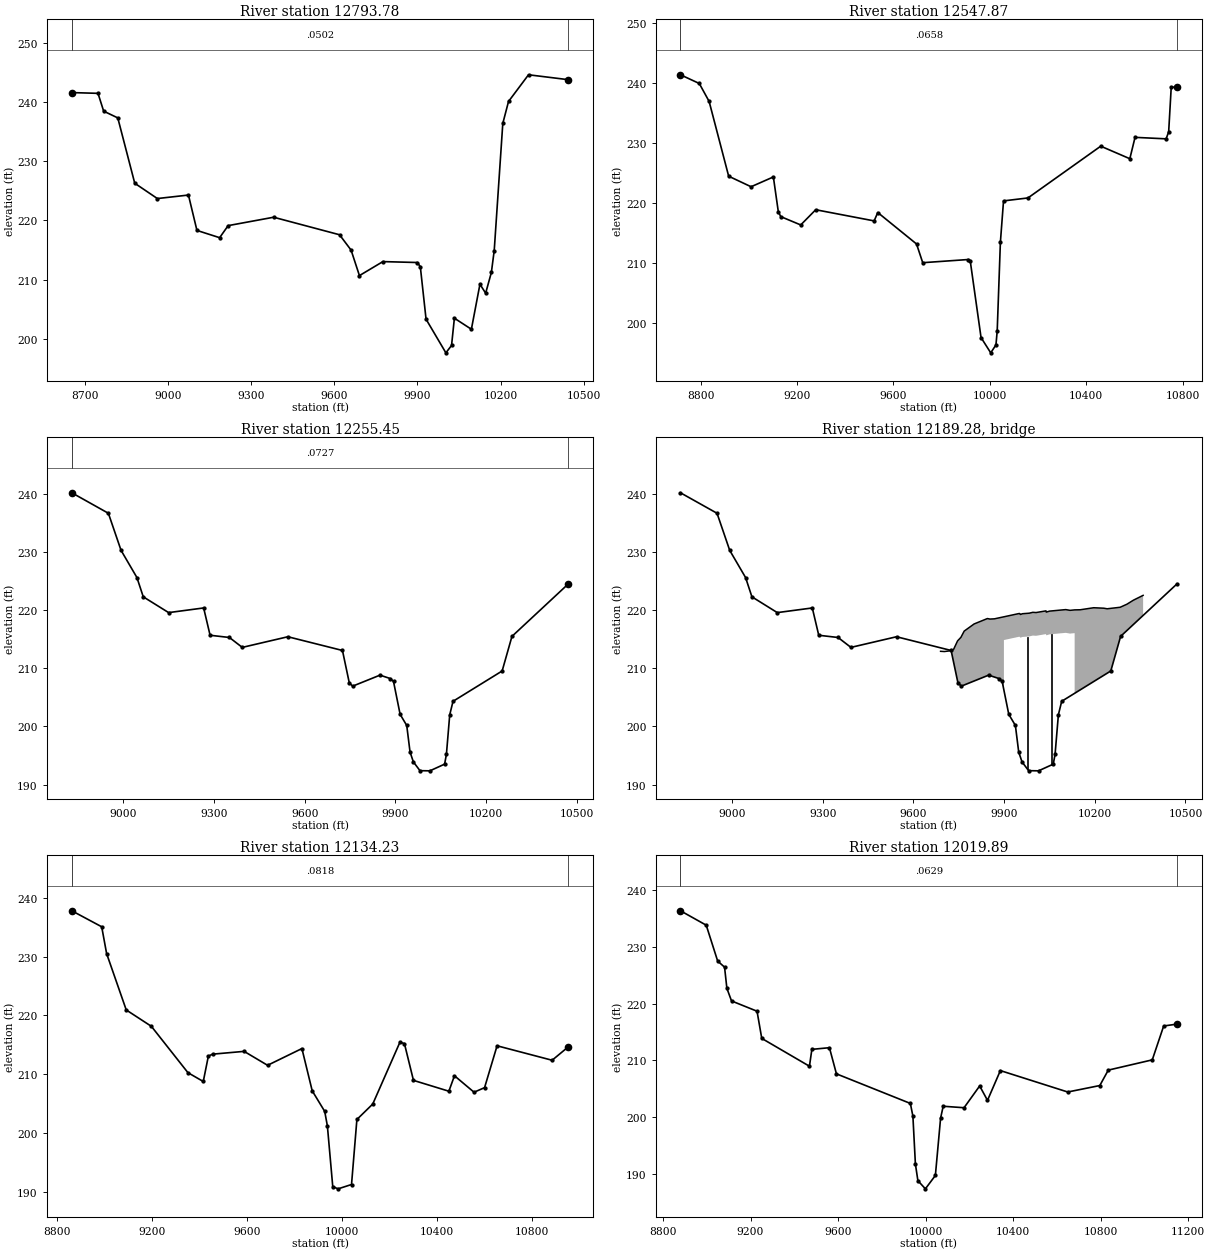
Type RM Length L Ch R = 1 ,12793.78,245.905000,245.905000,245.905000
XS GIS Cut Line= 6
622637.988286374736688.485524164622003.636244498736562.807750124
621713.474777158736490.634308782 621398.73003213736400.699050936
621227.272946034736365.195931274620895.355737184736284.249710114
#Sta/Elev= 30
 8654.09241.62288748.533241.49418768.891238.48368819.832237.34098880.961226.2889
8962.466223.70039074.535224.29249105.131218.30939186.938 217.0819217.615219.1202
9381.624220.54039619.099217.57749660.787  214.989690.838210.66879775.431213.0361
9900.052212.88099910.391212.15279931.019203.293410002.47197.6053 10022.9198.8525
10033.12 203.46410094.41201.594510125.24209.210210145.84207.690710166.44211.2078
10176.73214.910610207.63236.406110228.23240.114710300.31244.633910443.96243.8033
#Mann= 3 , 0 , 0
 8654.09  0.0502       0 8654.09  0.0502       010443.96  0.0502       0
#XS Ineff= 2 , 0
       09857.062        10187.79       0
Bank Sta=8654.09,10443.96
Exp/Cntr=0.3,0.1

Type RM Length L Ch R = 1 ,12547.87,292.417900,292.417900,292.417900
XS GIS Cut Line= 6
622621.439349884736625.807366221622054.063069999736491.706663296
621771.093148649736389.831408218621535.859237343736254.359075651
621208.859537482736002.454286948620762.108382106735799.301721424
#Sta/Elev= 30
8715.758241.33988793.838239.89468834.697236.91298915.854224.47169008.885222.7189
9101.425224.34889121.989218.54789132.271217.74949214.971216.36499277.216218.8945
9519.761217.03639534.782218.4291 9695.74213.19929721.418210.08579911.289210.6178
9918.929210.30469963.512197.635510003.71195.094810025.39196.412210030.56198.7218
 10043.8213.486410056.84220.365510158.22220.854710460.34229.465510581.11227.3807
10602.75230.932910731.75230.685510742.36231.850910752.89239.228510777.01239.3547
#Mann= 3 , 0 , 0
8715.758  0.0658       08715.758  0.0658       010777.01  0.0658       0
#XS Ineff= 2 , 0
       09850.439         10074.5       0
Bank Sta=8715.758,10777.01
Exp/Cntr=0.3,0.1

Type RM Length L Ch R = 1 ,12255.45,121.229200,121.229200,121.229200
XS GIS Cut Line= 6
622730.314243436736407.254364103622341.721515179736283.991079316
622081.304848522736188.504968226621757.954154074736019.234134898
621547.450681835735925.918162674621214.437102491735786.635008469
#Sta/Elev= 30
8829.549240.20128950.526236.6753 8992.49230.28999044.945225.61479065.927222.2962
9149.856219.57989265.685220.38149286.987215.68229350.893215.29929393.497213.5939
9544.285215.42619724.883213.06359747.457207.48829758.745206.92579849.044208.8181
9882.803208.23769893.741207.73119915.618202.07299937.495  200.169948.434195.5899
9959.372193.89719981.249192.379910014.06192.350810062.75193.502710068.76195.1917
 10079.7201.989410090.63204.317210253.11209.535510285.56215.488210472.16224.5277
#Mann= 3 , 0 , 0
8829.549  0.0727       08829.549  0.0727       010472.16  0.0727       0
#XS Ineff= 2 , 0
       09875.141        10130.63       0
Bank Sta=8829.549,10472.16
Exp/Cntr=0.3,0.1

Type RM Length L Ch R = 3 ,12189.28,,,
BEGIN DESCRIPTION:
END DESCRIPTION:
Bridge Culvert--1,0,-1,-1, 0
Deck Dist Width WeirC Skew NumUp NumDn MinLoCord MaxHiCord MaxSubmerge Is_Ogee
35.614600,50.000000,2.6,0, 35, 35, , , 0.95, 0, 0,0,,
 9690.00 9702.51 9724.38 9733.00 9746.26 9757.20 9768.13 9800.95 9844.91 9853.33
 9868.13 9899.52 9899.52 9949.39 9951.79 9954.25 9960.79 9983.30 9995.1110005.81
10038.6910039.5810050.8310104.0510118.3610133.5210133.5210151.9110196.5110229.96
10241.1110284.0110306.1910327.9410360.04
  212.92  212.88  213.02  213.25  214.72  215.32  216.40  217.63  218.56  218.47
  218.51  218.86  218.86  219.42  219.42  219.26  219.39  219.48  219.63  219.59
  219.88  219.67  219.84  220.10  219.97  220.05  220.05  220.07  220.42  220.34
  220.24  220.50  221.02  221.72  222.55
 -787.08 -787.12 -786.98 -786.75 -785.28 -784.68 -783.60 -782.37 -781.44 -781.53
 -781.49 -781.14  214.86  215.42  215.42  215.26  215.39  215.48  215.63  215.59
  215.88  215.67  215.84  216.10  215.97  216.05 -779.95 -779.93 -779.58 -779.66
 -779.76 -779.50 -778.98 -778.28 -777.45
 9690.00 9702.51 9724.38 9733.00 9746.26 9757.20 9768.13 9800.95 9844.91 9853.33
 9868.13 9900.53 9900.53 9949.39 9951.79 9954.25 9960.79 9983.30 9995.1110005.81
10038.6910039.5810050.8310104.0510118.3610134.5310134.5310151.9110196.5110229.96
10241.1110284.0110306.1910327.9410360.04
  212.92  212.88  213.02  213.25  214.72  215.32  216.40  217.63  218.56  218.47
  218.51  218.87  218.87  219.42  219.42  219.26  219.39  219.48  219.63  219.59
  219.88  219.67  219.84  220.10  219.97  220.05  220.05  220.07  220.42  220.34
  220.24  220.50  221.02  221.72  222.55
 -787.08 -787.12 -786.98 -786.75 -785.28 -784.68 -783.60 -782.37 -781.44 -781.53
 -781.49 -781.13  214.87  215.42  215.42  215.26  215.39  215.48  215.63  215.59
  215.88  215.67  215.84  216.10  215.97  216.05 -779.95 -779.93 -779.58 -779.66
 -779.76 -779.50 -778.98 -778.28 -777.45
Pier Skew, UpSta & Num, DnSta & Num=  ,9976.85, 2 ,9977.87, 2 , 0 , 0 , 0 ,,
    4.00    4.00
 -780.53  219.47
    4.00    4.00
 -780.53  219.47
Pier Skew, UpSta & Num, DnSta & Num=  ,10056.19, 2 ,10057.20, 2 , 0 , 0 , 0 ,,
    4.00    4.00
 -780.13  219.87
    4.00    4.00
 -780.13  219.87
BR Coef=-1 , 0 , 0 ,, 0 ,,,0.8,0,1,0,
WSPro=,,,, 1 ,,,, 0 ,,,, 0 ,,,,-1 ,-1 ,-1 , 0 , 0 , 0 , 0 , 0
BC Design=,, 0 ,, 0 ,,,,,,

Type RM Length L Ch R = 1 ,12134.23,114.334200,114.334200,114.334200
XS GIS Cut Line= 6
622766.814118236736267.628858879622328.700681835736155.952884883
622006.988973409736030.259350985621629.316515654735824.839770555
621217.407461166735570.205082327620860.062982738 735453.58667472
#Sta/Elev= 30
8863.513237.80558989.222235.08219009.862230.5202 9092.42220.92329198.038218.1374
9351.817210.24729416.234208.74669437.706213.0777 9455.65   213.49588.012213.8747
9686.594211.50389830.972214.35379874.268207.16149926.837203.65839938.112201.1715
9960.663190.84759983.213190.475210039.59191.213110062.14202.281910128.83204.9118
10242.93215.417710261.95215.205410299.99208.937410448.87207.092410472.38 209.723
10554.67206.920710598.93207.699410651.52214.824110882.94212.363210951.25214.6567
#Mann= 3 , 0 , 0
8863.513  0.0818       08863.513  0.0818       010951.25  0.0818       0
#XS Ineff= 2 , 0
       09863.682        10131.54       0
Bank Sta=8863.513,10951.25
Exp/Cntr=0.3,0.1

Type RM Length L Ch R = 1 ,12019.89,241.186900,241.186900,241.186900
XS GIS Cut Line= 6
622787.771962997736237.919780923622284.107012063736059.360286638
622059.272456795735943.560929075621274.604622334735472.336316094
621026.323007494735363.427104622620746.324347526735274.084647313
#Sta/Elev= 30
8879.977236.33428997.719233.7985 9049.95227.48519081.458226.41279092.053222.6907
9113.244220.46759229.863218.65619251.419213.8733  9469.3208.97559480.386211.9434
9560.618 212.2379592.616 207.6349930.394202.42799941.994200.19069953.407 191.766
 9964.82188.83329999.024187.3958 10044.7189.750710068.51199.836510080.41201.9313
10175.66201.670810247.09205.502910282.81202.967210341.61208.207910649.47204.4388
   10796205.576610834.67208.289911035.72210.094811087.82216.057611148.78216.3868
#Mann= 3 , 0 , 0
8879.977  0.0629       08879.977  0.0629       011148.78  0.0629       0
#XS Ineff= 2 , 0
       09866.554        10165.44       0
Bank Sta=8879.977,11148.78
Exp/Cntr=0.3,0.1

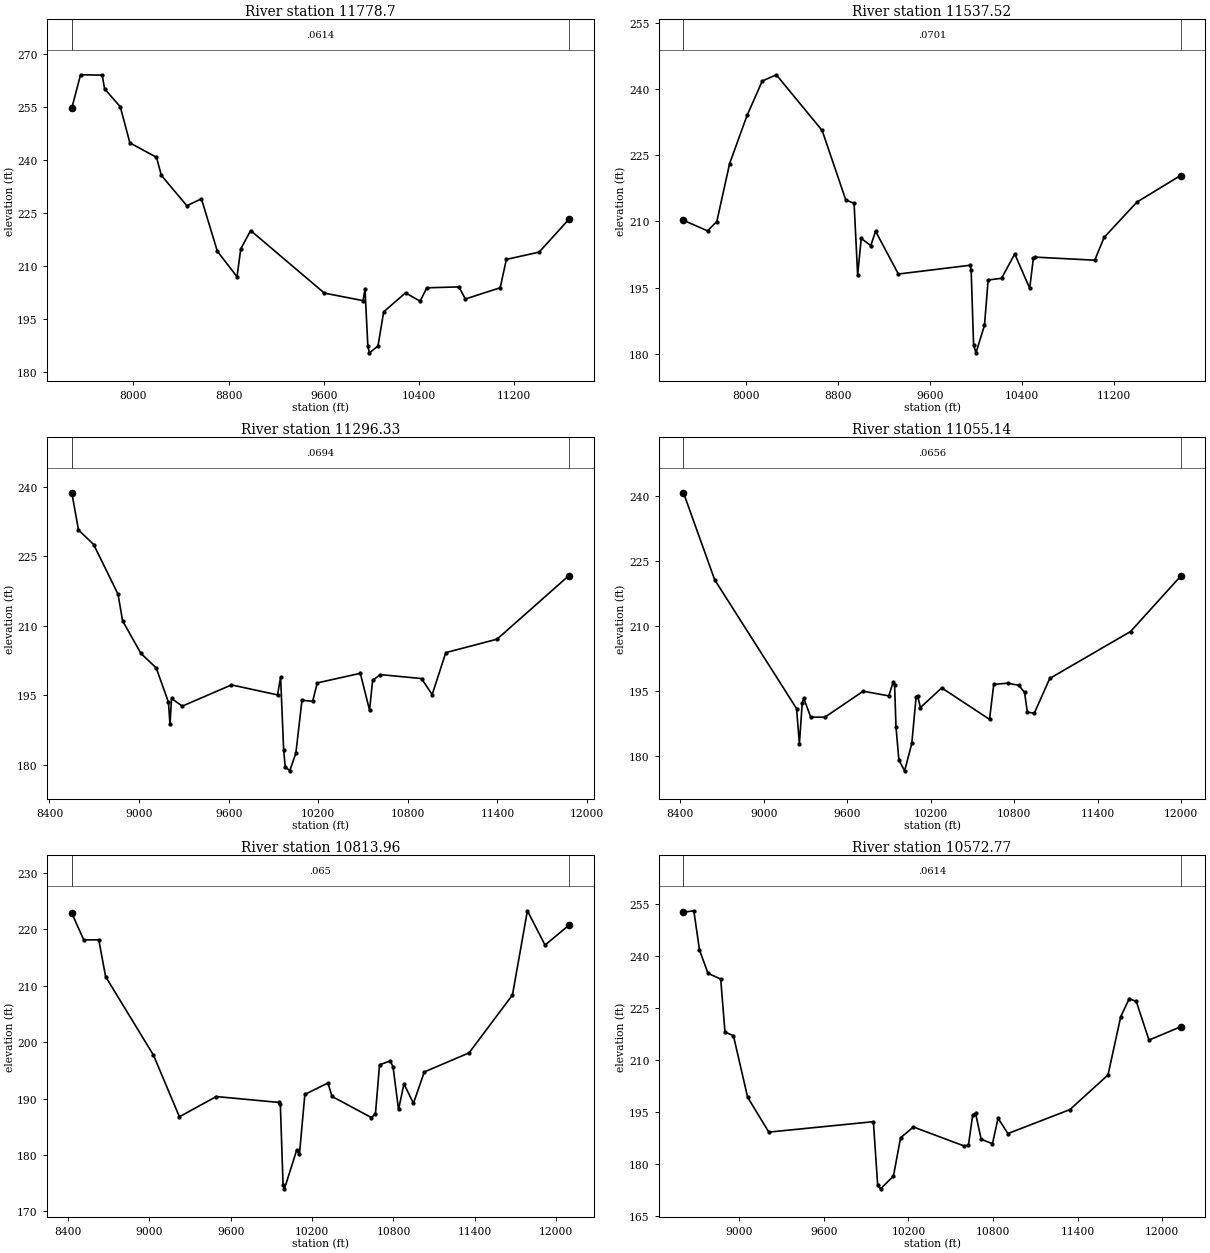
Type RM Length L Ch R = 1 , 11778.7,241.186800,241.186800,241.186800
XS GIS Cut Line= 6
624307.451908619736271.691927095622816.691224103735978.871572217
622287.003670847735783.424411774621340.802737294 735279.10109902
620868.812511597735127.930370521620357.477061607735040.428462062
#Sta/Elev= 30
 7483.83254.71457557.015264.10787738.836264.01757759.038260.12927890.585255.0647
7971.589244.82528194.932240.75378235.615235.64788449.655227.04258572.433228.9928
8706.162214.14198871.335206.94488902.472214.78978985.504220.0233 9604.97202.3088
9929.894200.17489946.192203.40149970.325187.1959 9983.88185.401210055.35187.3373
10102.98196.999910286.73202.374510409.56200.017410464.96203.807310735.57204.0662
10788.88200.639711081.77203.828211133.43211.844611409.09213.910911658.96223.2191
#Mann= 3 , 0 , 0
 7483.83  0.0614       0 7483.83  0.0614       011658.96  0.0614       0
#XS Ineff= 2 , 0
       09900.321        10313.75       0
Bank Sta=7483.83,11658.96
Exp/Cntr=0.3,0.1

Type RM Length L Ch R = 1 ,11537.52,241.186900,241.186900,241.186900
XS GIS Cut Line= 6
624471.966165357 735925.60290308623168.000670684735705.510760627
622617.205983733735556.799786342621193.028382896735082.306510855
620805.948679503 734994.19833828620288.468973766734934.156006786
#Sta/Elev= 30
7461.667210.26057670.361207.88297751.032209.99187862.182223.12318013.894234.0332
8145.574241.80638267.307243.20878664.786 230.6098870.127214.8729 8942.19214.1067
8973.074197.8575  9004.1206.15169087.066204.54849128.549207.79329326.284198.1067
9947.412200.08869957.931199.06829978.968182.043410000.01180.267810073.69186.5318
10105.26196.758210221.84197.1407 10336.1202.659710465.99194.866510497.83201.7276
10514.94201.931411030.06201.2381   11112206.401111396.51214.392411775.03220.4029
#Mann= 3 , 0 , 0
7461.667  0.0701       07461.667  0.0701       011775.03  0.0701       0
#XS Ineff= 2 , 0
       09907.775        10293.65       0
Bank Sta=7461.667,11775.03
Exp/Cntr=0.3,0.1

Type RM Length L Ch R = 1 ,11296.33,241.186800,241.186800,241.186800
XS GIS Cut Line= 6
 623478.82857437735438.362641175622869.024188001735313.752528021
622242.490270259735160.246860725621145.529896159734911.809317188
620713.499256858734847.994997836620214.525945822734820.283743753
#Sta/Elev= 30
8549.795238.77018594.351230.73218696.011227.58728859.169 216.8398889.773211.0931
9012.538204.04349114.944200.90739196.959193.49179207.238188.67659217.516194.3042
9289.463192.64269618.988 197.2329927.562195.0743 9947.99 198.8939968.419183.2148
9978.633179.585310009.29178.6564 10050.2182.468710091.12193.909510162.72193.6955
10193.57197.664110481.89199.742610543.64191.781110564.17198.193110615.52199.4652
10891.71198.605810963.04195.146911054.33204.214111397.61207.119511878.98220.8672
#Mann= 3 , 0 , 0
8549.795  0.0694       08549.795  0.0694       011878.98  0.0694       0
#XS Ineff= 2 , 0
       09881.987        10237.79       0
Bank Sta=8549.795,11878.98
Exp/Cntr=0.3,0.1

Type RM Length L Ch R = 1 ,11055.14,241.186900,241.186900,241.186900
XS GIS Cut Line= 6
623666.727843541735176.286979596622912.671918353735052.073509458
621849.576195279734825.506670733621593.876985659734786.601928997
 620751.65331854734701.158767158620135.951791485734699.279546072
#Sta/Elev= 30
8422.061240.70748646.348220.68189234.856191.03129255.217182.92239275.578  192.28
9285.758193.4741 9336.66189.05519438.464189.0444 9713.74195.02539898.208193.9509
9929.176197.17049939.499196.38189949.822186.69649970.467179.166910011.76176.6957
10063.34 183.03610094.29 193.73810104.61 194.01710125.24191.266810278.25195.7942
10621.88188.546410652.13196.575510752.88196.884810833.42196.360510873.68 194.735
10893.82190.181510944.15189.988311054.67197.964511635.82208.772611994.98221.4809
#Mann= 3 , 0 , 0
8422.061  0.0656       08422.061  0.0656       011994.98  0.0656       0
#XS Ineff= 2 , 0
       09862.685        10245.93       0
Bank Sta=8422.061,11994.98
Exp/Cntr=0.3,0.1

Type RM Length L Ch R = 1 ,10813.96,241.186900,241.186900,241.186900
XS GIS Cut Line= 6
623732.438757727 734833.14790317622655.519120994734701.691807399
 621923.29771266  734630.8030463620794.043316566734585.440428176
620504.671047359 734587.30910729620079.458812937734612.280359107
#Sta/Elev= 30
8428.203222.87468516.227218.13388626.964218.16588677.299211.62589030.079197.7088
9221.607186.75749493.512190.3463 9956.04 189.3029966.094188.93929986.202 174.612
9996.257173.969710086.72180.854210106.78180.066710146.88190.726910317.21 192.753
10347.23190.371810637.51186.620410667.54187.279110697.57195.977410777.65196.6748
10797.67195.556510837.71188.057310877.75192.594410947.81189.150511027.89194.7121
11358.07198.100811678.11208.378311788.19223.3145 11918.4 217.22712094.44220.7539
#Mann= 3 , 0 , 0
8428.203   0.065       08428.203   0.065       012094.44   0.065       0
#XS Ineff= 2 , 0
       09907.234        10286.42       0
Bank Sta=8428.203,12094.44
Exp/Cntr=0.3,0.1

Type RM Length L Ch R = 1 ,10572.77,241.186800,241.186800,241.186800
XS GIS Cut Line= 6
623548.192377894734446.920456849622530.992368095734373.950627897
622305.707572658734388.341418992 621720.50558352734468.307122016
620644.027779048734487.502262003620032.288998433734539.638844771
#Sta/Elev= 30
 8602.99252.73328676.491253.14218716.659241.83788776.911235.11938867.289233.4287
8897.416218.17188957.668217.09789058.088199.37289208.615189.29939950.804192.3058
9981.259173.985710001.57172.934710093.03176.583610143.73187.645710234.65190.7814
10595.71185.284610625.72185.575710655.72194.261110675.73 194.79410715.73187.2342
10795.73 185.94310835.73193.292110905.73188.878211345.77 195.79811616.01 205.783
 11706.2222.569311766.38227.780111816.52227.012211906.91215.844512130.95219.6667
#Mann= 3 , 0 , 0
 8602.99  0.0614       0 8602.99  0.0614       012130.95  0.0614       0
#XS Ineff= 2 , 0
       09889.883        10266.21       0
Bank Sta=8602.99,12130.95
Exp/Cntr=0.3,0.1