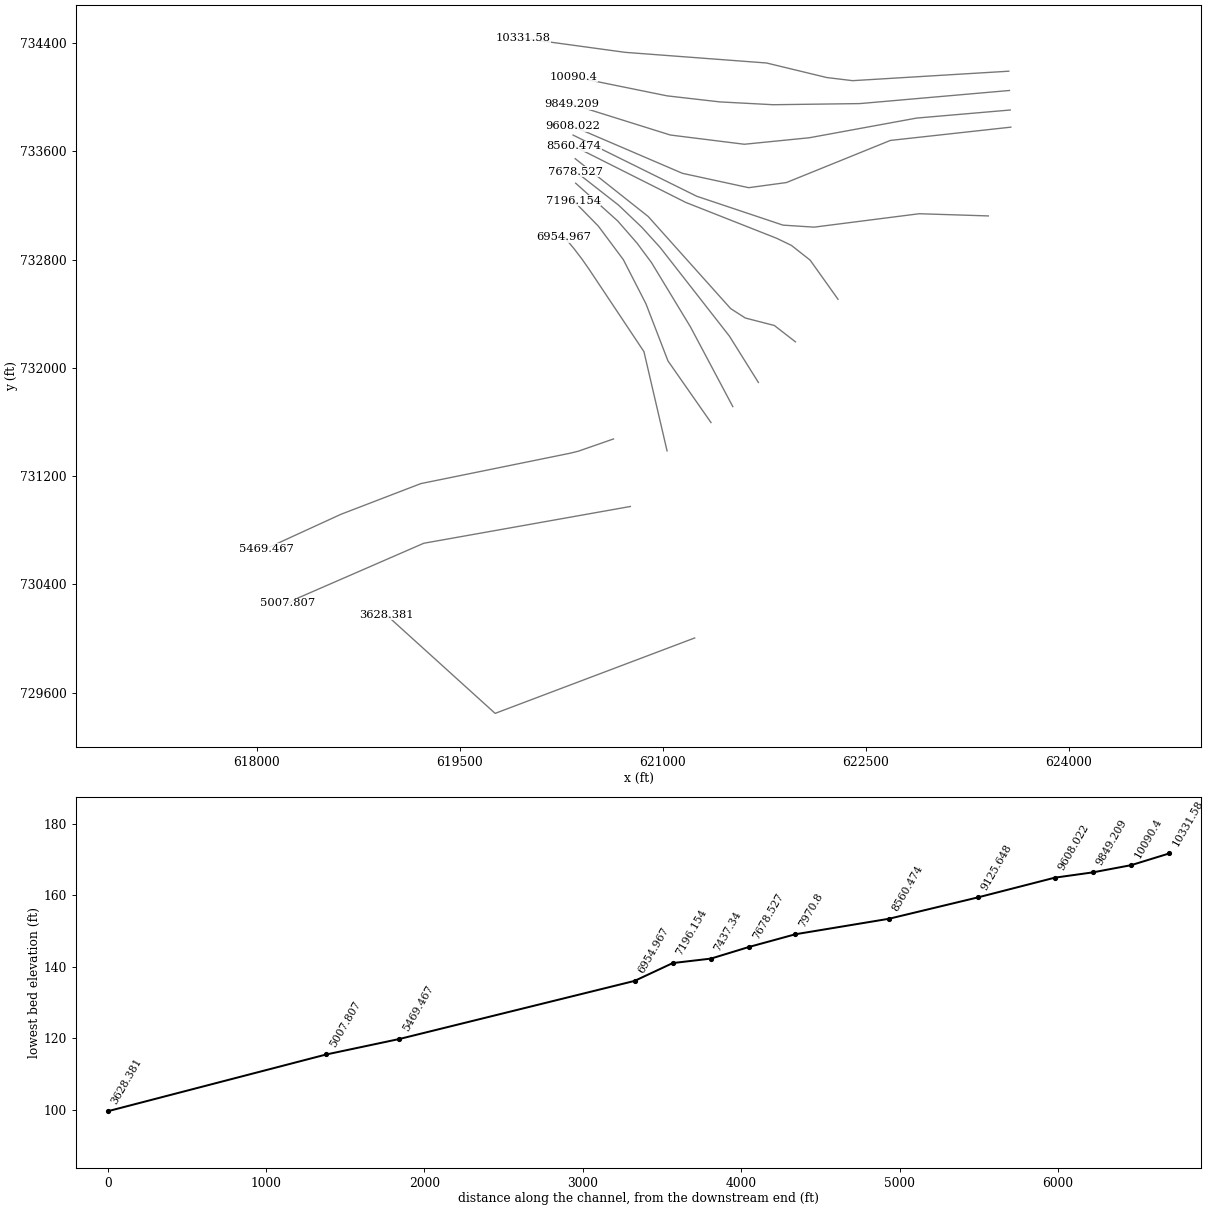
HEC-RAS study 3211_ras.prj: 3211

--- 3211_ras.g01 (geometry) --- (continued)

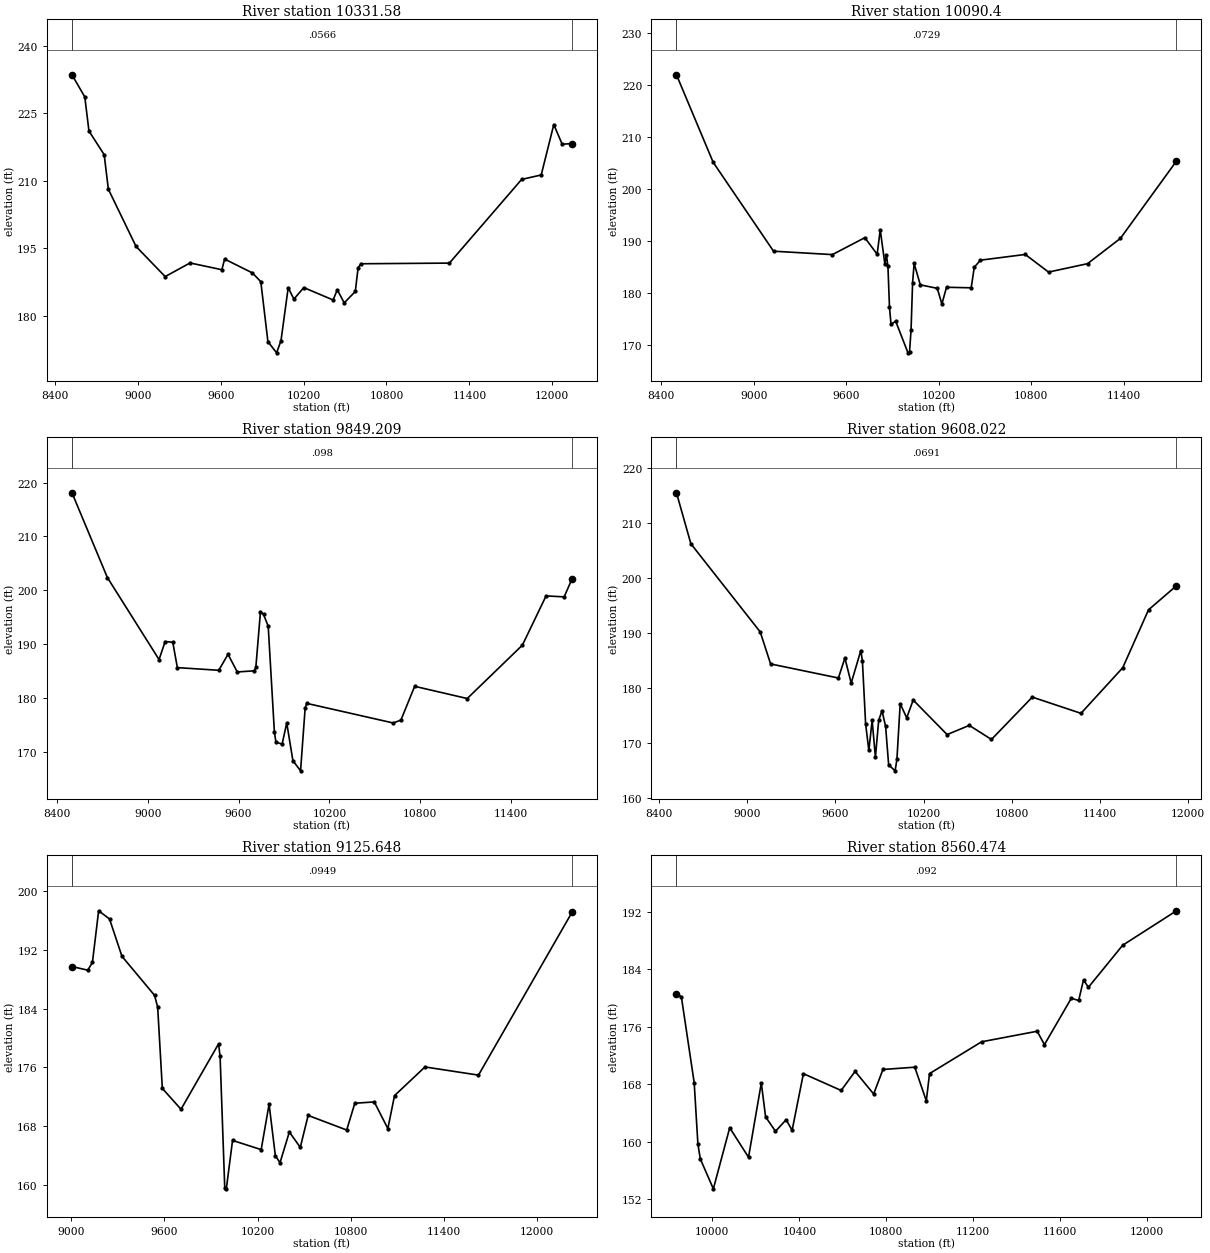
Type RM Length L Ch R = 1 ,10331.58,241.186900,241.186900,241.186900
XS GIS Cut Line= 6
623557.548645901 734193.36559388622403.518750086734123.404577289
622212.509178915734146.398988904621767.180984915734253.988384752
620722.165506116734332.709547081619965.149077401734436.243366381
#Sta/Elev= 30
8522.567233.59358615.331228.67088645.435221.09578755.815215.81648785.918208.1498
8986.609195.41469197.327188.72129377.764191.74919607.883 190.247 9627.89  192.61
9828.909189.53799889.933187.58739941.376174.255210004.47171.761810036.12174.4673
10088.27186.2501 10129.7183.709910201.23186.272810413.61183.514210443.81185.7767
10494.02182.872310574.28185.404410594.33190.649610614.38191.569811255.76191.7168
   11779210.327511920.51211.315112011.58222.515112072.41218.153912143.26218.2932
#Mann= 3 , 0 , 0
8522.567  0.0566       08522.567  0.0566       012143.26  0.0566       0
#XS Ineff= 2 , 0
       09836.977        10218.88       0
Bank Sta=8522.567,12143.26
Exp/Cntr=0.3,0.1

Type RM Length L Ch R = 1 , 10090.4,241.186900,241.186900,241.186900
XS GIS Cut Line= 6
623562.806470963734050.878534707622457.568255897733954.013980164
621816.532367074733945.614786869 621422.16111866733966.438533622
621032.368044837 734011.07510768620340.300870143734151.809157652
#Sta/Elev= 30
8497.934221.9416 8736.34205.0975 9127.89188.01659509.741187.36039720.233190.6155
9800.271187.42639820.279192.1319 9850.29185.56259860.294187.34019870.297185.0829
9880.301177.21429890.305173.94089920.307174.556710000.31  168.4710010.31 168.558
10020.31172.871710030.31 181.99210040.31185.653210080.31181.550210190.33180.8729
10220.34177.861110250.35181.079510410.48 180.976 10430.5184.936110470.57186.2883
10761.48187.390510912.43184.000711165.36185.611811378.96 190.48211742.62205.3468
#Mann= 3 , 0 , 0
8497.934  0.0729       08497.934  0.0729       011742.62  0.0729       0
#XS Ineff= 2 , 0
       09795.886        10209.61       0
Bank Sta=8497.934,11742.62
Exp/Cntr=0.3,0.1

Type RM Length L Ch R = 1 ,9849.209,241.186800,241.186800,241.186800
XS GIS Cut Line= 6
623568.131894114733906.559567309622876.341562915733846.876655829
622083.041532897733701.458069295 621602.87997303733653.440541815
621056.186103071733721.646332128620326.305602202733950.277299161
#Sta/Elev= 30
8499.731 218.111 8733.33202.37079074.727 187.1269115.031190.47679165.411190.3337
9195.642185.62979469.106185.13449530.121188.10259591.342184.82489703.629 185.032
9713.837185.6575 9744.46196.03619764.876195.5071  9795.5193.32599836.332173.6777
 9846.54 171.7789887.372171.42139917.899175.35729958.462168.359610009.12166.4541
10039.44178.110210049.54178.991310621.96175.3391 10672.1175.895710762.61182.1597
11109.77179.887511473.98189.803311630.33198.949411749.97198.774511801.42202.1022
#Mann= 3 , 0 , 0
8499.731   0.098       08499.731   0.098       011801.42   0.098       0
#XS Ineff= 2 , 0
       09744.772        10255.16       0
Bank Sta=8499.731,11801.42
Exp/Cntr=0.3,0.1

Type RM Length L Ch R = 1 ,9608.022,482.373700,482.373700,482.373700
XS GIS Cut Line= 6
623572.807497516733779.850715129622682.370621097733681.769037116
621913.981881691733370.371736898621635.085608245733332.462320516
621145.598734215733438.638344695620331.595184757733788.020073627
#Sta/Elev= 30
8519.691215.57648617.589206.2971 9089.29190.24649159.867184.41959620.953181.8596
9664.978185.48929707.817 180.9369773.181 186.8379784.106184.98789805.957173.5029
9828.021168.67619850.299174.15349872.577167.44099894.867174.15659917.448175.8951
9941.771173.05569962.611166.0565 10006.6164.961610018.81167.050110041.03177.1777
10085.46 174.60810129.54177.848210360.24 171.56210511.02173.235710661.66170.6733
10939.48178.382511270.56175.430111554.56183.732511729.84194.2709 11919.8198.6564
#Mann= 3 , 0 , 0
8519.691  0.0691       08519.691  0.0691       0 11919.8  0.0691       0
#XS Ineff= 2 , 0
       09725.611         10182.7       0
Bank Sta=8519.691,11919.8
Exp/Cntr=0.3,0.1

Type RM Length L Ch R = 1 ,9125.648,565.174800,565.174800,565.174800
XS GIS Cut Line= 6
623406.375408008733123.738472722622895.872029344733140.000201061
622118.907141612733040.841939445621888.846633496733055.664621277
621251.776555307733268.951835214620337.562403045733721.054623964
#Sta/Elev= 30
9004.945189.74889106.584189.24749136.623190.30629176.672197.33889246.758196.2213
9326.786191.14019536.828185.8235 9556.85184.20919586.883173.14749707.191170.3059
9948.878179.21029958.901177.50369988.973159.54049998.996159.472310039.11 166.067
10223.45164.813510274.46170.9966 10314.8163.981710344.85163.028810404.87167.2108
10475.39165.122110525.97169.470110774.23167.481610826.65171.130710951.92171.3059
11039.32167.679211082.39172.168611278.37176.071811623.04174.957612225.18197.1203
#Mann= 3 , 0 , 0
9004.945  0.0949       09004.945  0.0949       012225.18  0.0949       0
#XS Ineff= 2 , 0
       09923.845        10382.19       0
Bank Sta=9004.945,12225.18
Exp/Cntr=0.3,0.1

Type RM Length L Ch R = 1 ,8560.474,589.674200,589.674200,589.674200
XS GIS Cut Line= 6
622295.265668385732507.907171868622089.428753739732797.002496489
621951.146273427 732905.76455371621843.061811193732958.018267827
621169.607080375  733223.7778359620344.904291771733638.662317179
#Sta/Elev= 30
9834.956180.59149857.364 180.2179916.434168.2347 9933.59159.65499944.762157.5997
10004.55153.447710079.86161.953910166.33157.844810225.16  168.1910244.86163.4701
10290.38161.458610339.09 163.06810366.92161.602310418.71169.488210592.41167.1472
10656.45169.804410741.83166.653210784.52170.070410931.07170.3888   10984165.7009
10998.81169.496311238.29173.925211493.83 175.39411527.28173.526811650.78179.9833
11684.52179.677711707.02182.541311729.51 181.51611886.97187.367112134.44192.1707
#Mann= 3 , 0 , 0
9834.956   0.092       09834.956   0.092       012134.44   0.092       0
#XS Ineff= 2 , 0
       0                10347.19       0
Bank Sta=9834.956,12134.44
Exp/Cntr=0.3,0.1

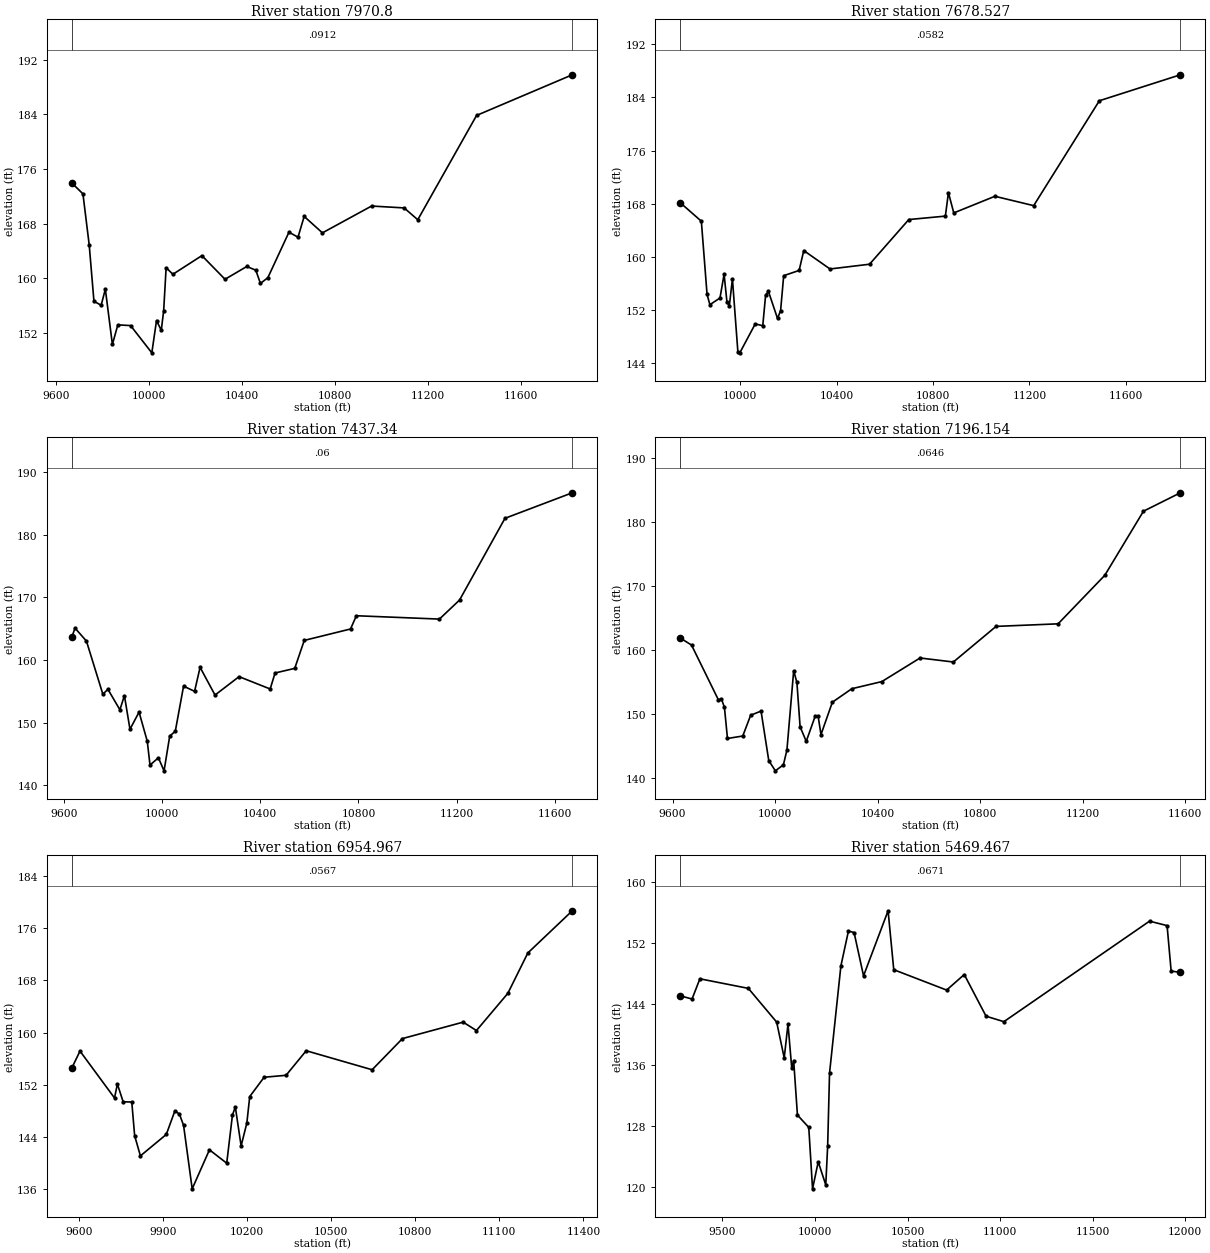
Type RM Length L Ch R = 1 ,  7970.8,292.272200,292.272200,292.272200
XS GIS Cut Line= 6
621980.651127839732193.292631322621825.031280365732313.888896161
621610.178650284732369.268571594621501.504404012732439.171513093
620892.778984193733119.268072308620353.079448398733546.918892849
#Sta/Elev= 30
9667.509173.94919714.604172.38359741.615164.90789762.001156.66999793.044156.0796
9811.048158.43699841.421150.34939864.867153.21659919.762 153.10710011.16149.1189
10031.37153.845110051.88152.410810062.19155.306810072.74161.575610101.89160.6158
10226.72163.345210326.25159.883710419.93 161.75510458.85161.2085 10478.7159.2704
10510.74160.119310601.55166.771910640.47 166.04210667.07169.081310745.56166.6754
10957.24170.600811097.33170.326211156.04168.595811409.25183.860411821.31 189.808
#Mann= 3 , 0 , 0
9667.509  0.0912       09667.509  0.0912       011821.31  0.0912       0
#XS Ineff= 2 , 0
       0                10178.44       0
Bank Sta=9667.509,11821.31
Exp/Cntr=0.3,0.1

Type RM Length L Ch R = 1 ,7678.527,241.186900,241.186900,241.186900
XS GIS Cut Line= 6
621706.821290487731892.985046827621493.231045714732234.615139617
620981.048994659732890.246503188620845.331066604733039.836328745
620673.905686942733203.168225376  620358.7377548733449.551787451
#Sta/Elev= 30
 9751.34168.17269839.508165.37159863.162 154.364 9874.94152.80839916.784153.8229
9933.832157.3878 9945.61153.2271  9955.5 152.6319968.395156.68649990.881145.7673
    9999145.569610062.92149.916410094.18 149.65110106.05154.263210117.64154.8151
10155.37150.737810168.17151.935410180.97157.177610244.97157.964110264.19160.9557
10372.96158.185110536.97   158.910699.79165.619810851.42166.136910864.11169.6701
10886.24166.615711056.82169.1208 11217.6167.712511489.88183.492211826.03 187.399
#Mann= 3 , 0 , 0
 9751.34  0.0582       0 9751.34  0.0582       011826.03  0.0582       0
#XS Ineff= 2 , 0
       0                10273.93       0
Bank Sta=9751.34,11826.03
Exp/Cntr=0.3,0.1

Type RM Length L Ch R = 1 , 7437.34,241.186800,241.186800,241.186800
XS GIS Cut Line= 6
621517.758747033731714.491068141621204.754770191732303.728777353
 620916.82628466732778.859897288620809.692599385732923.087947841
620667.122695699733086.616710818620356.583248143733365.526028264
#Sta/Elev= 30
 9633.44163.71249645.676165.09529692.249163.01729759.081154.53629779.736 155.315
9828.526152.05069846.952154.30719869.591148.9341 9906.55151.67829939.989147.0302
9951.136143.21819985.353144.382410008.37142.2969 10031.4147.8397 10054.2148.6227
10087.84155.8218 10132.7154.993210155.12158.828210215.95154.3976 10313.9157.3386
10440.53  155.3710460.55157.921110540.62158.6594 10579.4163.125710767.81164.9478
10791.67167.063511129.89166.530111211.88169.5696 11396.9182.623411671.11186.6994
#Mann= 3 , 0 , 0
 9633.44    0.06       0 9633.44    0.06       011671.11    0.06       0
#XS Ineff= 2 , 0
       0                10165.46       0
Bank Sta=9633.44,11671.11
Exp/Cntr=0.3,0.1

Type RM Length L Ch R = 1 ,7196.154,241.186900,241.186900,241.186900
XS GIS Cut Line= 6
621356.614325525731596.580515818 621038.67752106732052.180730798
620875.925081786 732474.42782185620708.709081223732800.654172086
620524.445348972733048.010389028620339.015231644733237.243501711
#Sta/Elev= 30
 9629.39 161.8419673.969160.72479778.661152.16679790.505152.30369802.348  150.98
9814.192146.11049873.812146.4949 9904.66149.74749945.137150.39559975.241 142.652
   10001 141.04810032.39141.994510046.09144.314810072.41156.706810084.98154.8742
10097.51147.925910121.45145.665410156.07149.580110167.51 149.65710178.94146.7221
10223.28151.7834 10299.1153.8934 10416.3155.009310565.36158.702110695.19158.0716
10861.66 163.64311103.69164.044911285.79171.632911436.59181.662211580.67184.5453
#Mann= 3 , 0 , 0
 9629.39  0.0646       0 9629.39  0.0646       011580.67  0.0646       0
#XS Ineff= 2 , 0
       0                10231.42       0
Bank Sta=9629.39,11580.67
Exp/Cntr=0.3,0.1

Type RM Length L Ch R = 1 ,6954.967,1485.499400,1485.499400,1485.499400
XS GIS Cut Line= 6
621031.983094275731387.185976505620861.077990353732120.653713778
620458.396409303732725.340679869620404.757416219732802.502695069
620343.120142579732883.326172158  620272.0085572732967.908015966
#Sta/Elev= 30
9574.685154.62949603.244157.17219726.459149.98099736.727152.12029757.263149.3981
9788.066149.36079798.334144.1944 9818.87141.10329911.281144.39149942.085148.0197
9957.988147.51099972.888145.797310003.69136.0503 10065.3142.033210126.91139.9808
10147.44 147.37610157.71148.599410178.32  142.6310198.78146.146910209.05 150.195
10260.39153.159510338.73153.458510410.62157.224710645.93154.309610754.25159.0908
10970.84161.608911018.31160.322111130.35166.026611201.74172.216511360.44178.6837
#Mann= 3 , 0 , 0
9574.685  0.0567       09574.685  0.0567       011360.44  0.0567       0
#XS Ineff= 2 , 0
       0                10247.46       0
Bank Sta=9574.685,11360.44
Exp/Cntr=0.3,0.1

Type RM Length L Ch R = 1 ,5469.467,461.660500,461.660500,461.660500
XS GIS Cut Line= 6
620636.074344022731475.401318719 620375.44673413731384.766947985
620314.569901854731369.795953572619212.420929968731145.498969793
618621.616867483730918.595960334618069.583730673730665.488083795
#Sta/Elev= 30
9270.831145.05849335.493 144.6339377.843147.28059639.635146.0275 9792.71 141.611
 9833.53136.9225 9853.94141.35139874.349135.54079884.554136.57739904.964129.4381
9966.194127.82529986.604 119.77610017.22123.308810058.04120.299310068.24125.3698
10078.45134.936610139.68148.9549 10180.5153.533910211.11153.334210262.14147.6657
 10394.8156.188210425.42148.472810711.16145.805310806.42147.838510924.26142.3809
11020.66141.667411807.59154.827611902.41154.246811924.41148.282511974.37148.1333
#Mann= 3 , 0 , 0
9270.831  0.0671       09270.831  0.0671       011974.37  0.0671       0
#XS Ineff= 2 , 0
       09723.668        10199.56       0
Bank Sta=9270.831,11974.37
Exp/Cntr=0.3,0.1

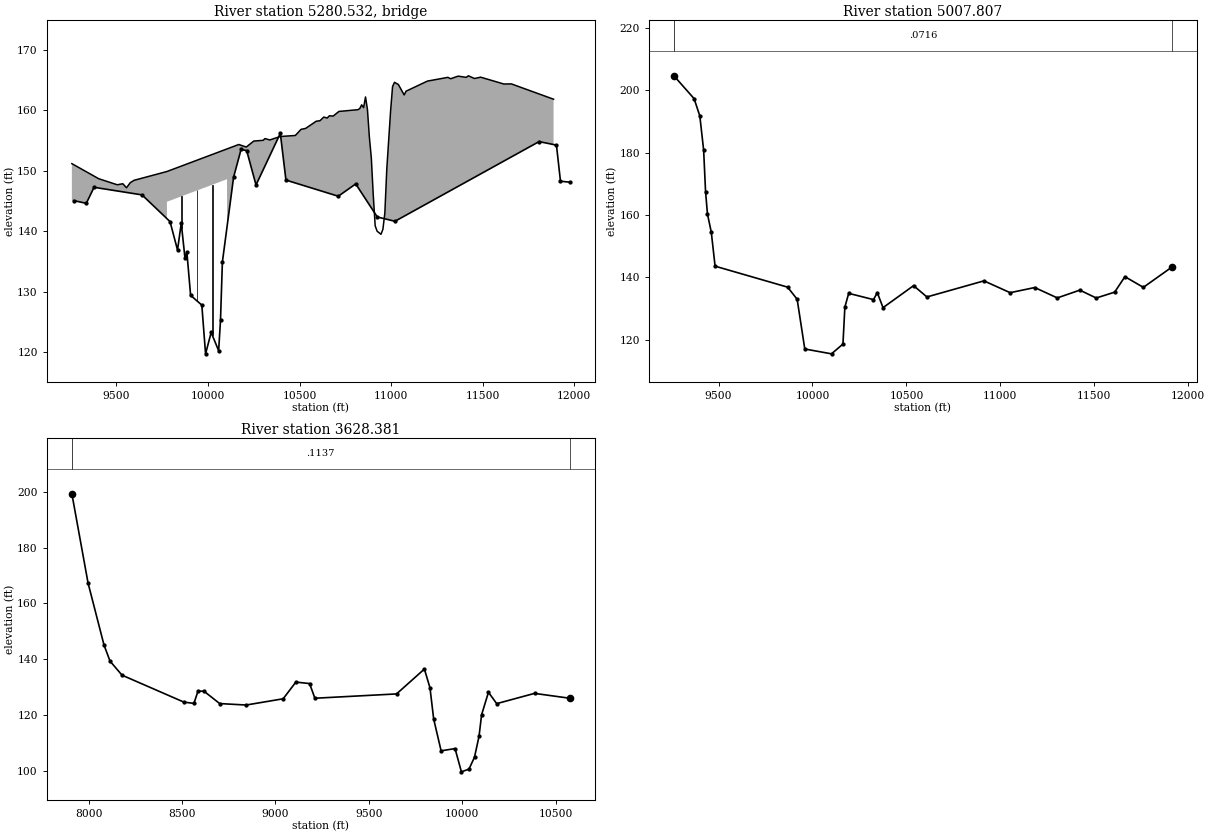
Type RM Length L Ch R = 3 ,5280.532,,,
BEGIN DESCRIPTION:
END DESCRIPTION:
Bridge Culvert--1,0,-1,-1, 0
Deck Dist Width WeirC Skew NumUp NumDn MinLoCord MaxHiCord MaxSubmerge Is_Ogee
158.830250,144.000000,2.6,0, 60, 60, , , 0.95, 0, 0,0,,
 9256.66 9403.10 9504.28 9534.74 9555.05 9575.35 9595.66 9775.72 9775.7210103.72
10103.7210167.9010208.8710249.8410301.0510311.2910337.3610394.0210476.7610507.79
10533.0710590.5410611.3610631.9110650.5010662.9410683.6310714.6610818.0910828.43
10838.8810849.4310859.9810870.5310881.0810891.6310902.1710912.7210923.2710944.37
10954.9210965.4710976.0210997.1211007.6611018.2111039.3111070.9611081.5111197.80
11309.6011324.5611365.5011410.2211421.4011454.9411488.4811615.2411656.1911886.64
  151.19  148.70  147.70  147.87  147.21  148.04  148.43  149.89  149.89  153.62
  153.62  154.35  153.93  154.92  155.04  155.33  155.10  155.67  155.84  156.85
  157.01  158.19  158.28  158.88  158.72  159.09  159.05  159.81  160.10  160.28
  160.90  160.44  162.20  160.13  155.53  152.15  146.02  140.92  140.03  139.52
  140.34  143.04  150.26  160.01  163.93  164.62  164.26  162.54  163.16  164.82
  165.44  165.21  165.64  165.44  165.70  165.25  165.47  164.34  164.36  161.83
 -848.81 -851.30 -852.30 -852.13 -852.79 -851.96 -851.57 -850.11  144.89  148.62
 -846.38 -845.65 -846.07 -845.08 -844.96 -844.67 -844.90 -844.33 -844.16 -843.15
 -842.99 -841.81 -841.72 -841.12 -841.28 -840.91 -840.95 -840.19 -839.90 -839.72
 -839.10 -839.56 -837.80 -839.87 -844.47 -847.85 -853.98 -859.08 -859.97 -860.48
 -859.66 -856.96 -849.74 -839.99 -836.07 -835.38 -835.74 -837.46 -836.84 -835.18
 -834.56 -834.79 -834.36 -834.56 -834.30 -834.75 -834.53 -835.66 -835.64 -838.17
 9256.66 9403.10 9504.28 9534.74 9555.05 9575.35 9595.66 9687.03 9717.48 9761.17
 9831.12 9831.1210159.1210159.1210203.0310249.8410301.0510311.2910337.3610445.73
10476.7610507.7910611.3610631.9110650.5010662.9410683.6310714.6610818.0910828.43
10838.8810849.4310859.9810870.5310881.0810891.6310902.1710912.7210923.2710944.37
10954.9210965.4710976.0210997.1211007.6611018.2111039.3111070.9611081.5111197.80
11309.6011324.5611365.5011410.2211421.4011454.9411488.4811615.2411656.1911886.64
  151.19  148.70  147.70  147.87  147.21  148.04  148.43  149.04  149.57  149.72
  150.52  150.52  154.25  154.25  153.89  154.92  155.04  155.33  155.10  155.92
  155.84  156.85  158.28  158.88  158.72  159.09  159.05  159.81  160.10  160.28
  160.90  160.44  162.20  160.13  155.53  152.15  146.02  140.92  140.03  139.52
  140.34  143.04  150.26  160.01  163.93  164.62  164.26  162.54  163.16  164.82
  165.44  165.21  165.64  165.44  165.70  165.25  165.47  164.34  164.36  161.83
 -848.81 -851.30 -852.30 -852.13 -852.79 -851.96 -851.57 -850.96 -850.43 -850.28
 -849.48  145.52  149.25 -845.75 -846.11 -845.08 -844.96 -844.67 -844.90 -844.08
 -844.16 -843.15 -841.72 -841.12 -841.28 -840.91 -840.95 -840.19 -839.90 -839.72
 -839.10 -839.56 -837.80 -839.87 -844.47 -847.85 -853.98 -859.08 -859.97 -860.48
 -859.66 -856.96 -849.74 -839.99 -836.07 -835.38 -835.74 -837.46 -836.84 -835.18
 -834.56 -834.79 -834.36 -834.56 -834.30 -834.75 -834.53 -835.66 -835.64 -838.17
Pier Skew, UpSta & Num, DnSta & Num=  ,9856.72, 2 ,9912.12, 2 , 0 , 0 , 0 ,,
    4.00    4.00
 -849.19  150.81
    4.00    4.00
 -848.56  151.44
Pier Skew, UpSta & Num, DnSta & Num=  ,9939.72, 2 ,9995.12, 2 , 0 , 0 , 0 ,,
    4.00    4.00
 -848.25  151.75
    4.00    4.00
 -847.62  152.38
Pier Skew, UpSta & Num, DnSta & Num=  ,10022.72, 2 ,10078.12, 2 , 0 , 0 , 0 ,,
    4.00    4.00
 -847.30  152.70
    4.00    4.00
 -846.68  153.32
BR Coef=-1 , 0 , 0 ,, 0 ,,,0.8,0,1,0,
WSPro=,,,, 1 ,,,, 0 ,,,, 0 ,,,,-1 ,-1 ,-1 , 0 , 0 , 0 , 0 , 0
BC Design=,, 0 ,, 0 ,,,,,,

Type RM Length L Ch R = 1 ,5007.807,1379.426200,1379.426200,1379.426200
XS GIS Cut Line= 4
620760.834698768730976.359899843619233.826874167730704.536517456
618307.686412394730301.473113999618229.247226565730261.178908747
#Sta/Elev= 30
9262.397204.71539369.895197.37289400.367 191.8129420.681180.84419430.838 167.552
9440.996160.3179 9461.31 154.5279481.624143.58459867.598136.85279918.384132.9614
9959.013116.994810101.21115.438410162.16118.577610172.31130.437910192.63134.8623
10324.67132.851710344.99135.080510375.46130.268410537.97137.330610609.07133.7013
10912.49 138.86711052.06135.070311182.93136.7261 11302.9133.393911422.87135.8932
11510.11133.363311608.27135.2487 11662.8140.218711760.95136.783411911.64143.2422
#Mann= 3 , 0 , 0
9262.397  0.0716       09262.397  0.0716       011911.64  0.0716       0
#XS Ineff= 2 , 0
       09770.338        10231.91       0
Bank Sta=9262.397,11911.64
Exp/Cntr=0.3,0.1

Type RM Length L Ch R = 1 ,3628.381,0.000000,0.000000,0.000000
XS GIS Cut Line= 3
621236.024294138 730004.61735636619761.240397424 729447.28623262
618955.740712761730176.475420828
#Sta/Elev= 30
7910.928199.33627997.545167.30468083.067145.01498115.138139.26998179.279134.2348
8510.677124.55528564.128124.10968585.509128.4939 8617.58128.48418701.911124.0379
8843.351123.51839041.367125.76199109.331131.75519182.808131.22259211.096125.9563
9648.008127.50539797.013136.42659826.814129.72059846.637118.51239886.416107.0768
9960.919107.88959995.01599.5412510035.48100.509610065.22104.827510089.44112.3422
10102.93119.994710139.72128.089210183.86124.019310386.19127.696110574.04125.9607
#Mann= 3 , 0 , 0
7910.928  0.1137       07910.928  0.1137       010574.04  0.1137       0
#XS Ineff= 2 , 0
       09684.062        10410.58       0
Bank Sta=7910.928,10574.04
Exp/Cntr=0.3,0.1